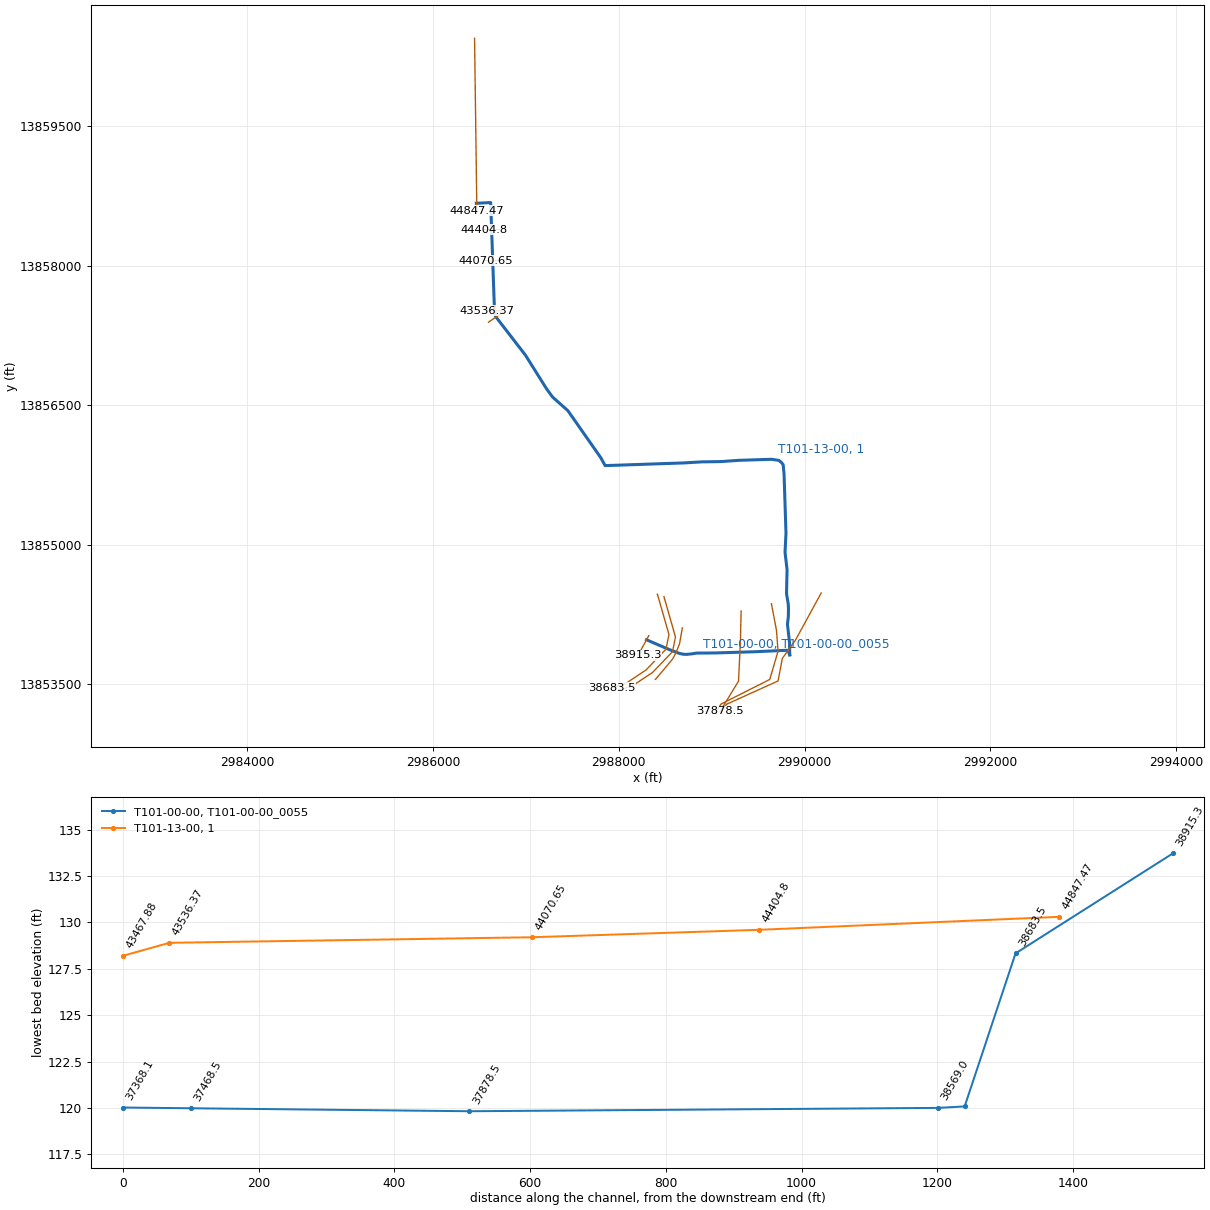
--- T101-00-00.PRJ (project) ---

Proj Title=T101-00-00
Current Plan=p02
Default Exp/Contr=.3,.1
English Units
Geom File=g01
Flow File=f01
Flow File=f02
Plan File=p01
Plan File=p02
Y Axis Title=Elevation
X Axis Title(PF)=Main Channel Distance
X Axis Title(XS)=Station
BEGIN DESCRIPTION:
HCFCD Watershed Unit ID: T
M3 Study Identifier: 2007_Effective_T
Engineer: HCFCD
Project Name: EffectiveFEMA Study for watershed Barker Reservoir (T)
Study Completion Date: 6/18/2007
FEMA Case Number: [No Data]
FEMA Approval Date: [No Date in Database]
Vertical Datum: NAVD 1988
Datum Note: 2001 ADJ
HYDRAULICS
HCFCD Unit No.:  T101-00-00
Hydraulic Program Name: HEC-RAS
Hydraulic Program Version: 3.0.1
Steady Hydraulic Model: Yes
Unsteady Hydraulic Model: No
Update1:
The effective FEMA hydraulic model for unit number T101-00-00 has been updated by FEMA LOMR 13-06-0262P with an effective date of 5/20/2013.
Update2:
HCFCD Nomenclature Update 2014,  Effective date of 5/20/2013.
Update 3:
The effective FEMA hydraulic model for unit number T101-00-00 has been updated by FEMA LOMR 13-06-4636P with an effective date of 08/21/2014.
Update 4:
The effective FEMA hydraulic model for unit number T101-00-00 has been updated by FEMA LOMR 14-06-1079P with an effective date of 09/15/2014.
END DESCRIPTION:
DSS Export Rating Curves= 0
DSS Export Rating Curve Sorted= 0
DSS Export Volume Flow Curves= 0
DXF OffsetX= 0
DXF OffsetY= 0
DXF ScaleX= 1
DXF ScaleY= 10

--- T101-00-00.p02 (plan) ---

Plan Title=FEMA Effective Floodway 2014
Version=Version 3.0.1  May 2012
Short Identifier=Eff+LOMR FW
Geom File=g01
Flow File=f02
Subcritical Flow
K Sum by GR= 0
Std Step Tol= 0.01
Critical Tol= 0.01
Num of Std Step Trials= 20
Max Error Tol= 0.3
Flow Tol Ratio= 0.001
Split Flow NTrial= 30
Split Flow Tol= 0.02
Split Flow Ratio= 0.02
Log Output Level= 0
Friction Slope Method= 1
Unsteady Friction Slope Method= 2
Parabolic Critical Depth
Global Vel Dist= 0 , 0 , 0
Global Log Level= 0
CheckData=True
Encroach Param=-1 ,0,0, 2
Encroach River=T101-00-00
Encroach Reach=T101-00-00_0055
Encroach Node=38915.3
       1  4989.3  5034.1
Encroach Node=38683.5
       1  4950.6  5147.9
Encroach Node=38646.0
       1  4950.6  5147.9
Encroach Node=38608.5
       1  4950.6  5147.9
Encroach Node=38569.0
       1    4944  5147.9
Encroach Node=37878.5
       1  4950.7  5147.9
Encroach Node=37468.5
       1  4950.7  5147.9
Encroach Node=37416.0
       1  4950.7  5147.9
Encroach Node=37368.1
       1  4963.6  5052.3
Encroach Reach=T101-00-00_Main
Encroach Node=36787.4
       1  4963.6  5052.3
Encroach Node=36712.7
       1  4963.6  5051.7
Encroach Node=36690.7
       1  4963.6  5051.7
Encroach Node=36668.7
       1  4963.6  5051.7
Encroach Node=36223.5
       1  4944.3  5058.6
Encroach Node=35418.0
       1  4937.3  5065.1
Encroach Node=35330.8
       1  4921.7  5071.9
Encroach Node=35199.0
       1  4924.5  5068.9
Encroach Node=35166.5
       1  4924.5  5068.9
Encroach Node=35134.0
       1  4924.5  5068.9
Encroach Node=34976.5
       1  4911.4  5081.6
Encroach Node=34876.3
       1  4911.4  5081.6
Encroach Node=34843.8
       1  4911.4  5081.6
Encroach Node=34811.3
       1  4911.4  5081.6
Encroach Node=34337.0
       1  4942.4  5052.7
Encroach Node=33870.8
       1  4942.4  5052.7
Encroach Node=33293.6
       1  4939.2  5062.1
Encroach Node=32830.0
       1  4947.2  5053.6
Encroach Node=31944.0
       1  4949.3  5053.3
Encroach Node=30826.4
       1  4949.3  5053.3
Encroach Node=30066.8
       1  4934.5    5044
Encroach Node=29859.0
       1 4923.09 5064.57
Encroach Node=29823.0
       1 4923.09 5064.57
Encroach Node=29787.0
       1 4923.09 5064.57
Encroach Node=29048.6
       1  4933.8  5063.8
Encroach Node=28854.0
       1  4933.8  5063.8
Encroach Node=27842.9
       1  4933.9    5061
Encroach Node=27009.2
       1  4924.4    5092
Encroach Node=26849.0
       1  4924.4    5092
Encroach Node=26809.0
       1  4924.4    5092
Encroach Node=26769.0
       1  4924.4    5092
Encroach Node=26158.9
       1  4927.5  5069.2
Encroach Node=25733.6
       1  4927.6  5069.2
Encroach Node=24718.5
       1  4919.3  5064.1
Encroach Node=23838.2
       1  4911.5  5113.4
Encroach Node=23734.5
       1  4930.5  5107.8
Encroach Node=23714.0
       1  4930.5  5107.8
Encroach Node=23693.5
       1  4930.5  5107.8
Encroach Node=23664.0
       1  4951.4  5081.1
Encroach Node=23628.0
       1  4951.4  5081.1
Encroach Node=23592.0
       1  4951.4  5081.1
Encroach Node=23539.0
       1  4941.1  5122.7
Encroach Node=23436.0
       1  4941.1  5122.7
Encroach Node=23333.0
       1  4941.1  5122.7
Encroach Node=23308.5
       1 4919.72 5077.52
Encroach Node=23298.0
       1 4919.72 5077.52
Encroach Node=23287.5
       1 4919.72 5077.52
Encroach Node=22837.5
       1    4926  5065.2
Encroach Node=21873.5
       1  4948.7  5036.8
Encroach Node=20917.4
       1  4953.8  5076.9
Encroach Node=19834.0
       1    4957  5107.7
Encroach Node=19352.2
       1  4925.8  5074.7
Encroach Node=18839.6
       1  4925.8  5074.7
Encroach Node=18730.3
       1  4925.8  5074.7
Encroach Node=18674.3
       1  4925.8  5074.7
Encroach Node=18618.3
       1  4925.8  5074.7
Encroach Node=18103.0
       1  4907.2  5093.8
Encroach Node=17920.6
       1  4907.2  5093.8
Encroach Node=17864.1
       1  4907.2  5093.8
Encroach Node=17807.6
       1  4907.2  5093.8
Encroach Node=17055.9
       1  4940.6  5089.8
Encroach Node=16184.3
       1  4920.1  5082.8
Encroach Node=16046.4
       1  4920.1  5082.8
Encroach Node=16019.4
       1  4920.1  5082.8
Encroach Node=15992.4
       1  4920.1  5082.8
Encroach Node=15394.4
       1  4926.9  5086.1
Encroach Node=14998.1
       1  4919.8  5061.5
Encroach Node=14118.0
       1  4918.4    5082
Encroach Node=13999.7
       1  4918.4    5082
Encroach Node=13972.7
       1  4918.4    5082
Encroach Node=13945.7
       1  4918.4    5082
Encroach Node=13308.5
       1  4896.8  5075.9
Encroach Node=12830.4
       1  4917.4  5075.5
Encroach Node=12374.9
       1  4922.3  5065.9
Encroach Node=11684.1
       1  4922.3  5065.9
Encroach Node=11260.6
       1  4905.6  5087.1
Encroach Node=10621.5
       1  4905.6  5087.1
Encroach Node=9809.1
       1  4922.5  5118.2
Encroach Node=9657.0
       1  4922.5    5118
Encroach Node=9600.5
       1  4922.5    5118
Encroach Node=9544.0
       1  4922.5    5118
Encroach Node=9090.1
       1  4901.3    5085
Encroach Node=8180.2
       1  4889.7  5069.3
Encroach Node=7504.8
       1  4893.7  5069.9
Encroach Node=7197.5
       1  4893.7  5069.9
Encroach Node=6168.3
       1    4890    5070
Encroach Node=5537.8
       1    4735    5265
Encroach Reach=1
Encroach Node=44847.47
       1    1960    2040
Encroach Node=44742.47
       1    1970    2030
Encroach Node=44404.8
       1    1980    2020
Encroach Node=44070.65
       1    1980    2020
Encroach Node=43536.37
       1    1960    2040
Encroach Node=43467.88
       1    1960    2040
Encroach Node=43054.48
       1    1960    2040
Encroach Node=42407.73
       1    1960    2040
Encroach Node=41664.82
       1    1980    2020
Encroach Node=41171.75
       1    1970    2030
Encroach Node=40473.45
       1    1980    2020
Encroach Node=39674.87
       1    1980    2020
Encroach Node=39526.31
       1    1980    2020
Encroach Node=39281.9
       1    1980    2020
Encroach Node=38647.7
       1    1980    2020
Encroach Node=38027.6
       1    1980    2020
Encroach Node=37408.2
       1    1960    2040
Encroach River=T101-13-00
Encroach Reach=T101-00-00_0055
Encroach Node=38915.3
       1  4989.3  5034.1
Encroach Node=38683.5
       1  4950.6  5147.9
Encroach Node=38646.0
       1  4950.6  5147.9
Encroach Node=38608.5
       1  4950.6  5147.9
Encroach Node=38569.0
       1    4944  5147.9
Encroach Node=37878.5
       1  4950.7  5147.9
Encroach Node=37468.5
       1  4950.7  5147.9
Encroach Node=37416.0
       1  4950.7  5147.9
Encroach Node=37368.1
       1  4963.6  5052.3
Encroach Reach=1
Encroach Node=44847.47
       1    1960    2040
Encroach Node=44742.47
       1    1960    2040
Encroach Node=44404.8
       1    1980    2020
Encroach Node=44070.65
       1    1980    2020
Encroach Node=43536.37
       1    1960    2040
Encroach Node=43467.88
       1    1960    2040
Encroach Node=43054.48
       1    1960    2040
Encroach Node=42407.73
       1    1960    2040
Encroach Node=41664.82
       1    1980    2020
Encroach Node=41171.75
       1    1970    2030
Encroach Node=40473.45
       1    1980    2020
Encroach Node=39674.87
       1    1980    2020
Encroach Node=39526.31
       1    1980    2020
Encroach Node=39281.9
       1    1980    2020
Encroach Node=38647.7
       1    1975    2025
Encroach Node=38027.6
       1    1955    2045
Encroach Node=37408.2
       1    1960    2040
BEGIN DESCRIPTION:
FEMA Effective June 2007 +...+ LOMR 14-06-1079P
END DESCRIPTION:
Computation Interval=1HOUR
Output Interval=1HOUR
Run HTab= 0
Run UNet= 0
Run PostProcess= 0
UNET Theta= 1
UNET ZTol= 0.02
UNET ZSATol= 0.05
UNET MxIter= 20
UNET MaxInSteps= 0
UNET DtIC= 0
UNET DtMin= 0
UNET MaxCRTS= 20
UNET WFStab= 2
UNET SFStab= 1
UNET WFX= 1
UNET SFX= 1
UNET Convert EG Bridges=-1
UNET Use Existing IB Tables=-1
Instantaneous Interval=1HOUR
DSS File=dss
Write IC File= 0
IC Time=0
Write Velocity= 0
Write Detailed= 0

--- T101-00-00.p01 (plan) ---

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Plan Title=FEMA Effective Multi-Profile 2014
Program Version=4.10
Short Identifier=Eff+LOMR MP
Geom File=g01
Flow File=f01
Unsteady Bridges Friction Slope Method= 1
Encroach Param=-1 ,0,0, 0
Run WQNet= 0
UNET Theta Warmup= 1
UNET DSS MLevel= 4
UNET DZMax Abort= 100
UNET Froude Reduction=False
UNET Froude Limit= 1
UNET Froude Power= 10
UNET Time Slicing=0,0, 5
UNET Junction Losses=0
IC Time=0,,
Write IC File at Sim End=0
Echo Input=False
Echo Parameters=False
Echo Output=False
WQ AD Non Conservative
WQ ULTIMATE=-1
WQ Max Comp Step=1HOUR
WQ Output Interval=15MIN
WQ Output Selected Increments= 0
WQ Output face flow=0
WQ Output face velocity=0
WQ Output face area=0
WQ Output face dispersion=0
WQ Output cell volume=0
WQ Output cell surface area=0
WQ Output cell continuity=0
WQ Output cumulative cell continuity=0
WQ Output face conc=0
WQ Output face dconc_dx=0
WQ Output face courant=0
WQ Output face peclet=0
WQ Output face adv mass=0
WQ Output face disp mass=0
WQ Output cell mass=0
WQ Output cell source sink temp=0
WQ Output cell source sink nsm=0
WQ Output MaxMinRange=-1
WQ Daily Max Min Mean=-1
WQ Daily Range=0
WQ Daily Time=0
WQ Create Restart=0
WQ Fixed Restart=0
WQ System Summary=0
WQ Use Fixed Temperature=0
Sorting and Armoring Iterations= 10
XS Update Threshold= 0.02
Hydraulics Update Threshold= 0.02
Energy Slope Method= 1
Volume Change Method= 0
XS Weighting Method= 0
Number of US Weighted Cross Sections= 1
Number of DS Weighted Cross Sections= 1
Upstream XS Weight=0.25
Main XS Weight=0.5
Downstream XS Weight=0.25
Number of DS XS's Weighted with US Boundary= 1
Upstream Boundary Weight= 1
Weight of XSs Associated with US Boundary= 0
Number of US XS's Weighted with DS Boundary= 1
Downstream Boundary Weight= 0.5
Weight of XSs Associated with DS Boundary= 0.5
Sediment Output Level= 4
Mass or Volume Output= 0
Output Increment Type= 1
Profile and TS Output Increment= 10
XS Output Flag= 0
XS Output Increment= 10
Disregard all LS=0
Disregard all Conn=0
Disregard all Breaches=0
Disregard all Pumps=0

--- T101-00-00.f02 (steady flow) ---

Flow Title=Floodway
Program Version=4.10
Number of Profiles= 2
Profile Names=100-YR,100-YRFW
River Rch & RM=T101-13-00,1               ,44847.47
   808.9   808.9
River Rch & RM=T101-13-00,1               ,41171.75
    1404    1404
River Rch & RM=T101-00-00,T101-00-00_0055 ,38915.3
      55      55
River Rch & RM=T101-00-00,T101-00-00_0055 ,37878.5
      66      66
River Rch & RM=T101-00-00,T101-00-00_Main ,36787.4
    1404    1404
River Rch & RM=T101-00-00,T101-00-00_Main ,36223.5
    1404    1404
River Rch & RM=T101-00-00,T101-00-00_Main ,35199
    2163    2163
River Rch & RM=T101-00-00,T101-00-00_Main ,34876.3
    2244    2244
River Rch & RM=T101-00-00,T101-00-00_Main ,33870.8
    2442    2442
River Rch & RM=T101-00-00,T101-00-00_Main ,32830
    3015    3015
River Rch & RM=T101-00-00,T101-00-00_Main ,30826.4
    3015    3015
River Rch & RM=T101-00-00,T101-00-00_Main ,29859
    3027    3027
River Rch & RM=T101-00-00,T101-00-00_Main ,28854
    3273    3273
River Rch & RM=T101-00-00,T101-00-00_Main ,27842.9
    3540    3540
River Rch & RM=T101-00-00,T101-00-00_Main ,26849
    3824    3824
River Rch & RM=T101-00-00,T101-00-00_Main ,25733.6
    4098    4098
River Rch & RM=T101-00-00,T101-00-00_Main ,24718.5
    4366    4366
River Rch & RM=T101-00-00,T101-00-00_Main ,23308.5
    4648    4648
River Rch & RM=T101-00-00,T101-00-00_Main ,22837.5
    4737    4737
River Rch & RM=T101-00-00,T101-00-00_Main ,21873.5
    4927    4927
River Rch & RM=T101-00-00,T101-00-00_Main ,20917.4
    5116    5116
River Rch & RM=T101-00-00,T101-00-00_Main ,19834
    5330    5330
River Rch & RM=T101-00-00,T101-00-00_Main ,18730.3
    5570    5570
River Rch & RM=T101-00-00,T101-00-00_Main ,17920.6
    5730    5730
River Rch & RM=T101-00-00,T101-00-00_Main ,17055.9
    5878    5878
River Rch & RM=T101-00-00,T101-00-00_Main ,16046.4
    6181    6181
River Rch & RM=T101-00-00,T101-00-00_Main ,14998.1
    6465    6465
River Rch & RM=T101-00-00,T101-00-00_Main ,13999.7
    6765    6765
River Rch & RM=T101-00-00,T101-00-00_Main ,12830.4
    7082    7082
River Rch & RM=T101-00-00,T101-00-00_Main ,11684.1
    7409    7409
River Rch & RM=T101-00-00,T101-00-00_Main ,10621.5
    7712    7712
River Rch & RM=T101-00-00,T101-00-00_Main ,9090.1
    8149    8149
River Rch & RM=T101-00-00,T101-00-00_Main ,8180.2
    8408    8408
River Rch & RM=T101-00-00,T101-00-00_Main ,7197.5
    8688    8688
River Rch & RM=T101-00-00,T101-00-00_Main ,5537.8
    9234    9234
Boundary for River Rch & Prof#=T101-00-00,T101-00-00_0055 , 1
Up Type= 0
Dn Type= 0
Boundary for River Rch & Prof#=T101-00-00,T101-00-00_0055 , 2
Up Type= 0
Dn Type= 0
Boundary for River Rch & Prof#=T101-00-00,T101-00-00_Main , 1
Up Type= 0
Dn Type= 3
Dn Slope=0.0004
Boundary for River Rch & Prof#=T101-00-00,T101-00-00_Main , 2
Up Type= 0
Dn Type= 3
Dn Slope=0.0004
DSS Import GetInterval= 0
DSS Import GetPeak= 0
DSS Import FillOption= 0

--- T101-00-00.f01 (steady flow) ---

Flow Title=FEMA Effective
Version=Version 3.0.1  May 2012
Number of Profiles= 4
Profile Names=10PCT_10yr,2PCT_50yr,1PCT_100yr,0.2PCT_500yr
River Rch & RM=T101-13-00,1               ,44847.47
   417.2   676.4   808.9  1263.5
River Rch & RM=T101-13-00,1               ,41171.75
     724    1168    1404    2133
River Rch & RM=T101-00-00,T101-00-00_0055 ,38915.3
      28      46      55      82
River Rch & RM=T101-00-00,T101-00-00_0055 ,37878.5
      34      55      66      98
River Rch & RM=T101-00-00,T101-00-00_Main ,36787.4
     724    1168    1404    2133
River Rch & RM=T101-00-00,T101-00-00_Main ,36223.5
     724    1168    1404    2133
River Rch & RM=T101-00-00,T101-00-00_Main ,35199
    1109    1797    2163    3275
River Rch & RM=T101-00-00,T101-00-00_Main ,34876.3
    1151    1824    2244    3392
River Rch & RM=T101-00-00,T101-00-00_Main ,33870.8
    1255    1890    2442    3678
River Rch & RM=T101-00-00,T101-00-00_Main ,32830
    1563    2519    3015    4412
River Rch & RM=T101-00-00,T101-00-00_Main ,30826.4
    1563    2519    3015    4412
River Rch & RM=T101-00-00,T101-00-00_Main ,29859
    1565    2528    3027    4485
River Rch & RM=T101-00-00,T101-00-00_Main ,28854
    1693    2733    3273    4848
River Rch & RM=T101-00-00,T101-00-00_Main ,27842.9
    1832    2955    3540    5241
River Rch & RM=T101-00-00,T101-00-00_Main ,26849
    1979    3191    3824    5659
River Rch & RM=T101-00-00,T101-00-00_Main ,25733.6
    2121    3418    4098    6062
River Rch & RM=T101-00-00,T101-00-00_Main ,24718.5
    2260    3641    4366    6457
River Rch & RM=T101-00-00,T101-00-00_Main ,23308.5
    2405    3876    4648    6874
River Rch & RM=T101-00-00,T101-00-00_Main ,22837.5
    2451    3950    4737    7006
River Rch & RM=T101-00-00,T101-00-00_Main ,21873.5
    2549    4109    4927    7287
River Rch & RM=T101-00-00,T101-00-00_Main ,20917.4
    2646    4266    5116    7566
River Rch & RM=T101-00-00,T101-00-00_Main ,19834
    2756    4444    5330    7883
River Rch & RM=T101-00-00,T101-00-00_Main ,18730.3
    2880    4644    5570    8238
River Rch & RM=T101-00-00,T101-00-00_Main ,17920.6
    2963    4778    5730    8474
River Rch & RM=T101-00-00,T101-00-00_Main ,17055.9
    3039    4901    5878    8694
River Rch & RM=T101-00-00,T101-00-00_Main ,16046.4
    3194    5149    6181    9135
River Rch & RM=T101-00-00,T101-00-00_Main ,14998.1
    3338    5381    6465    9547
River Rch & RM=T101-00-00,T101-00-00_Main ,13999.7
    3491    5627    6765    9984
River Rch & RM=T101-00-00,T101-00-00_Main ,12830.4
    3653    5887    7082   10446
River Rch & RM=T101-00-00,T101-00-00_Main ,11684.1
    3820    6154    7409   10922
River Rch & RM=T101-00-00,T101-00-00_Main ,10621.5
    3974    6402    7712   11363
River Rch & RM=T101-00-00,T101-00-00_Main ,9090.1
    4197    6759    8149   11998
River Rch & RM=T101-00-00,T101-00-00_Main ,8180.2
    4329    6972    8408   12375
River Rch & RM=T101-00-00,T101-00-00_Main ,7197.5
    4472    7201    8688   12783
River Rch & RM=T101-00-00,T101-00-00_Main ,5537.8
    4774    7666    9234   13655
Boundary for River Rch & Prof#=T101-00-00,T101-00-00_0055 , 1
Up Type= 0
Dn Type= 0
Boundary for River Rch & Prof#=T101-00-00,T101-00-00_0055 , 2
Up Type= 0
Dn Type= 0
Boundary for River Rch & Prof#=T101-00-00,T101-00-00_0055 , 3
Up Type= 0
Dn Type= 0
Boundary for River Rch & Prof#=T101-00-00,T101-00-00_0055 , 4
Up Type= 0
Dn Type= 0
Boundary for River Rch & Prof#=T101-00-00,T101-00-00_Main , 1
Up Type= 0
Dn Type= 3
Dn Slope=.0004
Boundary for River Rch & Prof#=T101-00-00,T101-00-00_Main , 2
Up Type= 0
Dn Type= 3
Dn Slope=.0004
Boundary for River Rch & Prof#=T101-00-00,T101-00-00_Main , 3
Up Type= 0
Dn Type= 3
Dn Slope=.0004
Boundary for River Rch & Prof#=T101-00-00,T101-00-00_Main , 4
Up Type= 0
Dn Type= 3
Dn Slope=.0004
DSS Import GetInterval= 0
DSS Import GetPeak= 0
DSS Import FillOption= 0

--- T101-00-00.g01 (geometry) ---

Geom Title=T101-00-00
Program Version=4.10

Junct Name=T101_Junctio
Junct Desc=, 0 , 0 ,-1 ,0
Up River,Reach=T101-00-00      ,T101-00-00_0055
Up River,Reach=T101-13-00      ,1
Dn River,Reach=T101-00-00      ,T101-00-00_Main
Junc L&A=580.7,0
Junc L&A=0,0

River Reach=T101-00-00      ,T101-00-00_0055
Reach XY= 15
      2988298.94     13853977.07      2988358.75       13853951.
      2988545.25       13853871.      2988645.25       13853833.
       2988694.5       13853821.        2988734.       13853820.
       2988797.5       13853827.      2988838.75       13853834.
      2989034.25       13853835.        2989457.       13853848.
        2989812.       13853864.        2989812.       13853864.
      2989812.17     13853863.81       2989828.5       13853845.
 2989840.500062613853814.9998033

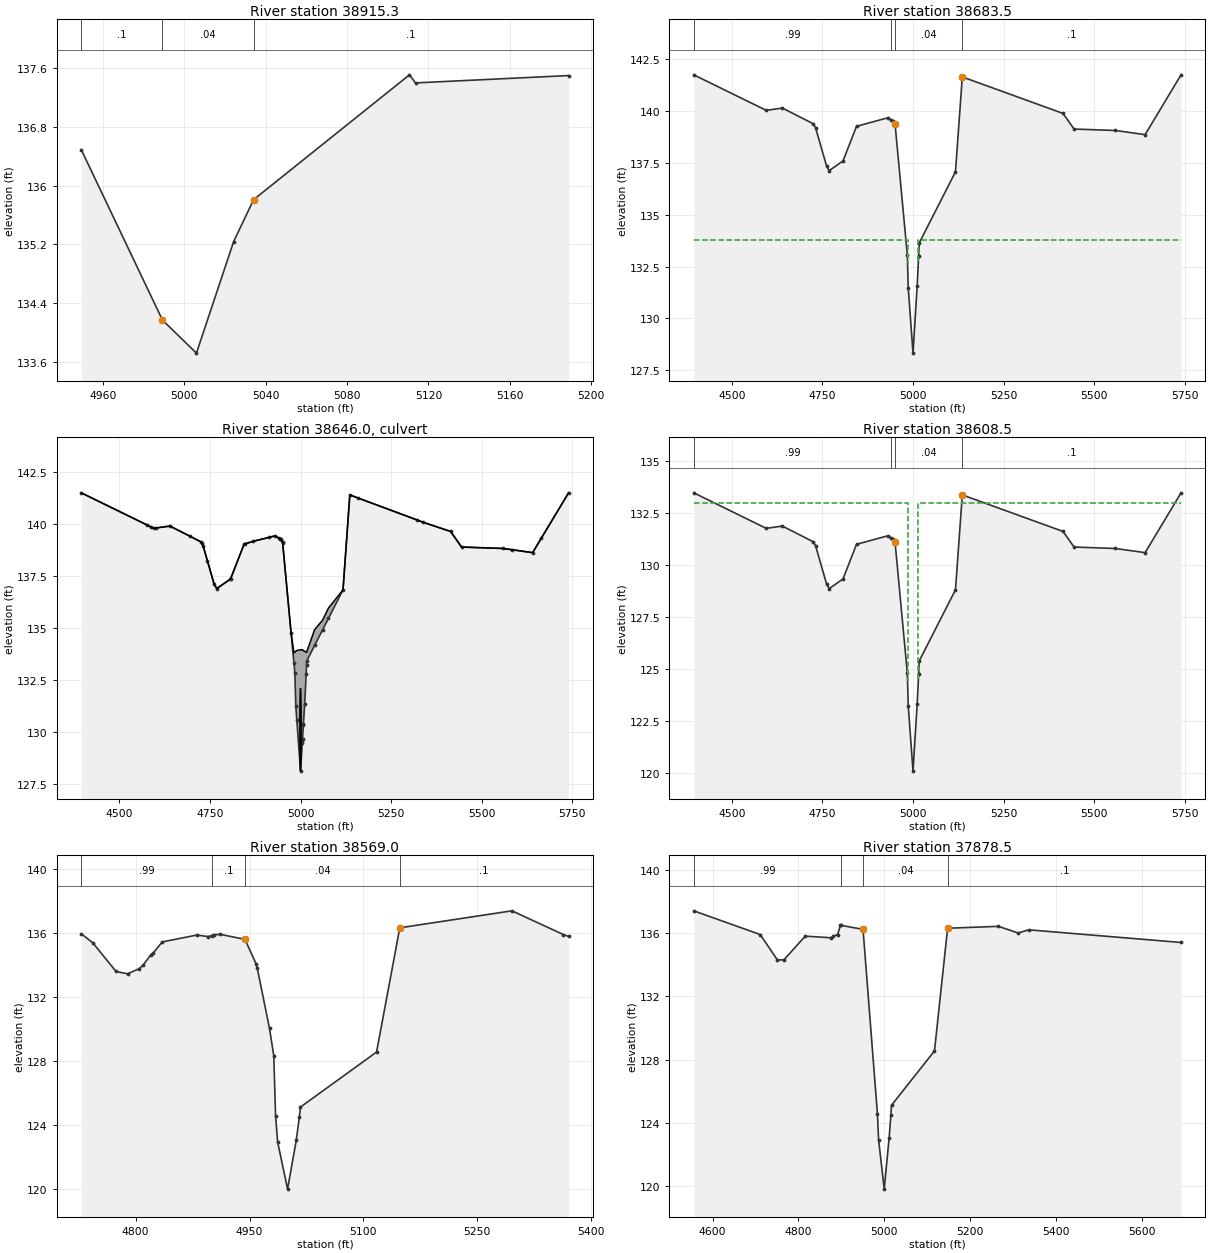
Type RM Length L Ch R = 1 ,38915.3 ,213.6,231.8,209.7
BEGIN DESCRIPTION:
Cross Section 38915.3
END DESCRIPTION:
XS GIS Cut Line= 3
      2988323.15     13854021.49      2988208.16      13853811.4
      2988208.16      13853811.4
#Sta/Elev= 8
  4949.4  136.49  4989.3  134.17    5006  133.72  5024.3  135.24  5034.1  135.81
  5110.7  137.51  5113.7   137.4  5188.9   137.5
#Mann= 3 , 1 , 0
  4949.4      .1       0  4989.3     .04       0  5034.1      .1       0
Bank Sta=4989.3,5034.1
XS Rating Curve= 0 ,0
Exp/Cntr=0.5,0.3

Type RM Length L Ch R = 1 ,38683.5 ,75,75,75
BEGIN DESCRIPTION:
Upstream Section of Bridge/Culvert/Weir
END DESCRIPTION:
XS GIS Cut Line= 6
      2988415.64     13854468.08      2988540.08     13854033.81
      2988508.43     13853876.34      2988293.19     13853651.89
      2988074.89     13853507.37      2987926.46     13853459.89
#Sta/Elev= 26
  4394.9  141.73  4594.9  140.02  4639.5  140.13  4725.2  139.37    4731  139.19
  4761.5  137.34  4768.8  137.12  4806.8  137.58  4844.1  139.25  4930.2  139.66
    4940  139.55  4945.8  139.49  4950.6  139.34  4984.3  133.07    4987  131.45
  5000.1  128.33  5011.5  131.55  5015.6  132.99  5017.1  133.63  5117.3  137.06
  5136.1  141.63  5414.3  139.87  5444.5  139.12  5558.6  139.05  5640.7  138.85
  5739.9  141.73
#Mann= 4 , 1 , 0
  4394.9     .99       0    4940      .1       0  4950.6     .04       0
  5136.1      .1       0
#XS Ineff= 2 , 0
       0    4985   133.8    5015       0   133.8
Permanent Ineff=
       F       F
Bank Sta=4950.6,5136.1
XS Rating Curve= 0 ,0
Exp/Cntr=0.5,0.3

Type RM Length L Ch R = 2 ,38646.0 ,,,
BEGIN DESCRIPTION:
Detention Pond Inlet Structure
END DESCRIPTION:
Bridge Culvert--1,0,-1,-1, 0
Deck Dist Width WeirC Skew NumUp NumDn MinLoCord MaxHiCord MaxSubmerge Is_Ogee
10,55,3,0, 56, 56, , , 0.95, 0, 1,1,,
  4394.9  4575.5  4586.8  4594.9  4602.4  4639.5    4696  4725.2  4727.2    4731
  4742.8  4761.5  4768.8  4805.2  4806.8  4844.1  4846.7  4869.9  4912.3  4930.2
    4940  4942.5    4943  4945.8  4950.6  4950.7  4973.9  4981.9  4984.3    4987
  4989.8  5000.1  5004.9  5005.3  5005.5    5008  5008.1  5011.5  5015.6  5016.7
  5017.1  5038.9    5061  5077.1  5117.3  5136.1  5157.3  5322.3  5338.6  5414.3
  5444.5  5558.6  5584.1  5640.7  5664.8  5739.9
   141.5  139.96  139.86  139.79  139.81   139.9   139.4  139.14  139.08  138.96
  138.24  137.11  136.89  137.33  137.35  139.02  139.04  139.17  139.35  139.43
  139.32  139.29  139.28  139.26  139.11  139.09  134.77  133.79  133.83  133.87
  133.91  133.94  133.95  133.93  133.94   133.9   133.9  133.87  133.83  133.82
  133.84  134.91  135.37  135.95  136.83   141.4  141.26  140.19  140.08  139.64
  138.89  138.82  138.76  138.62  139.32   141.5
   141.5  139.96  139.86  139.79  139.81   139.9   139.4  139.14  139.08  138.96
  138.24  137.11  136.89  137.33  137.35  139.02  139.04  139.17  139.35  139.43
  139.32  139.29  139.28  139.26  139.11  139.09  134.77  133.29  132.84  131.22
  130.55   128.1  129.46  129.57  129.63  130.33  130.36  131.32  132.76  133.23
   133.4  134.15   134.9  135.45  136.83   141.4  141.26  140.19  140.08  139.64
  138.89  138.82  138.76  138.62  139.32   141.5
  4394.9  4575.5  4586.8  4594.9  4602.4  4639.5    4696  4725.2  4727.2    4731
  4742.8  4761.5  4768.8  4805.2  4806.8  4844.1  4846.7  4869.9  4912.3  4930.2
    4940  4942.5    4943  4945.8  4950.6  4950.7  4973.9  4981.9  4984.3    4987
  4989.8  5000.1  5004.9  5005.3  5005.5    5008  5008.1  5011.5  5015.6  5016.7
  5017.1  5038.9    5061  5077.1  5117.3  5136.1  5157.3  5322.3  5338.6  5414.3
  5444.5  5558.6  5584.1  5640.7  5664.8  5739.9
   137.5  135.97  135.87   135.8  135.88  135.91  135.41  135.15  135.09  134.97
  134.25  133.12   132.9  133.34  133.36  135.03  135.05  135.18  135.36  135.55
  135.71  135.75  135.73  135.63  135.46  135.46  134.58  133.79  133.83  133.87
  133.91  133.94  133.95  133.93  133.94   133.9   133.9  133.87  133.83  133.82
  133.84  134.91  135.37  135.95  136.73  137.41  137.51  136.44  136.34  135.89
  135.71  135.02  134.87  134.73  135.33   137.5
   133.5  131.96  131.86  131.79  131.81   131.9   131.4  131.14  131.08  130.96
  130.24  129.11  128.89  129.33  129.35  131.02  131.04  131.17  131.35  131.43
  131.32  131.29  131.28  131.26  131.11  131.09  126.77  125.29  124.84  123.22
  122.55   120.1  121.46  121.57  121.63  122.33  122.36  123.32  124.76  125.23
   125.4  126.15   126.9  127.45  128.83   133.4  133.26  132.19  132.08  131.64
  130.89  130.82  130.76  130.62  131.32   133.5
BR Coef= 1 , 0 , 0 ,1.25, 0 ,,,0.8,-1,2,0,
WSPro=,,,, 1 ,,,, 0 ,,,, 0 ,,,,-1 ,-1 ,-1 , 0 , 0 , 0 , 0 , 0
Culvert=1,4,,55,0.024,0.2,1,1,3,128.1,5000,120.1,5000,Culvert #1  , 0 ,10
Culvert Bottom n=0.024
BR U #Sta/Elev= 56
  4394.9   141.5  4575.5  139.96  4586.8  139.86  4594.9  139.79  4602.4  139.81
  4639.5   139.9    4696   139.4  4725.2  139.14  4727.2  139.08    4731  138.96
  4742.8  138.24  4761.5  137.11  4768.8  136.89  4805.2  137.33  4806.8  137.35
  4844.1  139.02  4846.7  139.04  4869.9  139.17  4912.3  139.35  4930.2  139.43
    4940  139.32  4942.5  139.29    4943  139.28  4945.8  139.26  4950.6  139.11
  4950.7  139.09  4973.9  134.77  4981.9  133.29  4984.3  132.84    4987  131.22
  4989.8  130.55  5000.1   128.1  5004.9  129.46  5005.3  129.57  5005.5  129.63
    5008  130.33  5008.1  130.36  5011.5  131.32  5015.6  132.76  5016.7  133.23
  5017.1   133.4  5038.9  134.15    5061   134.9  5077.1  135.45  5117.3  136.83
  5136.1   141.4  5157.3  141.26  5322.3  140.19  5338.6  140.08  5414.3  139.64
  5444.5  138.89  5558.6  138.82  5584.1  138.76  5640.7  138.62  5664.8  139.32
  5739.9   141.5
BR U #Mann= 4
  4394.9     .99    4940      .1  4950.6     .04  5136.1      .1
BR U Banks=4950.6,5136.1
BR D #Sta/Elev= 56
  4394.9   133.5  4575.5  131.96  4586.8  131.86  4594.9  131.79  4602.4  131.81
  4639.5   131.9    4696   131.4  4725.2  131.14  4727.2  131.08    4731  130.96
  4742.8  130.24  4761.5  129.11  4768.8  128.89  4805.2  129.33  4806.8  129.35
  4844.1  131.02  4846.7  131.04  4869.9  131.17  4912.3  131.35  4930.2  131.43
    4940  131.32  4942.5  131.29    4943  131.28  4945.8  131.26  4950.6  131.11
  4950.7  131.09  4973.9  126.77  4981.9  125.29  4984.3  124.84    4987  123.22
  4989.8  122.55  5000.1   120.1  5004.9  121.46  5005.3  121.57  5005.5  121.63
    5008  122.33  5008.1  122.36  5011.5  123.32  5015.6  124.76  5016.7  125.23
  5017.1   125.4  5038.9  126.15    5061   126.9  5077.1  127.45  5117.3  128.83
  5136.1   133.4  5157.3  133.26  5322.3  132.19  5338.6  132.08  5414.3  131.64
  5444.5  130.89  5558.6  130.82  5584.1  130.76  5640.7  130.62  5664.8  131.32
  5739.9   133.5
BR D #Mann= 4
  4394.9     .99    4940      .1  4950.6     .04  5136.1      .1
BR D Banks=4950.6,5136.1
BC Design=,, 0 ,, 0 ,,,,,,
BC HTab HWMax=141.73
BC Use User HTab Curves=0
BC User HTab FreeFlow(D)= 0

Type RM Length L Ch R = 1 ,38608.5 ,39.5,39.5,39.5
BEGIN DESCRIPTION:
Downstream Section of Bridge/Culvert/Weir
END DESCRIPTION:
XS GIS Cut Line= 6
      2988485.75     13854441.44      2988610.18     13854007.17
      2988578.53      13853849.7      2988363.29     13853625.25
      2988144.99     13853480.73      2987996.57     13853433.25
#Sta/Elev= 26
  4394.9  133.48  4594.9  131.77  4639.5  131.88  4725.2  131.12    4731  130.94
  4761.5  129.09  4768.8  128.87  4806.8  129.33  4844.1     131  4930.2  131.41
    4940   131.3  4945.8  131.24  4950.6  131.09  4984.3  124.82    4987   123.2
  5000.1  120.08  5011.5   123.3  5015.6  124.74  5017.1  125.38  5117.3  128.81
  5136.1  133.38  5414.3  131.62  5444.5  130.87  5558.6   130.8  5640.7   130.6
  5739.9  133.48
#Mann= 4 , 1 , 0
  4394.9     .99       0    4940      .1       0  4950.6     .04       0
  5136.1      .1       0
#XS Ineff= 2 , 0
       0    4985     133    5015       0     133
Permanent Ineff=
       F       F
Bank Sta=4950.6,5136.1
XS Rating Curve= 0 ,0
Exp/Cntr=0.5,0.3

Type RM Length L Ch R = 1 ,38569.0 ,690.5,690.5,690.5
BEGIN DESCRIPTION:
Cross Section 38569.0 - Interpolated
END DESCRIPTION:
XS GIS Cut Line= 6
      2988684.21     13854105.38      2988654.17     13853933.74
      2988617.27      13853841.5      2988580.37     13853770.78
      2988398.96     13853555.55      2988393.26     13853551.57
#Sta/Elev= 30
  4728.4  135.93  4743.7  135.36  4774.1  133.58  4789.4  133.43  4804.6  133.75
  4810.3  133.99  4819.8  134.61  4823.2  134.73    4835  135.42  4880.7  135.85
  4895.9  135.75    4900  135.82  4902.7  135.87  4911.7  135.89    4944  135.58
  4958.9  134.02  4960.2  133.78  4976.3  130.02  4981.9  128.33  4984.3  124.56
    4987  122.94  5000.1     120  5011.5  123.04  5015.6  124.48  5017.1  125.12
  5117.3  128.55  5147.9   136.3  5295.6  137.36  5363.3  135.88  5370.2  135.76
#Mann= 4 , 1 , 0
  4728.4     .99       0    4900      .1       0    4944     .04       0
  5147.9      .1       0
Bank Sta=4944,5147.9
XS Rating Curve= 0 ,0
Exp/Cntr=0.3,0.1

Type RM Length L Ch R = 1 ,37878.5 ,382.1,410,384.3
BEGIN DESCRIPTION:
Cross Section 37878.5
END DESCRIPTION:
XS GIS Cut Line= 4
      2989317.04     13854287.13      2989310.05     13853961.81
      2989289.06     13853531.55      2989090.64     13853207.38
#Sta/Elev= 23
    4556   137.4    4711   135.9    4751   134.3    4766   134.3    4816   135.8
    4876   135.7  4881.4   135.8  4891.4   135.9  4898.1  136.49    4900  136.48
  4950.7  136.23  4984.3  124.56    4987  122.94  5000.1  119.82  5011.5  123.04
  5015.6  124.48  5017.1  125.12  5117.3  128.55  5147.9   136.3  5266.5  136.42
  5312.2     136  5337.2   136.2  5692.2   135.4
#Mann= 4 , 1 , 0
    4556     .99       0    4900      .1       0  4950.7     .04       0
  5147.9      .1       0
Bank Sta=4950.7,5147.9
XS Rating Curve= 0 ,0
Exp/Cntr=0.5,0.3

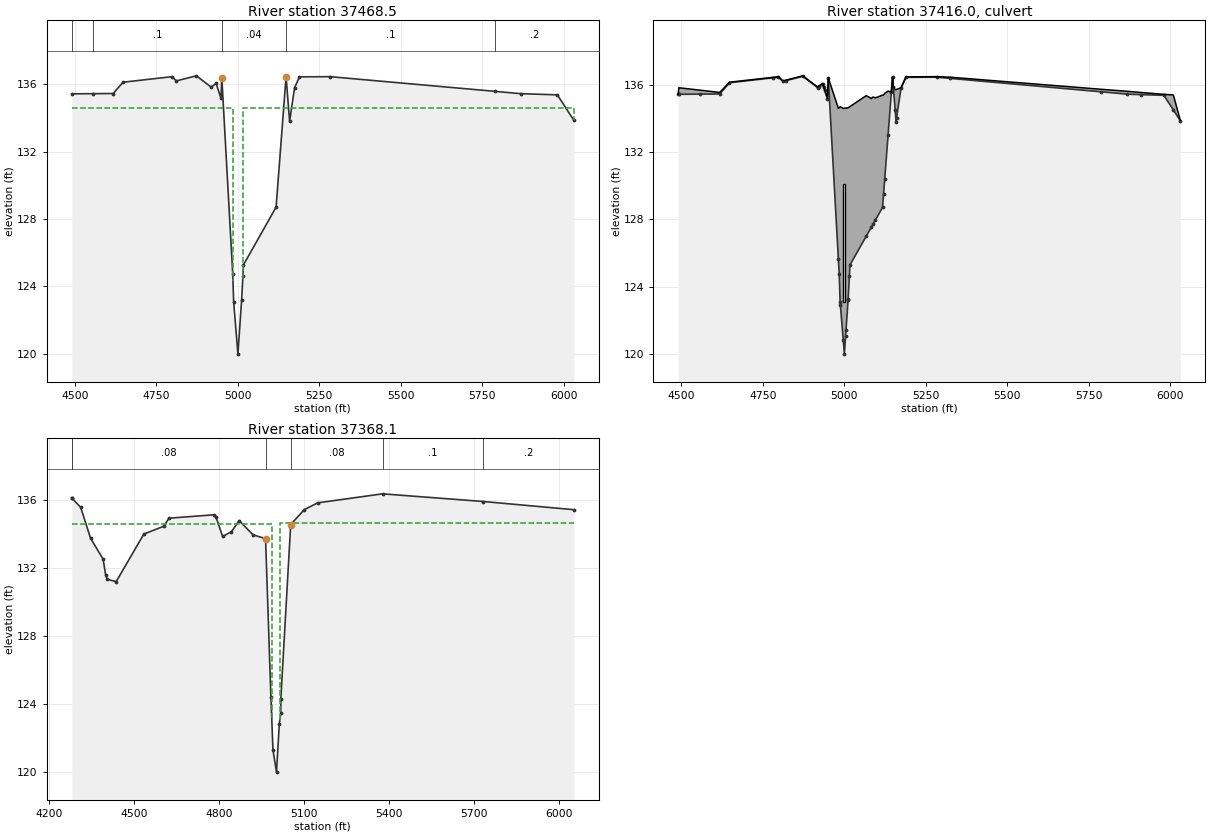
Type RM Length L Ch R = 1 ,37468.5 ,100.4,100.4,100.4
BEGIN DESCRIPTION:
Upstream Section of Bridge/Culvert/Weir
END DESCRIPTION:
XS GIS Cut Line= 6
      2989643.72     13854363.68      2989697.85     13854078.85
      2989714.78     13853854.51      2989625.61     13853550.11
      2989101.94     13853286.36      2989034.73     13853185.28
#Sta/Elev= 27
  4490.2  135.44    4556  135.45  4617.4  135.46  4647.5  136.13  4797.9  136.46
  4811.3  136.21  4872.5  136.51  4918.1  135.84  4933.1  136.06  4948.1  135.18
  4950.7  136.39  4984.3  124.72    4987   123.1  5000.1  119.98  5011.5   123.2
  5015.6  124.64  5017.1  125.28  5117.3  128.71  5147.9  136.46  5158.8   133.8
  5173.9   135.8    5189  136.45    5283  136.46  5787.9  135.59  5867.8  135.45
  5980.5  135.38  6031.1  133.87
#Mann= 5 , 1 , 0
  4490.2      .2       0    4556      .1       0  4950.7     .04       0
  5147.9      .1       0  5787.9      .2       0
#XS Ineff= 2 , 0
       0    4985   134.6    5015       0   134.6
Permanent Ineff=
       F       F
Bank Sta=4950.7,5147.9
XS Rating Curve= 0 ,0
Exp/Cntr=0.5,0.3

Type RM Length L Ch R = 2 ,37416.0 ,,,
BEGIN DESCRIPTION:
DS DETENTION STRUCTURE
END DESCRIPTION:
Bridge Culvert--1,0,-1,-1, 0
Deck Dist Width WeirC Skew NumUp NumDn MinLoCord MaxHiCord MaxSubmerge Is_Ogee
10,85,3,0, 55, 55, , , 0.95, 0, 1,1,,
  4490.2  4492.1    4556  4617.4  4647.5  4780.2  4797.9  4811.3  4822.2  4872.5
  4918.1  4920.1  4921.4  4922.9  4933.1  4936.4  4939.2  4948.1  4950.7  4981.6
  4984.3    4987  4987.9  4996.6  5000.1  5003.9  5005.1  5011.5  5011.6  5015.6
  5017.1  5067.3  5082.8  5087.8  5095.4  5117.3  5120.5    5124  5134.3  5144.3
  5147.9  5150.2    5156  5158.8  5160.1  5173.9    5189    5283  5323.4  5787.9
  5867.8  5909.7  5980.5  6009.8  6031.1
  135.46  135.83  135.69  135.55  136.16  136.45  136.49  136.24  136.29  136.54
  135.87   135.9  135.92  135.94  136.09   135.9  135.73  135.21  136.42  134.61
  134.65  134.69   134.7   134.6  134.61  134.62  134.62  134.64  134.64  134.69
  134.71  135.36  135.19  135.28  135.23  135.39  135.41   135.5  135.63  135.58
  136.49  135.93  135.71  135.72  135.73  135.83  136.48  136.49  136.46  135.74
  135.62  135.55  135.44   135.4  133.89
  135.44  135.44  135.45  135.46  136.13  136.42  136.46  136.21  136.26  136.51
  135.84  135.87  135.89  135.91  136.06  135.87   135.7  135.18  136.39  125.66
  124.72   123.1  122.89  120.81  119.98  121.05  121.39   123.2  123.24  124.64
  125.28     127  127.53   127.7  127.96  128.71  129.52  130.41  133.02  135.55
  136.46   135.9  134.48   133.8  134.01   135.8  136.45  136.46  136.39  135.59
  135.45  135.42  135.38  134.51  133.87
  4490.2  4492.1    4556  4617.4  4647.5  4780.2  4797.9  4811.3  4822.2  4872.5
  4918.1  4920.1  4921.4  4922.9  4933.1  4936.4  4939.2  4948.1  4950.7  4981.6
  4984.3    4987  4987.9  4996.6  5000.1  5003.9  5005.1  5011.5  5011.6  5015.6
  5017.1  5067.3  5082.8  5087.8  5095.4  5117.3  5120.5    5124  5134.3  5144.3
  5147.9  5150.2    5156  5158.8  5160.1  5173.9    5189    5283  5323.4  5787.9
  5867.8  5909.7  5980.5  6009.8  6031.1
  135.47  135.83  135.69  135.55  136.16  136.45  136.49  136.24  136.29  136.54
  135.87   135.9  135.92  135.94  136.09   135.9  135.73  135.21  136.42  134.61
  134.65  134.69   134.7   134.6  134.61  134.62  134.62  134.64  134.64  134.69
  134.71  135.36  135.19  135.28  135.23  135.39  135.41   135.5  135.63  135.58
  136.49  135.93  135.71  135.72  135.73  135.83  136.48  136.49  136.46  135.74
  135.62  135.55  135.44   135.4   133.9
  135.47  135.47  135.48  135.49  136.16  136.45  136.49  136.24  136.29  136.54
  135.87   135.9  135.92  135.94  136.09   135.9  135.73  135.21  136.42  125.69
  124.75  123.13  122.92  120.84  120.01  121.08  121.42  123.23  123.27  124.67
  125.31  127.03  127.56  127.73  127.99  128.74  129.55  130.44  133.05  135.58
  136.49  135.93  134.51  133.83  134.04  135.83  136.48  136.49  136.42  135.62
  135.48  135.45  135.41  134.54   133.9
BR Coef= 1 , 0 , 0 ,1.25, 0 ,,,0.8,-1,2,0,
WSPro=,,,, 1 ,,,, 0 ,,,, 0 ,,,,-1 ,-1 ,-1 , 0 , 0 , 0 , 0 , 0
Culvert=2,7,7,85,0.024,0.2,1,8,1,123.1,5000,123,5000,Culvert #1  , 0 ,10
Culvert Bottom n=0.024
BR U #Sta/Elev= 55
  4490.2  135.44  4492.1  135.44    4556  135.45  4617.4  135.46  4647.5  136.13
  4780.2  136.42  4797.9  136.46  4811.3  136.21  4822.2  136.26  4872.5  136.51
  4918.1  135.84  4920.1  135.87  4921.4  135.89  4922.9  135.91  4933.1  136.06
  4936.4  135.87  4939.2   135.7  4948.1  135.18  4950.7  136.39  4981.6  125.66
  4984.3  124.72    4987   123.1  4987.9  122.89  4996.6  120.81  5000.1  119.98
  5003.9  121.05  5005.1  121.39  5011.5   123.2  5011.6  123.24  5015.6  124.64
  5017.1  125.28  5067.3     127  5082.8  127.53  5087.8   127.7  5095.4  127.96
  5117.3  128.71  5120.5  129.52    5124  130.41  5134.3  133.02  5144.3  135.55
  5147.9  136.46  5150.2   135.9    5156  134.48  5158.8   133.8  5160.1  134.01
  5173.9   135.8    5189  136.45    5283  136.46  5323.4  136.39  5787.9  135.59
  5867.8  135.45  5909.7  135.42  5980.5  135.38  6009.8  134.51  6031.1  133.87
BR U #Mann= 5
  4490.2      .2    4556      .1  4950.7     .04  5147.9      .1  5787.9      .2
BR U Banks=4950.7,5147.9
BR D #Sta/Elev= 55
  4490.2  135.47  4492.1  135.47    4556  135.48  4617.4  135.49  4647.5  136.16
  4780.2  136.45  4797.9  136.49  4811.3  136.24  4822.2  136.29  4872.5  136.54
  4918.1  135.87  4920.1   135.9  4921.4  135.92  4922.9  135.94  4933.1  136.09
  4936.4   135.9  4939.2  135.73  4948.1  135.21  4950.7  136.42  4981.6  125.69
  4984.3  124.75    4987  123.13  4987.9  122.92  4996.6  120.84  5000.1  120.01
  5003.9  121.08  5005.1  121.42  5011.5  123.23  5011.6  123.27  5015.6  124.67
  5017.1  125.31  5067.3  127.03  5082.8  127.56  5087.8  127.73  5095.4  127.99
  5117.3  128.74  5120.5  129.55    5124  130.44  5134.3  133.05  5144.3  135.58
  5147.9  136.49  5150.2  135.93    5156  134.51  5158.8  133.83  5160.1  134.04
  5173.9  135.83    5189  136.48    5283  136.49  5323.4  136.42  5787.9  135.62
  5867.8  135.48  5909.7  135.45  5980.5  135.41  6009.8  134.54  6031.1   133.9
BR D #Mann= 5
  4490.2      .2    4556      .1  4950.7     .04  5147.9      .1  5787.9      .2
BR D Banks=4950.7,5147.9
BC Design=,, 0 ,, 0 ,,,,,,
BC HTab HWMax=136.51
BC Use User HTab Curves=0
BC User HTab FreeFlow(D)= 0

Type RM Length L Ch R = 1 ,37368.1 ,561.6,580.7,367.9
BEGIN DESCRIPTION:
Cross Section 37368.1-Interpolated
END DESCRIPTION:
XS GIS Cut Line= 6
       2990179.5     13854480.28      2989902.95     13853973.78
      2989761.08     13853776.93      2989714.96     13853534.03
      2989159.38      13853282.9      2989105.55     13853205.24
#Sta/Elev= 30
  4279.8   136.1  4280.6  136.08  4311.2  135.55  4346.2  133.73  4390.4  132.51
  4399.5  131.57  4405.1  131.33  4436.4  131.19  4534.1  133.98  4604.6  134.44
  4622.6  134.91  4780.7  135.11  4788.4     135    4812  133.84  4843.3  134.12
  4870.5  134.77  4919.2  133.94  4963.6  133.71  4982.5  124.41  4989.7  121.33
  5002.2  120.02  5012.2  122.87  5017.3  123.48  5017.5  124.32  5052.3  134.54
  5100.1  135.41  5147.5  135.81  5376.3  136.34  5731.9  135.89  6051.4  135.41
#Mann= 6 , 1 , 0
  4279.8      .2       0  4280.6     .08       0  4963.6     .04       0
  5052.3     .08       0  5376.3      .1       0  5731.9      .2       0
#XS Ineff= 2 , 0
       0  4985.5  134.57    5014       0  134.64
Permanent Ineff=
       F       F
Bank Sta=4963.6,5052.3
XS Rating Curve= 0 ,0
Exp/Cntr=0.5,0.3

River Reach=T101-13-00      ,1
Reach XY= 30
      2986465.67      13858672.2      2986620.28      13858679.8
      2986657.81      13857617.2      2986662.21      13857518.5
      2986672.61      13857455.2      2986994.31      13857039.1
      2987223.22      13856674.7      2987287.13      13856587.5
      2987452.05      13856440.9      2987806.36      13855934.9
       2987852.6      13855850.4      2988698.38      13855879.2
      2988895.71      13855890.6      2989097.58      13855893.6
      2989297.63      13855907.4        2989644.      13855918.3
      2989723.21      13855906.6      2989753.24      13855881.9
      2989769.76      13855860.1      2989779.43      13855762.1
  2989800.35544213855123.1310623  2989789.95115913854917.3574666
 2989811.915756313854732.3924367 2989806.135599113854474.5974263
 2989824.632102113854360.1503141  2989826.94416513854316.2211195
 2989825.788133613854228.3627303 2989816.167176413854142.7747437
 2989838.976706413853941.1000197 2989840.500062613853814.9998033

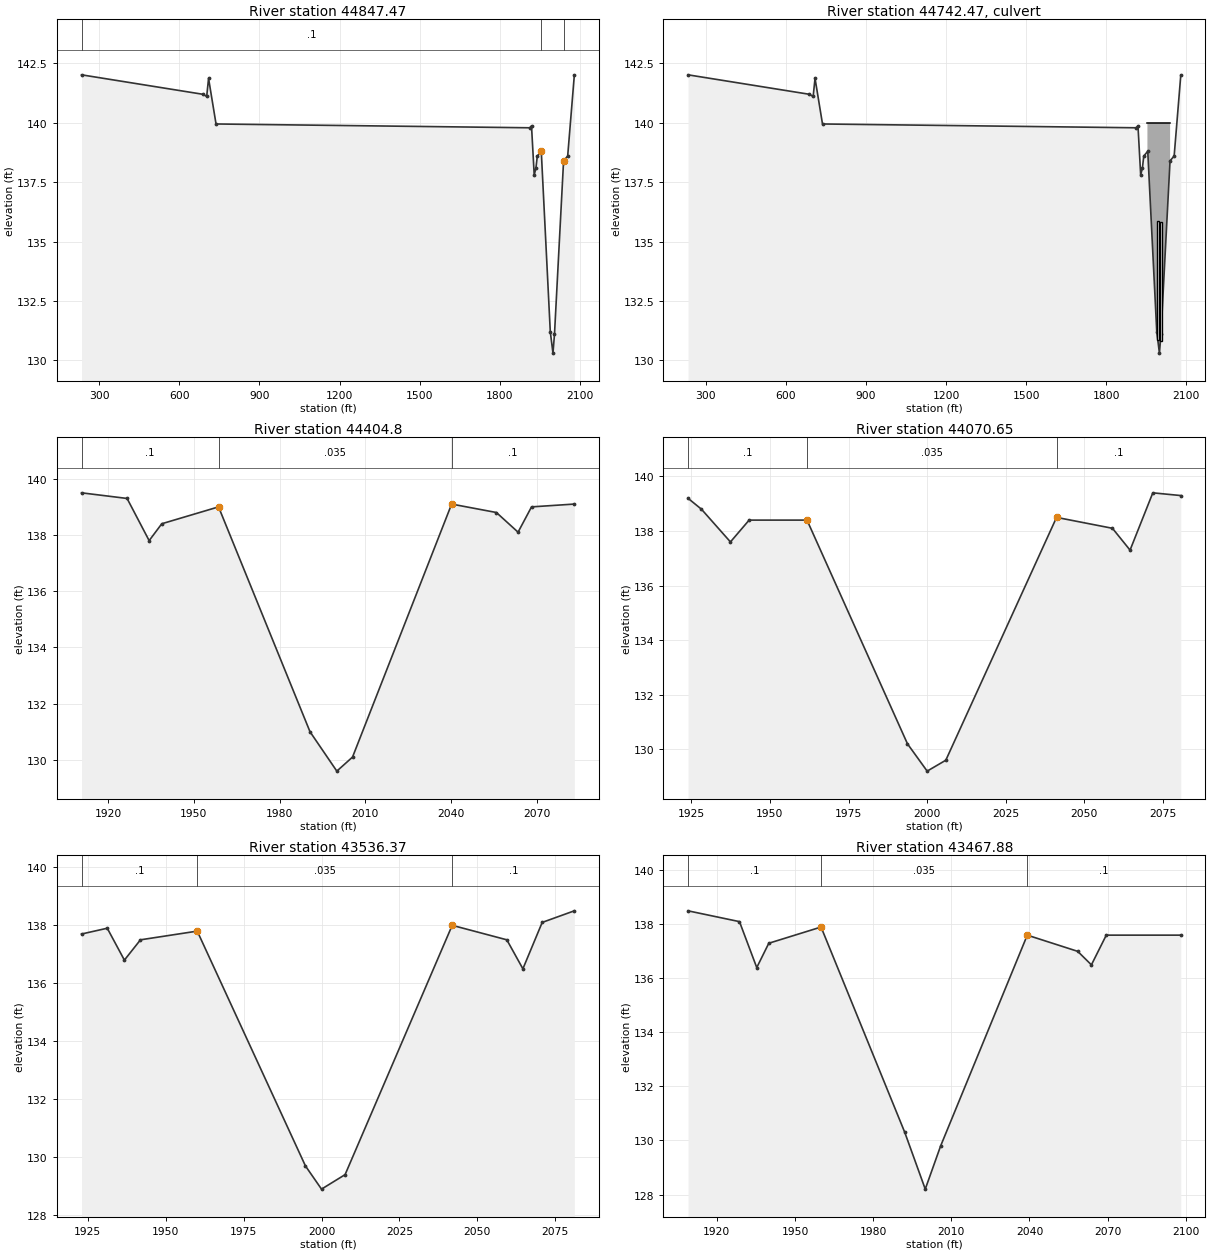
Type RM Length L Ch R = 1 ,44847.47,578.77,442.67,362.86
BEGIN DESCRIPTION:
Upstream of Mason Road
END DESCRIPTION:
XS GIS Cut Line= 4
 2986446.768882813860446.2887218      2986469.42       13858750.
       2986471.2      13858616.7 2986471.531533913858591.8722116
#Sta/Elev= 17
   233.3  142.02   688.3   141.2   702.3  141.11   709.3  141.87   737.3  139.95
  1912.6  139.79  1919.6  139.87 1929.74   137.8 1936.26   138.1 1941.33   138.6
  1956.2   138.8 1989.97   131.2    2000   130.3 2005.74   131.1 2039.79   138.4
 2055.17   138.6    2080     142
#Mann= 3 , 0 , 0
   233.3      .1       0  1956.2    .035       0 2039.79      .1       0
Bank Sta=1956.2,2039.79
XS Rating Curve= 0 ,0
Exp/Cntr=0.3,0.1

Type RM Length L Ch R = 2 ,44742.47,,,
BEGIN DESCRIPTION:
Mason Road
END DESCRIPTION:
Bridge Culvert--1,0,-1,-1, 0
Deck Dist Width WeirC Skew NumUp NumDn MinLoCord MaxHiCord MaxSubmerge Is_Ogee
105,226,2.6,0, 2, 2, , , 0.95, 0, 0,0,,
    1955    2040
     140     140
     130     130
    1955    2040
     140     140
     130     130
BR Coef=-1 , 0 , 0 ,, 0 ,,,0.8,-1,,0,
WSPro=,,,, 1 ,,,, 0 ,,,, 0 ,,,,-1 ,-1 ,-1 , 0 , 0 , 0 , 0 , 0
Culvert=2,5,8,226.2,0.015,1,1,8,1,130.87,1994,130.74,1994,Culvert #1  , 0 ,105
Culvert Bottom n=0.015
Culvert=2,5,8,226.2,0.015,1,1,8,1,130.83,2006,130.69,2006,Culvert #2  , 0 ,105
Culvert Bottom n=0.015
BC Design=,, 0 ,, 0 ,,,,,,
BC HTab HWMax=142.02
BC Use User HTab Curves=0
BC User HTab FreeFlow(D)= 0

Type RM Length L Ch R = 1 ,44404.8 ,334.15,334.15,334.15
BEGIN DESCRIPTION:
Downstream of Mason Road
END DESCRIPTION:
XS GIS Cut Line= 2
      2986718.59      13858389.8      2986549.03      13858386.8
#Sta/Elev= 13
 1910.72   139.5 1926.64   139.3 1934.36   137.8 1938.78   138.4 1958.63     139
 1990.62     131    2000   129.6 2005.49   130.1 2040.15   139.1  2055.8   138.8
 2063.38   138.1 2068.09     139 2083.05   139.1
#Mann= 3 , 0 , 0
 1910.72      .1       0 1958.63    .035       0 2040.15      .1       0
Bank Sta=1958.63,2040.15
XS Rating Curve= 0 ,0
Exp/Cntr=0.3,0.1

Type RM Length L Ch R = 1 ,44070.65,534.28,534.28,534.28
BEGIN DESCRIPTION:
Cross Section 44070.65
END DESCRIPTION:
XS GIS Cut Line= 2
      2986719.08      13858057.5      2986562.11      13858053.6
#Sta/Elev= 13
 1923.95   139.2 1928.22   138.8 1937.44   137.6 1943.38   138.4 1961.79   138.4
 1993.74   130.2    2000   129.2 2005.93   129.6 2041.15   138.5 2058.92   138.1
 2064.52   137.3 2071.76   139.4 2080.65   139.3
#Mann= 3 , 0 , 0
 1923.95      .1       0 1961.79    .035       0 2041.15      .1       0
Bank Sta=1961.79,2041.15
XS Rating Curve= 0 ,0
Exp/Cntr=0.3,0.1

Type RM Length L Ch R = 1 ,43536.37,46.07,68.49,97.74
BEGIN DESCRIPTION:
Cross Section 43536.37
END DESCRIPTION:
XS GIS Cut Line= 2
      2986739.54      13857515.4      2986581.44      13857515.5
#Sta/Elev= 13
 1923.05   137.7 1931.29   137.9 1936.79   136.8 1941.94   137.5 1960.15   137.8
 1994.85   129.7    2000   128.9 2007.56   129.4 2041.91     138 2059.43   137.5
 2064.58   136.5 2070.77   138.1 2081.07   138.5
#Mann= 3 , 0 , 0
 1923.05      .1       0 1960.15    .035       0 2041.91      .1       0
Bank Sta=1960.15,2041.91
XS Rating Curve= 0 ,0
Exp/Cntr=0.3,0.1

Type RM Length L Ch R = 1 ,43467.88,413.4,413.4,413.4
BEGIN DESCRIPTION:
Cross Section 43467.88
END DESCRIPTION:
XS GIS Cut Line= 2
      2986752.99      13857499.5      2986596.94      13857393.2
#Sta/Elev= 13
 1908.95   138.5  1928.7   138.1 1935.33   136.4 1939.95   137.3 1960.01   137.9
 1992.14   130.3    2000   128.2 2005.91   129.8 2039.16   137.6 2058.52     137
 2063.77   136.5 2069.48   137.6 2098.07   137.6
#Mann= 3 , 0 , 0
 1908.95      .1       0 1960.01    .035       0 2039.16      .1       0
Bank Sta=1960.01,2039.16
XS Rating Curve= 0 ,0
Exp/Cntr=0.3,0.1