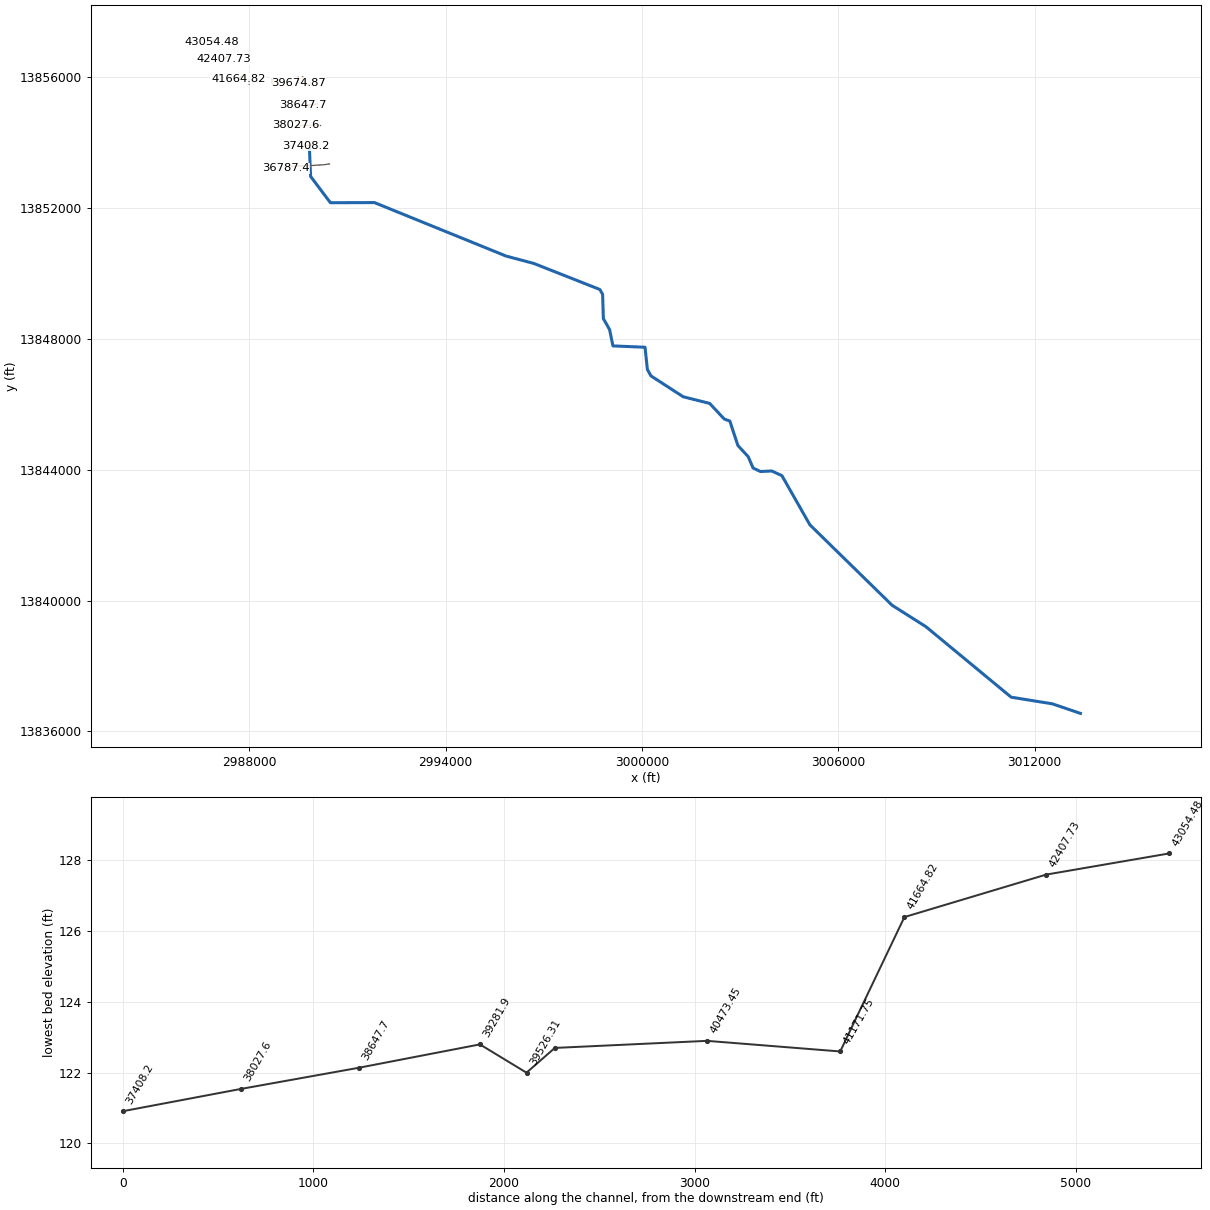
HEC-RAS study T101-00-00.PRJ: T101-00-00

--- T101-00-00.g01 (geometry) --- (continued)

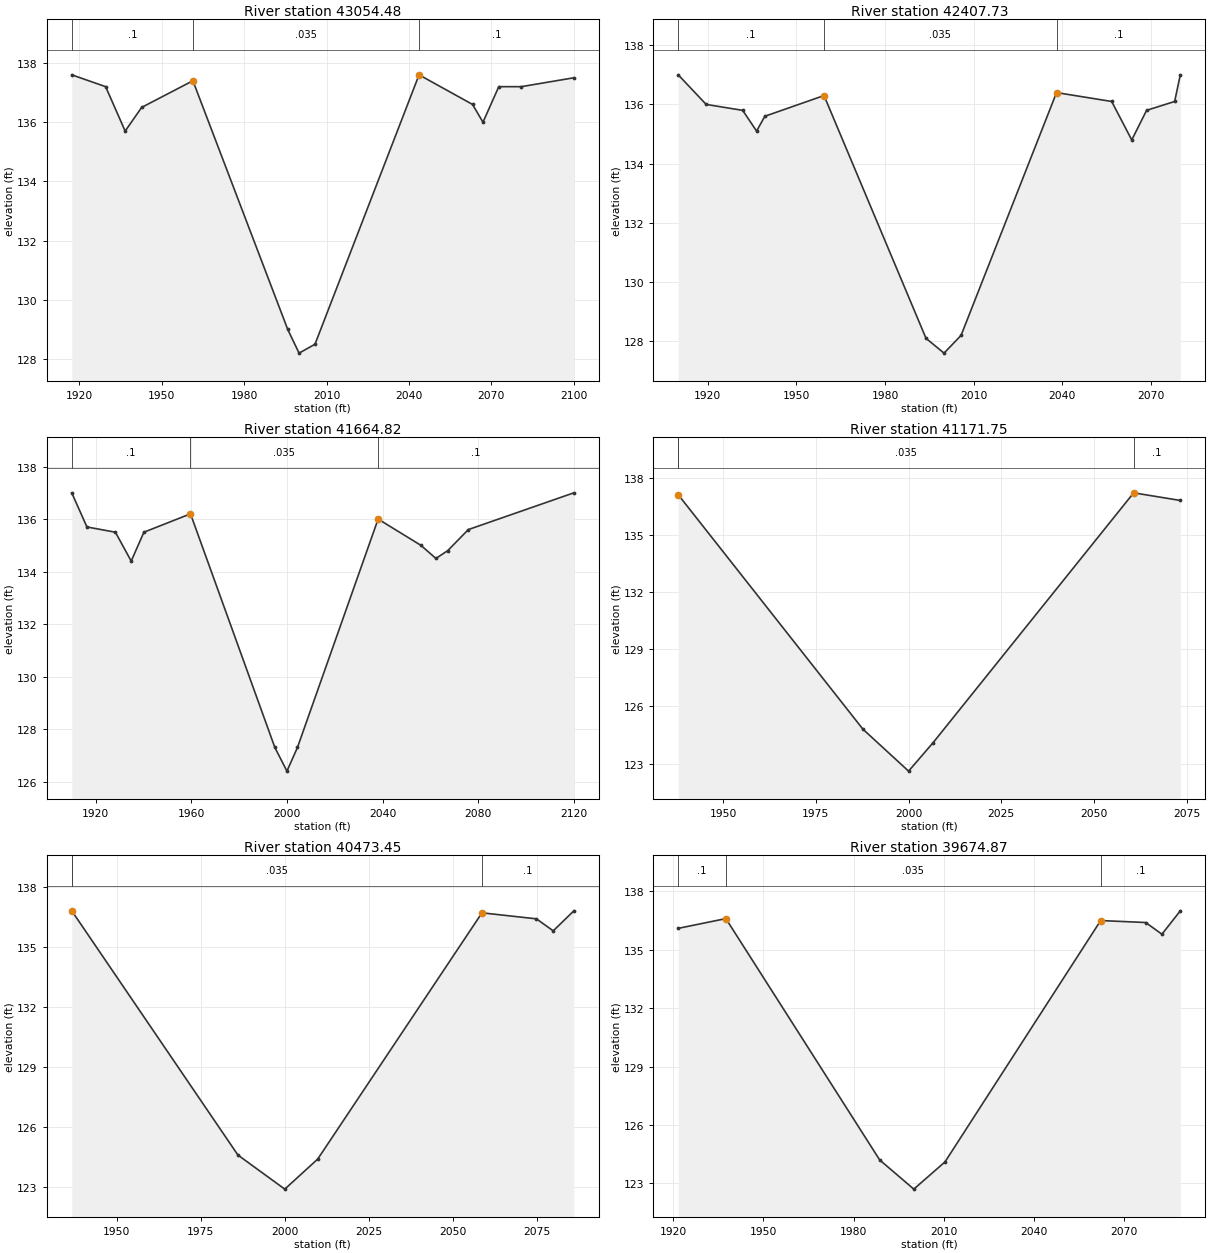
Type RM Length L Ch R = 1 ,43054.48,646.75,646.75,646.75
BEGIN DESCRIPTION:
Cross Section 43054.48
END DESCRIPTION:
XS GIS Cut Line= 3
      2986997.89       13857179.      2986866.47      13857076.7
 2986851.350790113857064.9308996
#Sta/Elev= 14
 1917.28   137.6  1929.6   137.2 1936.71   135.7 1942.72   136.5 1961.36   137.4
 1995.88     129    2000   128.2 2005.79   128.5 2043.67   137.6 2063.13   136.6
 2066.93     136 2072.69   137.2 2080.84   137.2    2100   137.5
#Mann= 3 , 0 , 0
 1917.28      .1       0 1961.36    .035       0 2043.67      .1       0
Bank Sta=1961.36,2043.67
XS Rating Curve= 0 ,0
Exp/Cntr=0.3,0.1

Type RM Length L Ch R = 1 ,42407.73,742.91,742.91,742.91
BEGIN DESCRIPTION:
Cross Section 42407.73
END DESCRIPTION:
XS GIS Cut Line= 4
 2987358.405916813856642.3858523        2987351.      13856636.5
      2987226.81      13856537.8 2987225.306951313856536.6054521
#Sta/Elev= 15
    1910     137 1919.46     136 1931.82   135.8 1936.53   135.1 1939.32   135.6
 1959.36   136.3  1993.9   128.1    2000   127.6 2005.77   128.2 2038.09   136.4
 2056.76   136.1 2063.56   134.8 2068.58   135.8 2078.08   136.1    2080     137
#Mann= 3 , 0 , 0
    1910      .1       0 1959.36    .035       0 2038.09      .1       0
Bank Sta=1959.36,2038.09
XS Rating Curve= 0 ,0
Exp/Cntr=0.3,0.1

Type RM Length L Ch R = 1 ,41664.82,273.1,336.78,383.29
BEGIN DESCRIPTION:
Cross Section 41664.82
END DESCRIPTION:
XS GIS Cut Line= 4
 2987825.256481513856064.9979602      2987820.18      13856061.2
      2987698.68      13855970.3 2987663.336694513855943.8579715
#Sta/Elev= 15
    1910     137 1916.34   135.7 1928.25   135.5 1934.86   134.4 1940.17   135.5
 1959.66   136.2 1994.95   127.3    2000   126.4 2004.39   127.3 2038.14     136
 2056.04     135 2062.31   134.5 2067.27   134.8 2075.86   135.6    2120     137
#Mann= 3 , 0 , 0
    1910      .1       0 1959.66    .035       0 2038.14      .1       0
Bank Sta=1959.66,2038.14
XS Rating Curve= 0 ,0
Exp/Cntr=0.3,0.1

Type RM Length L Ch R = 1 ,41171.75,698.3,698.3,698.3
BEGIN DESCRIPTION:
Cross Section 41171.75
END DESCRIPTION:
XS GIS Cut Line= 2
  2987996.16459813855922.1116257  2987997.77750813855781.4689902
#Sta/Elev= 6
 1937.88   137.1 1987.69   124.8    2000   122.6 2006.64   124.1  2060.7   137.2
 2073.28   136.8
#Mann= 3 , 0 , 0
 1937.88      .1       0 1937.88    .035       0  2060.7      .1       0
Bank Sta=1937.88,2060.7
XS Rating Curve= 0 ,0
Exp/Cntr=0.3,0.1

Type RM Length L Ch R = 1 ,40473.45,798.59,798.59,798.59
BEGIN DESCRIPTION:
Cross Section 40473.45
END DESCRIPTION:
XS GIS Cut Line= 2
 2988695.259343613855942.3574638      2988698.76      13855790.1
#Sta/Elev= 8
 1936.57   136.8 1986.06   124.6    2000   122.9  2009.8   124.4 2058.73   136.7
 2074.94   136.4 2079.94   135.8 2086.08   136.8
#Mann= 3 , 0 , 0
 1936.57      .1       0 1936.57    .035       0 2058.73      .1       0
Bank Sta=1936.57,2058.73
XS Rating Curve= 0 ,0
Exp/Cntr=0.3,0.1

Type RM Length L Ch R = 1 ,39674.87,148.56,148.56,148.56
BEGIN DESCRIPTION:
Cross Section 39674.87
END DESCRIPTION:
XS GIS Cut Line= 2
 2989495.510945213855989.1074308      2989501.31       13855821.
#Sta/Elev= 9
  1921.7   136.1 1937.53   136.6 1988.66   124.2    2000   122.7 2010.37   124.1
 2062.11   136.5 2077.06   136.4 2082.47   135.8 2088.58     137
#Mann= 3 , 0 , 0
  1921.7      .1       0 1937.53    .035       0 2062.11      .1       0
Bank Sta=1937.53,2062.11
XS Rating Curve= 0 ,0
Exp/Cntr=0.3,0.1

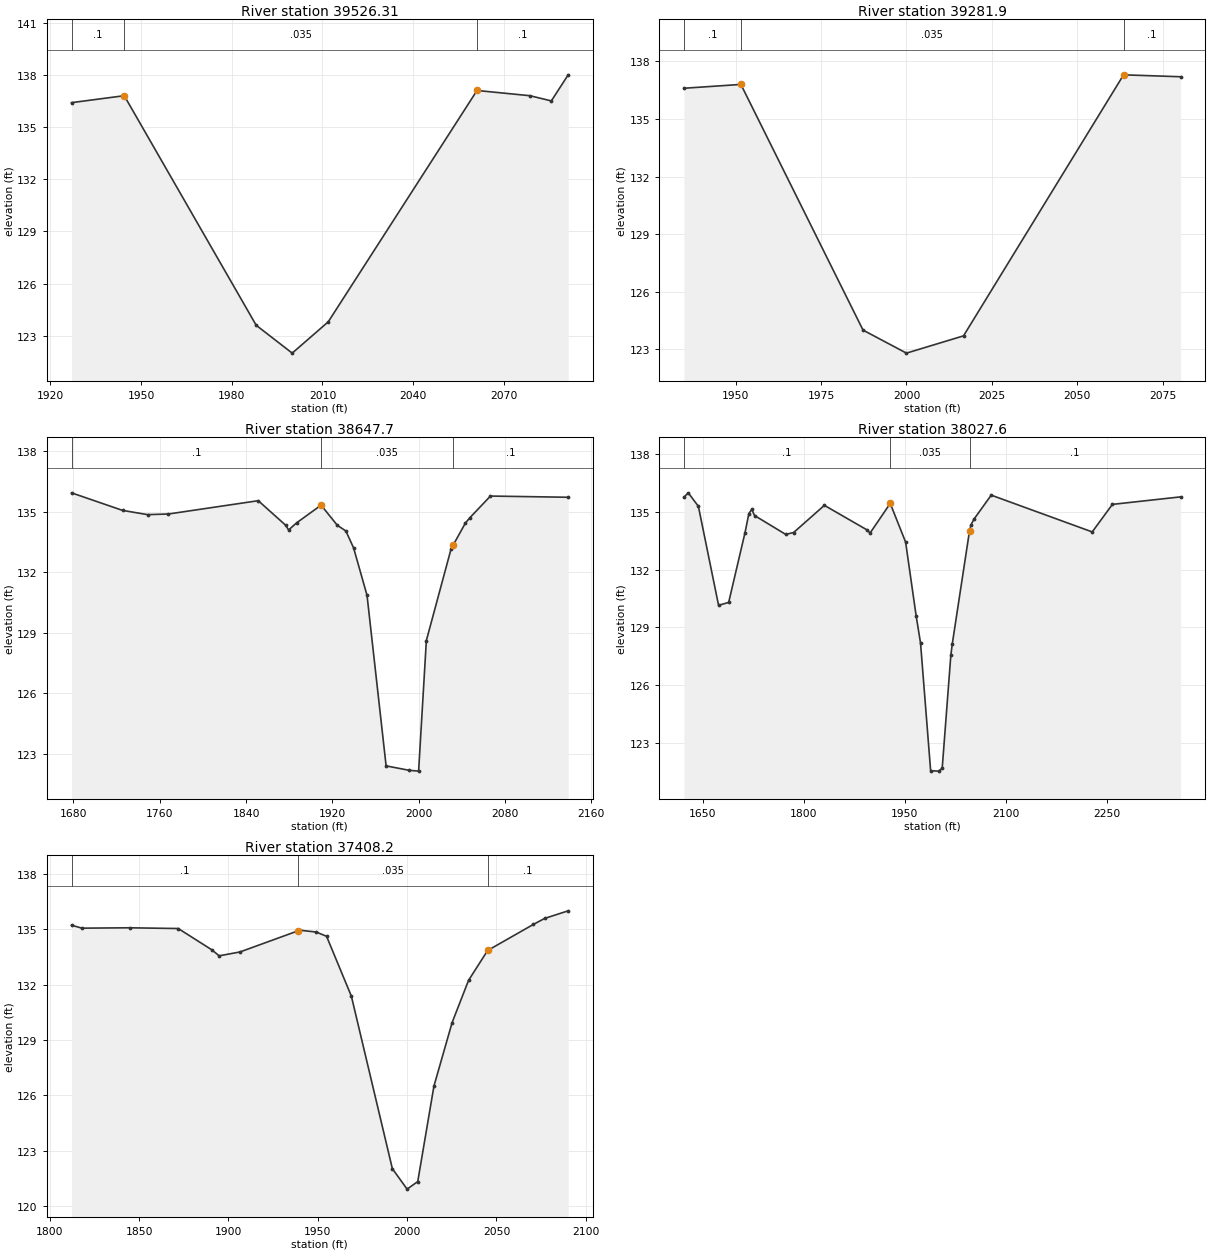
Type RM Length L Ch R = 1 ,39526.31,322.66,244.41,144.52
BEGIN DESCRIPTION:
Cross Section 39526.31
END DESCRIPTION:
XS GIS Cut Line= 2
      2989631.35      13856006.6      2989637.19      13855823.8
#Sta/Elev= 9
 1927.01   136.4 1944.45   136.8  1988.1   123.6    2000     122 2011.92   123.8
 2061.12   137.1 2078.59   136.8  2085.7   136.5 2091.27     138
#Mann= 3 , 0 , 0
 1927.01      .1       0 1944.45    .035       0 2061.12      .1       0
Bank Sta=1944.45,2061.12
XS Rating Curve= 0 ,0
Exp/Cntr=0.3,0.1

Type RM Length L Ch R = 1 ,39281.9 ,634.2,634.2,634.2
BEGIN DESCRIPTION:
Cross Section 39281.9
END DESCRIPTION:
XS GIS Cut Line= 2
      2989883.67      13855774.4      2989738.0713855772.4271874
#Sta/Elev= 7
 1934.87   136.6 1951.55   136.8 1987.29     124    2000   122.8  2016.7   123.7
 2063.54   137.3 2080.22   137.2
#Mann= 3 , 0 , 0
 1934.87      .1       0 1951.55    .035       0 2063.54      .1       0
Bank Sta=1951.55,2063.54
XS Rating Curve= 0 ,0
Exp/Cntr=0.3,0.1

Type RM Length L Ch R = 1 ,38647.7 ,620.1,620.1,620.1
BEGIN DESCRIPTION:
Cross Section 38647.7
END DESCRIPTION:
XS GIS Cut Line= 2
 2990082.849807613855171.0678142 2989624.464215513855127.0743208
#Sta/Elev= 23
 1678.17  135.93 1725.49  135.06 1748.64  134.85 1767.95  134.88 1851.31  135.54
 1876.83  134.32 1879.45  134.09 1887.08  134.45 1909.59  135.32 1924.63  134.32
 1932.56  134.04 1939.72   133.2 1952.17  130.85 1969.86   122.4 1991.31  122.18
    2000  122.14 2007.17  128.61 2030.14  133.16  2032.1 133.348 2043.36  134.43
 2047.41  134.69  2066.6  135.77 2138.67  135.71
#Mann= 3 , 0 , 0
 1678.17      .1       0 1909.59    .035       0  2032.1      .1       0
Bank Sta=1909.59,2032.1
XS Rating Curve= 0 ,0
Exp/Cntr=0.3,0.1

Type RM Length L Ch R = 1 ,38027.6 ,619.4,619.4,619.4
BEGIN DESCRIPTION:
Cross Section 38027.6
END DESCRIPTION:
XS GIS Cut Line= 2
 2990173.999995113854525.9963437 2989436.225595513854525.9963437
#Sta/Elev= 30
 1621.75  135.76 1628.26  135.99 1643.26  135.29 1673.26  130.15 1688.26   130.3
 1712.59  133.93 1718.26  134.91  1722.5  135.13 1726.75  134.81 1773.05  133.83
 1784.76  133.93 1830.42  135.34 1894.01  134.06 1898.26   133.9 1928.26  135.44
 1951.09  133.43 1966.75   129.6 1973.26  128.19 1988.26  121.56    2000  121.54
 2005.42  121.68 2018.26  127.55 2020.42  128.15 2046.09  134.03 2048.26  134.33
 2052.59  134.62 2078.26  135.87 2228.26  133.96 2258.26  135.39 2359.53  135.78
#Mann= 3 , 0 , 0
 1621.75      .1       0 1928.26    .035       0 2046.09      .1       0
Bank Sta=1928.26,2046.09
XS Rating Curve= 0 ,0
Exp/Cntr=0.3,0.1

Type RM Length L Ch R = 1 ,37408.2 ,,,
BEGIN DESCRIPTION:
Cross Section 37408.2
END DESCRIPTION:
XS GIS Cut Line= 4
 2990009.998375813853919.5032451 2990006.104703313853919.2807478
 2990004.157806113853919.1694957 2989732.500020813853903.6460746
#Sta/Elev= 22
 1812.19  135.22 1818.04  135.06 1844.65  135.08 1871.94  135.04 1890.65  133.89
 1894.83  133.56 1906.48  133.77  1939.1  134.92 1939.91  134.95 1949.11  134.85
 1954.93  134.62 1968.82  131.37 1991.75  122.02    2000  120.91 2005.96  121.32
 2015.03   126.5 2025.19  129.94 2034.39  132.23 2045.08  133.85  2070.6  135.26
 2077.02  135.59 2090.15     136
#Mann= 3 , 0 , 0
 1812.19      .1       0  1939.1    .035       0 2045.08      .1       0
Bank Sta=1939.1,2045.08
XS Rating Curve= 0 ,0
Exp/Cntr=0.3,0.1

River Reach=T101-00-00      ,T101-00-00_Main
Reach XY= 30
 2989840.500062613853814.9998033      2989876.75       13852961.
      2990481.25       13852156.      2991827.75       13852160.
      2995852.75       13850525.        2996699.       13850300.
      2998715.75       13849504.      2998799.25       13849356.
        2998822.       13848615.      2999012.25       13848280.
        2999114.       13847781.      3000094.25       13847740.
       3000167.5       13847059.      3000274.25       13846866.
      3001260.75       13846227.        3002070.       13846024.
      3002515.25       13845547.      3002686.53     13845485.04
        3002933.       13844737.       3003249.5       13844394.
      3003394.75       13844052.        3003620.       13843943.
      3003969.25       13843959.      3004278.75       13843815.
      3005132.25       13842314.      3007643.75       13839857.
      3008678.25       13839201.      3011283.69     13837046.69
      3012536.05     13836845.22      3013399.16     13836552.51

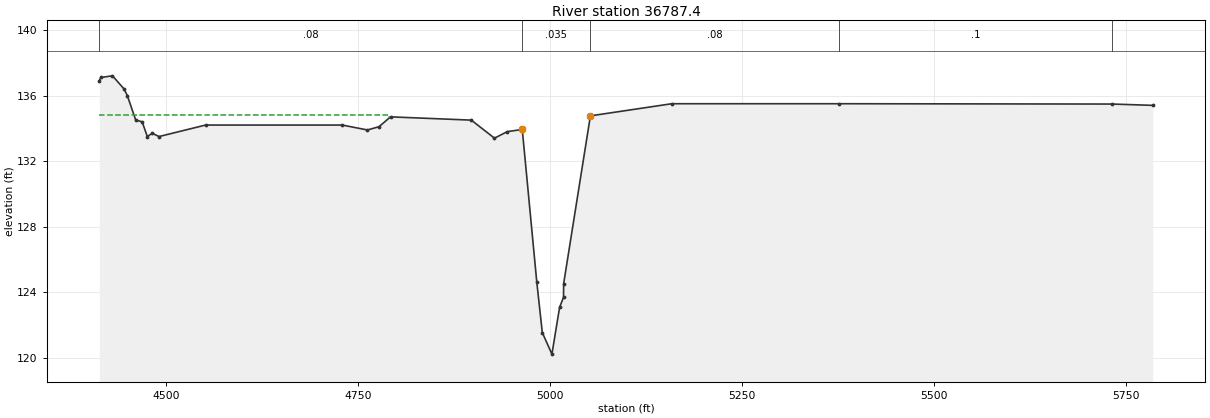
Type RM Length L Ch R = 1 ,36787.4 ,74.7,74.7,74.7
BEGIN DESCRIPTION:
Cross Section 36787.4-Interpolated
END DESCRIPTION:
XS GIS Cut Line= 6
      2990451.43     13853341.41      2990284.57     13853317.58
      2989983.86     13853297.41      2989864.67     13853290.07
      2989151.39     13853260.73      2989111.65     13853205.37
#Sta/Elev= 30
    4413   136.9  4414.9   137.1  4430.1   137.2  4445.2   136.4  4449.4     136
  4460.4   134.5  4468.7   134.4  4475.5   133.5  4481.9   133.7  4490.7   133.5
  4551.3   134.2  4729.3   134.2    4762   133.9  4777.1   134.1  4792.1   134.7
  4897.3   134.5  4927.4   133.4  4944.1   133.8  4963.6  133.93  4982.5  124.63
  4989.7  121.55  5002.2  120.24  5012.2  123.09  5017.3   123.7  5017.5  124.54
  5052.3  134.76  5158.3   135.5  5376.3   135.5  5731.9  135.48  5784.4   135.4
#Mann= 5 , 1 , 0
    4413     .08       0  4963.6    .035       0  5052.3     .08       0
  5376.3      .1       0  5731.9      .2       0
#XS Ineff= 2 , 0
       0    4790   134.8               0
Permanent Ineff=
       F       F
Bank Sta=4963.6,5052.3
XS Rating Curve= 0 ,0
Exp/Cntr=0.5,0.3