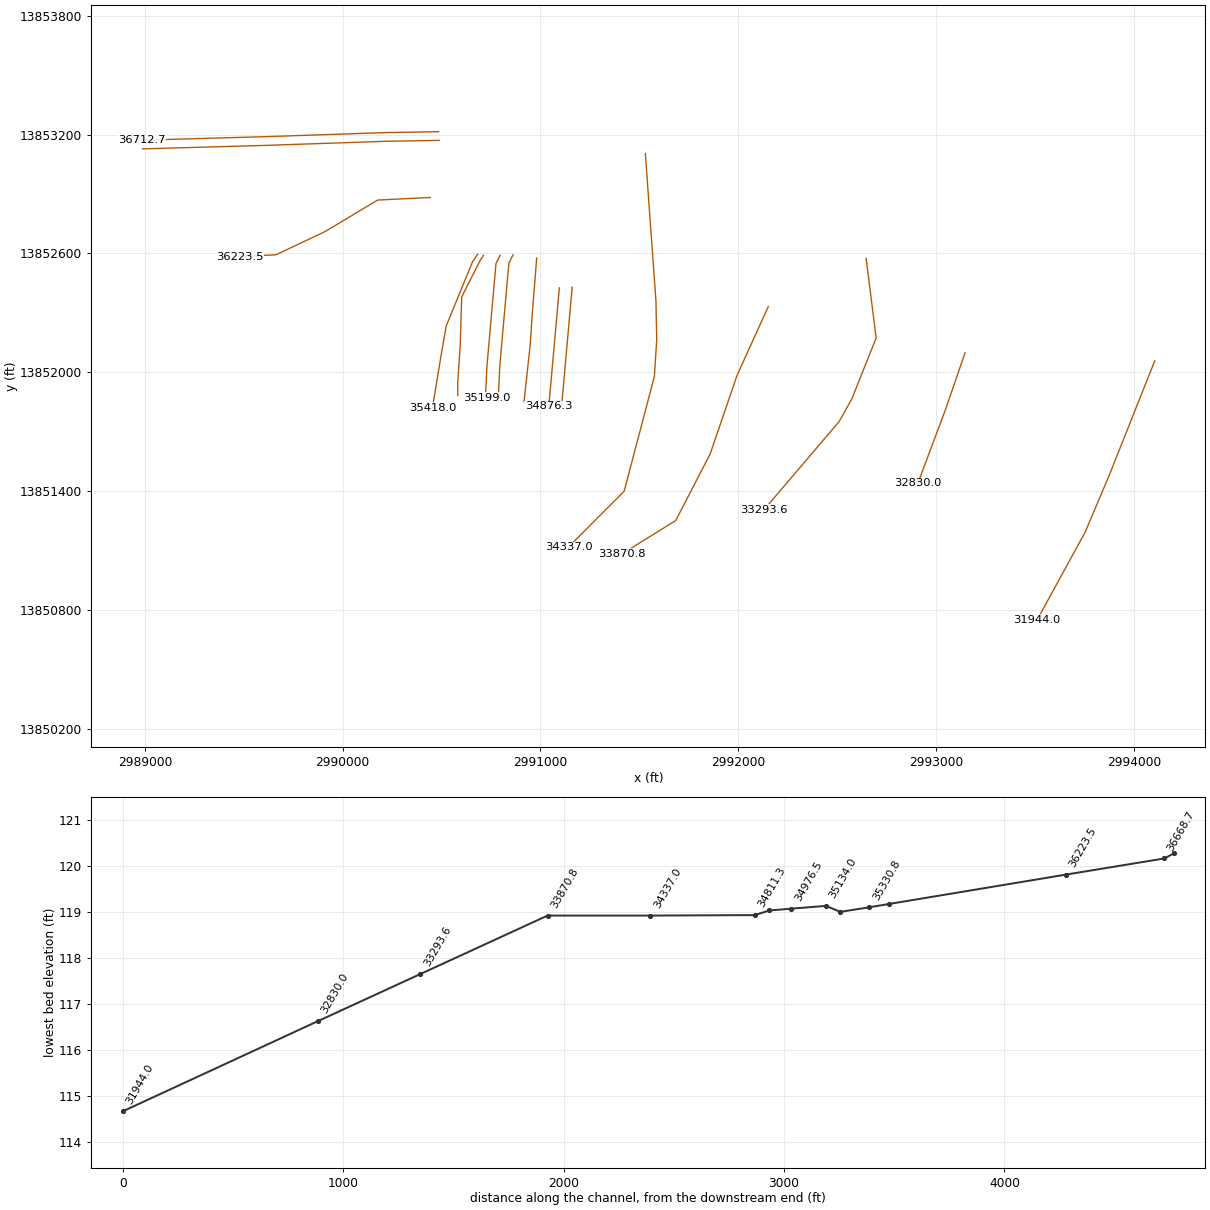
HEC-RAS study T101-00-00.PRJ: T101-00-00

--- T101-00-00.g01 (geometry) --- (continued)

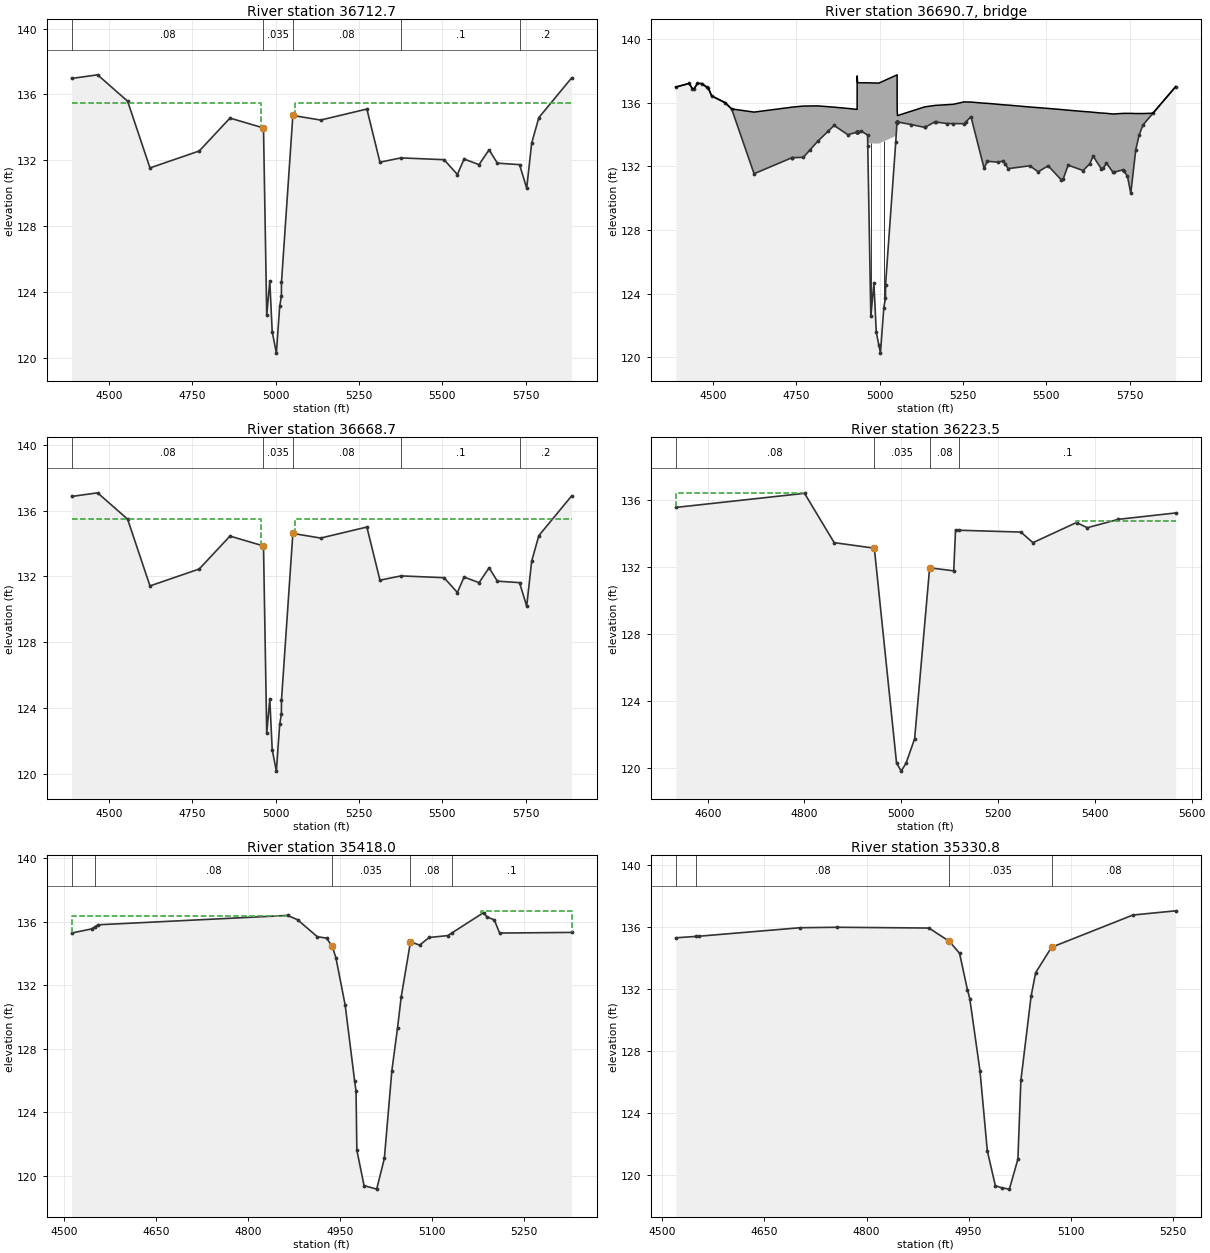
Type RM Length L Ch R = 1 ,36712.7 ,44,44,44
BEGIN DESCRIPTION:
Upstream Section of Bridge/Culvert/Weir
END DESCRIPTION:
XS GIS Cut Line= 4
      2990485.35     13853214.55      2990209.95     13853209.72
      2989616.69     13853189.57      2988985.98     13853171.71
#Sta/Elev= 30
    4388  136.97  4465.8  137.19  4555.8  135.59    4623  131.53  4770.8  132.56
    4863  134.56  4963.6  133.96  4973.3  122.58  4982.5  124.66  4989.7  121.58
  5002.2  120.27  5012.2  123.12  5017.3  123.73  5017.5  124.57  5051.7  134.72
  5135.1  134.44  5273.8  135.11    5313  131.88  5376.3  132.14  5505.4  132.03
  5545.4  131.13  5565.4  132.07  5610.4  131.73  5640.4  132.63  5665.4  131.82
  5731.9  131.73  5753.3   130.3  5768.3  133.04  5789.8  134.59    5888     137
#Mann= 5 , 1 , 0
    4388     .08       0  4963.6    .035       0  5051.7     .08       0
  5376.3      .1       0  5731.9      .2       0
#XS Ineff= 2 , 0
       0    4955   135.5    5058       0   135.5
Permanent Ineff=
       F       F
Bank Sta=4963.6,5051.7
XS Rating Curve= 0 ,0
Exp/Cntr=0.5,0.3

Type RM Length L Ch R = 3 ,36690.7 ,,,
BEGIN DESCRIPTION:
FRANZ ROAD
Structure ID: T01-25
END DESCRIPTION:
Bridge Culvert--1,0,-1,-1, 0
Deck Dist Width WeirC Skew NumUp NumDn MinLoCord MaxHiCord MaxSubmerge Is_Ogee
10,24,2.6,0, 60, 60, , , 0.95, 0, 1,1,,
    4388    4428    4438    4443    4453  4465.8  4485.8  4495.8  4535.8  4555.8
    4623  4736.7  4770.8  4814.2    4863  4904.4 4932.19  4932.3  4932.5  4933.4
  4944.4  4963.6  4964.1  4997.3    5048    5052  5052.2  5052.3  5053.2  5135.1
  5166.1  5220.5  5253.2  5273.8    5313    5323  5355.4  5370.4  5385.4  5450.4
  5475.4  5505.4  5545.4  5550.4  5565.4  5610.4  5630.4  5640.4  5665.4  5670.4
  5680.4  5700.4  5730.4  5743.3  5753.3  5768.3  5778.3  5789.8  5819.6    5888
  136.97   137.2  136.87  136.86   137.2  137.19   136.9  136.42     136   135.6
   135.4  135.71  135.78  135.79  135.71  135.63  135.57  137.67  137.67  137.25
  137.24  137.24  137.24  137.22   137.7  137.74  137.69  135.59  135.18  135.73
  135.82  135.89  136.04  136.03  135.96  135.95  135.89  135.86  135.84  135.72
  135.68  135.63  135.56  135.55  135.52  135.44  135.41  135.39  135.34  135.34
  135.32  135.28  135.32  135.32  135.32  135.31  135.31  135.31  135.33     137
  136.97   137.2  136.87  136.86   137.2  137.19  136.89  136.41  135.99  135.59
  131.53  132.54  132.56  133.57  134.56  133.98  134.14  134.14  134.14  134.15
  134.21  133.96  133.44  133.42   133.9  134.79  134.79  134.79  134.78  134.44
  134.79  134.68  134.67  135.11  131.88  132.31  132.26  132.33  131.85  132.03
  131.65  132.03  131.13  131.19  132.07  131.73  132.16  132.63  131.82  131.86
  132.19  131.61  131.78  131.37   130.3  133.04  133.95  134.59  135.32     137
    4388    4428    4438    4443    4453  4465.8  4485.8  4495.8  4535.8  4555.8
    4623  4736.7  4770.8  4814.2    4863  4904.4 4932.19  4932.3  4932.5  4933.4
  4944.4  4963.6  4964.1  4997.3    5048    5052  5052.2  5052.3  5053.2  5135.1
  5166.1  5220.5  5253.2  5273.8    5313    5323  5355.4  5370.4  5385.4  5450.4
  5475.4  5505.4  5545.4  5550.4  5565.4  5610.4  5630.4  5640.4  5665.4  5670.4
  5680.4  5700.4  5730.4  5743.3  5753.3  5768.3  5778.3  5789.8  5819.6    5888
  136.97   137.2  136.87  136.86   137.2  137.19   136.9  136.42     136   135.6
   135.4  135.71  135.78  135.79  135.71  135.63  135.57  137.67  137.67  137.25
  137.24  137.24  137.24  137.22   137.7  137.74  137.69  135.59  135.18  135.73
  135.82  135.89  136.04  136.03  135.96  135.95  135.89  135.86  135.84  135.72
  135.68  135.63  135.56  135.55  135.52  135.44  135.41  135.39  135.34  135.34
  135.32  135.28  135.32  135.32  135.32  135.31  135.31  135.31  135.33     137
  136.87   137.1  136.77  136.76   137.1  137.09  136.79  136.31  135.89  135.49
  131.43  132.44  132.46  133.47  134.46  133.88  134.04  134.04  134.04  134.05
  134.11  133.86  133.34  133.32   133.8  134.69  134.69  134.69  134.68  134.34
  134.69  134.58  134.57  135.01  131.78  132.21  132.16  132.23  131.75  131.93
  131.55  131.93  131.03  131.09  131.97  131.63  132.06  132.53  131.72  131.76
  132.09  131.51  131.68  131.27   130.2  132.94  133.85  134.49  135.22   136.9
Pier Skew, UpSta & Num, DnSta & Num=  ,4973.3, 2 ,4973.3, 2 , 0 , 0 , 0 ,,
     1.4     1.4
  121.74  134.43
     1.4     1.4
  121.64  134.33
Pier Skew, UpSta & Num, DnSta & Num=  ,5012.2, 2 ,5012.2, 2 , 0 , 0 , 0 ,,
     1.4     1.4
  121.92  134.57
     1.4     1.4
  121.82  134.47
BR Coef= 1 , 1 , 0 ,1.25, 0 ,,,0.8,0,2,0,
WSPro=,,,, 1 ,,,, 0 ,,,, 0 ,,,,-1 ,-1 ,-1 , 0 , 0 , 0 , 0 , 0
BR U #Sta/Elev= 88
    4388  136.97    4428   137.2    4438  136.87    4443  136.86    4453   137.2
  4465.8  137.19  4480.6  136.97  4485.8  136.89  4495.8  136.41  4535.8  135.99
  4555.8  135.59    4623  131.53  4735.8  132.53  4736.7  132.54  4770.8  132.56
  4789.6     133  4814.2  133.57  4845.7  134.21    4863  134.56  4904.4  133.98
 4932.19  134.14  4932.3  134.14 4932.41  134.14  4932.5  134.14 4932.61  134.14
  4932.7  134.14  4932.8  134.14  4933.4  134.15  4944.4  134.21  4963.6  133.96
  4964.1   133.3  4973.3  122.58  4982.5  124.66  4989.7  121.58  4997.3  120.78
  5002.2  120.27  5012.2  123.12  5017.3  123.73  5017.5  124.57    5048   133.5
  5051.7  134.72 5051.79  134.75  5051.9  134.79    5052  134.79 5052.09  134.79
  5052.2  134.79  5052.3  134.79 5052.41  134.79  5053.2  134.78  5094.4  134.62
  5135.1  134.44  5136.9  134.46  5166.1  134.79  5167.9  134.78  5203.1  134.68
  5220.5  134.68  5253.2  134.67  5257.8  134.77  5273.8  135.11    5313  131.88
    5323  132.31  5355.4  132.26  5370.4  132.33  5376.3  132.14  5385.4  131.85
  5450.4  132.03  5475.4  131.65  5505.4  132.03  5545.4  131.13  5550.4  131.19
  5565.4  132.07  5610.4  131.73  5630.4  132.16  5640.4  132.63  5665.4  131.82
  5670.4  131.86  5680.4  132.19  5700.4  131.61  5702.1  131.62  5730.4  131.78
  5731.9  131.73  5743.3  131.37  5753.3   130.3  5768.3  133.04  5778.3  133.95
  5789.8  134.59  5819.6  135.32    5888     137
BR U #Mann= 5
    4388     .08  4963.6    .035  5051.7     .08  5376.3      .1  5731.9      .2
BR U Banks=4963.6,5051.7
BR D #Sta/Elev= 88
    4388  136.87    4428   137.1    4438  136.77    4443  136.76    4453   137.1
  4465.8  137.09  4480.6  136.87  4485.8  136.79  4495.8  136.31  4535.8  135.89
  4555.8  135.49    4623  131.43  4735.8  132.43  4736.7  132.44  4770.8  132.46
  4789.6   132.9  4814.2  133.47  4845.7  134.11    4863  134.46  4904.4  133.88
 4932.19  134.04  4932.3  134.04 4932.41  134.04  4932.5  134.04 4932.61  134.04
  4932.7  134.04  4932.8  134.04  4933.4  134.05  4944.4  134.11  4963.6  133.86
  4964.1   133.2  4973.3  122.48  4982.5  124.56  4989.7  121.48  4997.3  120.68
  5002.2  120.17  5012.2  123.02  5017.3  123.63  5017.5  124.47    5048   133.4
  5051.7  134.62 5051.79  134.65  5051.9  134.69    5052  134.69 5052.09  134.69
  5052.2  134.69  5052.3  134.69 5052.41  134.69  5053.2  134.68  5094.4  134.52
  5135.1  134.34  5136.9  134.36  5166.1  134.69  5167.9  134.68  5203.1  134.58
  5220.5  134.58  5253.2  134.57  5257.8  134.67  5273.8  135.01    5313  131.78
    5323  132.21  5355.4  132.16  5370.4  132.23  5376.3  132.04  5385.4  131.75
  5450.4  131.93  5475.4  131.55  5505.4  131.93  5545.4  131.03  5550.4  131.09
  5565.4  131.97  5610.4  131.63  5630.4  132.06  5640.4  132.53  5665.4  131.72
  5670.4  131.76  5680.4  132.09  5700.4  131.51  5702.1  131.52  5730.4  131.68
  5731.9  131.63  5743.3  131.27  5753.3   130.2  5768.3  132.94  5778.3  133.85
  5789.8  134.49  5819.6  135.22    5888   136.9
BR D #Mann= 5
    4388     .08  4963.6    .035  5051.7     .08  5376.3      .1  5731.9      .2
BR D Banks=4963.6,5051.7
BC Design=,, 0 ,, 0 ,,,,,,
BC HTab HWMax=137.2
BC Use User HTab Curves=0
BC User HTab FreeFlow(D)= 0

Type RM Length L Ch R = 1 ,36668.7 ,445.2,445.2,445.2
BEGIN DESCRIPTION:
Downstream Section of Bridge/Culvert/Weir
END DESCRIPTION:
XS GIS Cut Line= 4
      2990488.29     13853170.65      2990212.89     13853165.82
      2989619.63     13853145.67      2988988.92     13853127.81
#Sta/Elev= 30
    4388  136.86  4465.8  137.08  4555.8  135.48    4623  131.42  4770.8  132.45
    4863  134.45  4963.6  133.85  4973.3  122.47  4982.5  124.55  4989.7  121.47
  5002.2  120.16  5012.2  123.01  5017.3  123.62  5017.5  124.46  5051.7  134.61
  5135.1  134.33  5273.8     135    5313  131.77  5376.3  132.03  5505.4  131.92
  5545.4  131.02  5565.4  131.96  5610.4  131.62  5640.4  132.52  5665.4  131.71
  5731.9  131.62  5753.3  130.19  5768.3  132.93  5789.8  134.48    5888  136.89
#Mann= 5 , 1 , 0
    4388     .08       0  4963.6    .035       0  5051.7     .08       0
  5376.3      .1       0  5731.9      .2       0
#XS Ineff= 2 , 0
       0    4955   135.5    5058       0   135.5
Permanent Ineff=
       F       F
Bank Sta=4963.6,5051.7
XS Rating Curve= 0 ,0
Exp/Cntr=0.5,0.3

Type RM Length L Ch R = 1 ,36223.5 ,739.1,805.5,898.7
BEGIN DESCRIPTION:
Cross Section 36223.5
END DESCRIPTION:
XS GIS Cut Line= 6
      2990442.94     13852882.63      2990177.07     13852869.54
      2989909.31     13852709.53      2989662.89     13852593.57
      2989599.07      13852590.2 2989480.634906213852583.9460629
#Sta/Elev= 18
    4534  135.53  4800.1  136.37  4861.4  133.43  4944.3   133.1  4990.2   120.3
  4999.8  119.81  5009.8  120.28  5027.6  121.74  5058.6  131.93  5108.4  131.75
  5112.1  134.18  5119.6  134.17  5247.1  134.06  5272.1  133.43  5362.1  134.63
  5384.4  134.32  5448.4  134.82    5567   135.2
#Mann= 4 ,-1 , 0
    4534     .08       0  4944.3    .035       0  5058.6     .08       0
  5119.6      .1       0
#XS Ineff= 2 , 0
       0    4800   136.4    5360       0   134.7
Permanent Ineff=
       F       F
Bank Sta=4944.3,5058.6
XS Rating Curve= 0 ,0
Exp/Cntr=0.3,0.1

Type RM Length L Ch R = 1 ,35418.0 ,69.3,87.2,98.5
BEGIN DESCRIPTION:
Cross Section 35418.0-Interpolated
END DESCRIPTION:
XS GIS Cut Line= 5
      2990682.96     13852596.96      2990656.52     13852557.73
      2990523.46     13852234.07      2990494.69     13852068.64
      2990454.05      13851820.9
#Sta/Elev= 30
  4511.9   135.3  4544.3  135.56  4549.3  135.68  4555.1  135.82  4864.5  136.41
  4880.7  136.14  4912.9  135.07  4928.1  134.98  4937.3  134.46  4943.3  133.75
  4958.5  130.75  4973.8  126.01  4976.2  125.34  4977.5  121.63  4989.3  119.39
  5009.9  119.17  5022.4   121.1  5034.7  126.64    5044  129.34  5049.9  131.27
  5065.1  134.75    5080  134.54  5095.5  135.02  5125.9  135.14  5133.6  135.33
  5184.5  136.59  5189.9  136.32  5201.9  136.13  5210.6   135.3  5328.1  135.34
#Mann= 5 , 1 , 0
  4511.9      .2       0  4549.3     .08       0  4937.3    .035       0
  5065.1     .08       0  5133.6      .1       0
#XS Ineff= 2 , 0
       0    4864   136.4    5180       0   136.7
Permanent Ineff=
       F       F
Bank Sta=4937.3,5065.1
XS Rating Curve= 0 ,0
Exp/Cntr=0.3,0.1

Type RM Length L Ch R = 1 ,35330.8 ,131.8,131.8,131.8
BEGIN DESCRIPTION:
Cross Section 35330.8-Interpolated
END DESCRIPTION:
XS GIS Cut Line= 6
      2990711.37     13852590.39      2990693.56     13852561.92
      2990601.79      13852380.6      2990594.45     13852136.73
      2990581.62     13851946.03      2990582.33     13851883.21
#Sta/Elev= 22
  4519.6  135.31  4549.3   135.4  4553.1  135.41  4702.4  135.96  4756.4  135.99
  4891.7  135.94  4921.7  135.08  4936.7  134.31  4948.2  131.97  4951.7  131.39
  4966.7  126.73  4977.5  121.56  4989.3  119.32  4999.1  119.18  5009.9   119.1
  5022.4  121.03  5026.8  126.11  5041.8  131.54  5048.5  133.06  5071.9   134.7
  5191.5  136.78  5254.3  137.05
#Mann= 4 ,-1 , 0
  4519.6      .2       0  4549.3     .08       0  4921.7    .035       0
  5071.9     .08       0
Bank Sta=4921.7,5071.9
XS Rating Curve= 0 ,0
Exp/Cntr=0.5,0.3

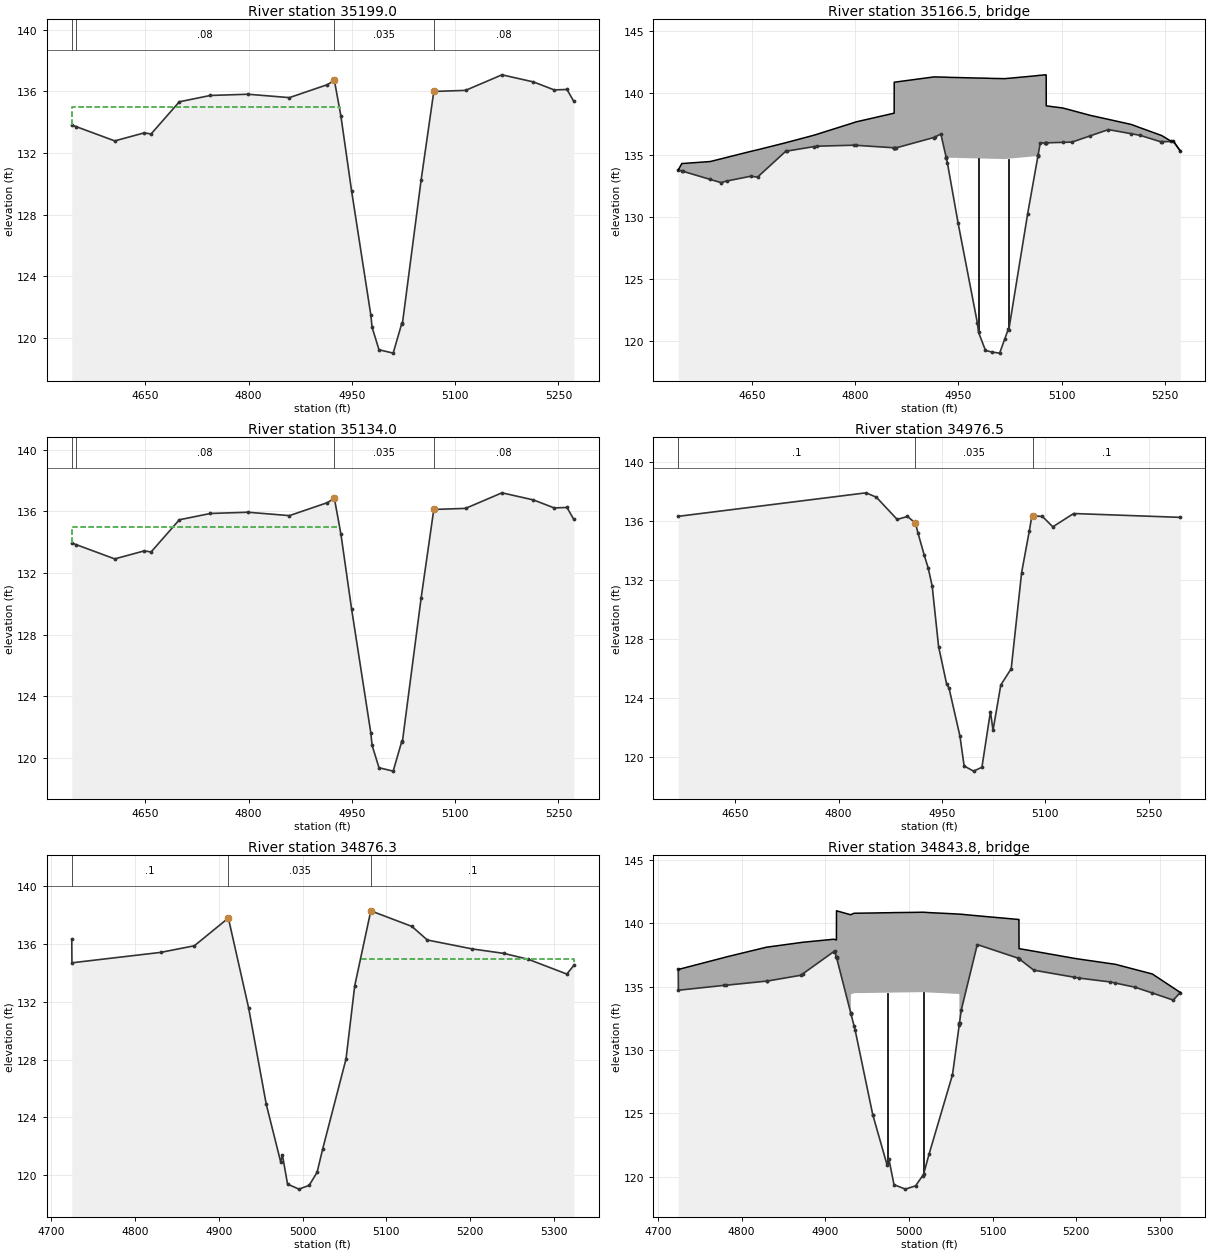
Type RM Length L Ch R = 1 ,35199.0 ,65,65,65
BEGIN DESCRIPTION:
Upstream Section of Bridge/Culvert/Weir
END DESCRIPTION:
XS GIS Cut Line= 5
      2990796.19     13852591.35      2990775.25      13852549.8
      2990729.63     13852033.28      2990722.27     13851882.43
      2990728.93     13851871.09
#Sta/Elev= 27
  4543.1  133.81  4549.3  133.71  4605.5  132.78  4648.3   133.3  4658.3  133.23
  4699.3  135.32  4744.4  135.73    4799  135.81  4859.2  135.59  4914.2  136.43
  4924.5  136.71    4934  134.39  4949.5  129.53  4977.5  121.46  4979.2  120.69
  4989.3  119.22  5009.9     119  5022.4  120.93  5023.2  120.88  5050.5  130.24
  5068.9  135.99    5115  136.06  5167.9  137.07  5213.6  136.61  5243.8  136.09
  5262.3  136.12  5272.3  135.34
#Mann= 4 ,-1 , 0
  4543.1      .2       0  4549.3     .08       0  4924.5    .035       0
  5068.9     .08       0
#XS Ineff= 2 , 0
       0 4932.21  134.96  5066.1       0   135.1
Permanent Ineff=
       F       F
Bank Sta=4924.5,5068.9
XS Rating Curve= 0 ,0
Exp/Cntr=0.5,0.3

Type RM Length L Ch R = 3 ,35166.5 ,,,
BEGIN DESCRIPTION:
PEEK ROAD SOUTH
Structure ID: T01-23
END DESCRIPTION:
Bridge Culvert--1,0,-1,-1, 0
Deck Dist Width WeirC Skew NumUp NumDn MinLoCord MaxHiCord MaxSubmerge Is_Ogee
10,45,2.6,0, 55, 55, , , 0.95, 0, 1,1,,
  4543.1  4548.3  4549.3  4589.6  4605.5  4613.3  4648.3  4658.3  4699.3  4700.5
  4739.7  4744.4    4799  4801.7 4856.69  4856.8 4856.91  4857.6  4859.2  4914.2
  4915.3  4924.5 4932.21  4932.3  4932.4    4934  4949.5  4977.5  4979.2  4989.3
  4999.1  5009.9  5017.5  5022.4  5023.2  5050.5  5065.5 5065.59  5065.7  5068.9
    5076 5077.39  5077.5 5077.61  5101.4    5115  5141.7  5167.9  5200.9  5213.6
  5243.8  5245.3  5259.2  5262.3  5272.3
   133.8  134.32  134.32  134.48   134.7  134.81   135.3  135.43     136  136.02
   136.6  136.68  137.64  137.69  138.39  140.89  140.89   140.9  140.91  141.32
  141.32  141.31   141.3   141.3   141.3  141.29  141.27  141.23  141.23  141.22
   141.2  141.19  141.18  141.21  141.21  141.35  141.43  141.43  141.44  141.45
  141.49  141.48  141.48  138.98  138.81  138.61  138.21  137.89  137.48  137.22
  136.61  136.58  136.11  136.12  135.33
   133.8  133.71   133.7  133.03  132.77   132.9  133.29  133.22  135.31  135.32
  135.68  135.72   135.8  135.79  135.59  135.59  135.59  135.59  135.58  136.42
  136.44   136.7  134.82   134.8   134.8  134.79  134.77  134.73  134.73  134.72
   134.7  134.69  134.68  134.71  134.71  134.85  134.93  134.95  134.98  135.98
  135.99  135.99  135.99  135.99  136.03  136.05  136.56  137.06  136.73   136.6
  136.08  136.08   136.1  136.11  135.33
  4543.1  4548.3  4549.3  4589.6  4605.5  4613.3  4648.3  4658.3  4699.3  4700.5
  4739.7  4744.4    4799  4801.7 4856.69  4856.8 4856.91  4857.6  4859.2  4914.2
  4915.3  4924.5 4932.21  4932.3  4932.4    4934  4949.5  4977.5  4979.2  4989.3
  4999.1  5009.9  5017.5  5022.4  5023.2  5050.5  5065.5 5065.59  5065.7  5068.9
    5076 5077.39  5077.5 5077.61  5101.4    5115  5141.7  5167.9  5200.9  5213.6
  5243.8  5245.3  5259.2  5262.3  5272.3
  133.94  134.32  134.32  134.48   134.7  134.81   135.3  135.43     136  136.02
   136.6  136.68  137.64  137.69  138.39  140.89  140.89   140.9  140.91  141.32
  141.32  141.31   141.3   141.3   141.3  141.29  141.27  141.23  141.23  141.22
   141.2  141.19  141.18  141.21  141.21  141.35  141.43  141.43  141.44  141.45
  141.49  141.48  141.48  138.98  138.81  138.61  138.21  137.89  137.48  137.22
  136.61  136.58  136.24  136.25  135.47
  133.94  133.85  133.84  133.17  132.91  133.04  133.43  133.36  135.45  135.46
  135.82  135.86  135.94  135.93  135.73  135.73  135.73  135.73  135.72  136.56
  136.58  136.84  134.96  134.94  134.94  134.93  134.91  134.87  134.87  134.86
  134.84  134.83  134.82  134.85  134.85  134.99  135.07  135.09  135.12  136.12
  136.13  136.13  136.13  136.13  136.17  136.19   136.7   137.2  136.87  136.74
  136.22  136.22  136.24  136.25  135.47
Pier Skew, UpSta & Num, DnSta & Num=  ,4979.2, 2 ,4979.2, 2 , 0 , 0 , 0 ,,
     1.4     1.4
  119.58  135.73
     1.4     1.4
  119.72  135.87
Pier Skew, UpSta & Num, DnSta & Num=  ,5023.3, 2 ,5023.3, 2 , 0 , 0 , 0 ,,
     1.4     1.4
  119.91  135.71
     1.4     1.4
  120.05  135.85
BR Coef= 1 , 1 , 0 ,1.25, 0 ,,,0.8,0,2,0,
WSPro=,,,, 1 ,,,, 0 ,,,, 0 ,,,,-1 ,-1 ,-1 , 0 , 0 , 0 , 0 , 0
BR U #Sta/Elev= 55
  4543.1   133.8  4548.3  133.71  4549.3   133.7  4589.6  133.03  4605.5  132.77
  4613.3   132.9  4648.3  133.29  4658.3  133.22  4699.3  135.31  4700.5  135.32
  4739.7  135.68  4744.4  135.72    4799   135.8  4801.7  135.79 4856.69  135.59
  4856.8  135.59 4856.91  135.59  4857.6  135.59  4859.2  135.58  4914.2  136.42
  4915.3  136.44  4924.5   136.7 4932.21  134.82  4932.3   134.8  4932.4  134.77
    4934  134.38  4949.5  129.52  4977.5  121.45  4979.2  120.68  4989.3  119.21
  4999.1  119.07  5009.9  118.99  5017.5  120.16  5022.4  120.92  5023.2  120.87
  5050.5  130.23  5065.5  134.92 5065.59  134.95  5065.7  134.98  5068.9  135.98
    5076  135.99 5077.39  135.99  5077.5  135.99 5077.61  135.99  5101.4  136.03
    5115  136.05  5141.7  136.56  5167.9  137.06  5200.9  136.73  5213.6   136.6
  5243.8  136.08  5245.3  136.08  5259.2   136.1  5262.3  136.11  5272.3  135.33
BR U #Mann= 4
  4543.1      .2  4549.3     .08  4924.5    .035  5068.9     .08
BR U Banks=4924.5,5068.9
BR D #Sta/Elev= 55
  4543.1  133.94  4548.3  133.85  4549.3  133.84  4589.6  133.17  4605.5  132.91
  4613.3  133.04  4648.3  133.43  4658.3  133.36  4699.3  135.45  4700.5  135.46
  4739.7  135.82  4744.4  135.86    4799  135.94  4801.7  135.93 4856.69  135.73
  4856.8  135.73 4856.91  135.73  4857.6  135.73  4859.2  135.72  4914.2  136.56
  4915.3  136.58  4924.5  136.84 4932.21  134.96  4932.3  134.94  4932.4  134.91
    4934  134.52  4949.5  129.66  4977.5  121.59  4979.2  120.82  4989.3  119.35
  4999.1  119.21  5009.9  119.13  5017.5   120.3  5022.4  121.06  5023.2  121.01
  5050.5  130.37  5065.5  135.06 5065.59  135.09  5065.7  135.12  5068.9  136.12
    5076  136.13 5077.39  136.13  5077.5  136.13 5077.61  136.13  5101.4  136.17
    5115  136.19  5141.7   136.7  5167.9   137.2  5200.9  136.87  5213.6  136.74
  5243.8  136.22  5245.3  136.22  5259.2  136.24  5262.3  136.25  5272.3  135.47
BR D #Mann= 4
  4543.1      .2  4549.3     .08  4924.5    .035  5068.9     .08
BR D Banks=4924.5,5068.9
BC Design=,, 0 ,, 0 ,,,,,,
BC HTab HWMax=137.07
BC Use User HTab Curves=0
BC User HTab FreeFlow(D)= 0

Type RM Length L Ch R = 1 ,35134.0 ,157.5,157.5,157.5
BEGIN DESCRIPTION:
Downstream Section of Bridge/Culvert/Weir
END DESCRIPTION:
XS GIS Cut Line= 5
      2990861.17     13852592.74      2990840.23      13852551.2
      2990794.61     13852034.68      2990787.25     13851883.83
      2990793.91     13851872.49
#Sta/Elev= 27
  4543.1  133.94  4549.3  133.84  4605.5  132.91  4648.3  133.43  4658.3  133.36
  4699.3  135.45  4744.4  135.86    4799  135.94  4859.2  135.72  4914.2  136.56
  4924.5  136.84    4934  134.52  4949.5  129.66  4977.5  121.59  4979.2  120.82
  4989.3  119.35  5009.9  119.13  5022.4  121.06  5023.2  121.01  5050.5  130.37
  5068.9  136.12    5115  136.19  5167.9   137.2  5213.6  136.74  5243.8  136.22
  5262.3  136.25  5272.3  135.47
#Mann= 4 ,-1 , 0
  4543.1      .2       0  4549.3     .08       0  4924.5    .035       0
  5068.9     .08       0
#XS Ineff= 2 , 0
       0 4932.21  134.96  5066.1       0   135.1
Permanent Ineff=
       F       F
Bank Sta=4924.5,5068.9
XS Rating Curve= 0 ,0
Exp/Cntr=0.5,0.3

Type RM Length L Ch R = 1 ,34976.5 ,100.2,100.2,100.2
BEGIN DESCRIPTION:
Cross Section 34976.5-Interpolated
END DESCRIPTION:
XS GIS Cut Line= 4
      2990980.99     13852577.09      2990957.25     13852278.86
      2990948.65     13852144.02      2990916.88      13851851.4
#Sta/Elev= 29
  4567.2  136.31  4839.8   137.9  4854.8   137.6  4884.9   136.1  4899.9   136.3
  4911.4  135.85    4915   135.2  4924.1   133.7    4930   132.8  4935.7   131.6
    4945   127.5  4956.8  124.94  4960.1   124.7    4976  121.44  4982.1  119.42
  4995.7  119.07  5007.9  119.33  5020.3   123.1    5024  121.83  5035.3   124.9
  5050.4     126  5065.5   132.5  5076.6   135.3  5080.6   136.4  5081.6  136.35
  5095.7   136.3  5110.8   135.6    5141   136.5  5295.8  136.24
#Mann= 3 , 1 , 0
  4567.2      .1       0  4911.4    .035       0  5081.6      .1       0
Bank Sta=4911.4,5081.6
XS Rating Curve= 0 ,0
Exp/Cntr=0.5,0.3

Type RM Length L Ch R = 1 ,34876.3 ,65,65,65
BEGIN DESCRIPTION:
Upstream Section of Bridge/Culvert/Weir
END DESCRIPTION:
XS GIS Cut Line= 2
      2991095.43     13852426.39      2991042.26     13851828.82
#Sta/Elev= 24
  4724.3  136.35  4724.5  134.71  4830.5  135.43  4870.8  135.89  4911.4  137.81
  4935.7  131.56  4956.7   124.9  4973.9  120.92    4976   121.4  4982.1  119.38
  4995.7  119.03  5007.9  119.29  5017.4  120.19    5024  121.79    5052  128.05
  5062.4  133.12  5081.6  138.31  5130.7  137.23  5149.1  136.29  5202.9  135.67
  5240.7  135.36  5269.9  134.95  5315.8  133.93  5324.2  134.53
#Mann= 3 , 1 , 0
  4724.3      .1       0  4911.4    .035       0  5081.6      .1       0
#XS Ineff= 2 , 0
       0    4920     135    5070       0     135
Permanent Ineff=
       F       F
Bank Sta=4911.4,5081.6
XS Rating Curve= 0 ,0
Exp/Cntr=0.5,0.3

Type RM Length L Ch R = 3 ,34843.8 ,,,
BEGIN DESCRIPTION:
PEEK ROAD NORTH
Structure ID: T01-22
END DESCRIPTION:
Bridge Culvert--1,0,-1,-1, 0
Deck Dist Width WeirC Skew NumUp NumDn MinLoCord MaxHiCord MaxSubmerge Is_Ogee
10,45,2.6,0, 49, 49, , , 0.95, 0, 1,1,,
  4724.3  4724.5  4778.7  4780.8  4830.2  4830.5  4870.8  4872.9  4910.1  4911.4
 4913.29  4913.4 4913.51  4930.4 4930.51  4930.6  4934.4  4935.7  4956.7  4956.8
  4973.9    4976  4982.1  4995.7  5007.9  5016.2  5017.4    5024    5052  5060.1
 5060.19  5060.3  5060.4  5062.4  5081.6  5130.7  5131.1 5131.29  5131.4 5131.51
  5149.1    5197  5202.9  5240.7  5246.3  5269.9  5290.8  5315.8  5324.2
  136.35  136.35  137.28  137.32  138.11  138.11  138.47  138.49  138.73  138.71
  138.67  140.97  140.97  140.66  140.66  140.67  140.78  140.78   140.8   140.8
  140.82  140.82  140.83  140.84  140.85  140.86  140.86  140.83  140.74  140.71
  140.71  140.71  140.71   140.7  140.58  140.29  140.29  140.29  140.29  137.99
  137.79  137.23  137.17  136.81  136.76  136.35  135.99   134.9  134.53
  136.35  134.71  135.09   135.1  135.43  135.43  135.89  135.99  137.75  137.81
  137.32   137.3  137.27  132.92  132.89  134.37  134.48  134.48   134.5   134.5
  134.52  134.52  134.53  134.54  134.55  134.56  134.56  134.53  134.44  134.41
  134.41   132.1  132.14  133.12  138.31  137.23  137.21   137.2  137.19  137.19
  136.29  135.74  135.67  135.36  135.28  134.95  134.49  133.93  134.53
  4724.3  4724.5  4778.7  4780.8  4830.2  4830.5  4870.8  4872.9  4910.1  4911.4
 4913.29  4913.4 4913.51  4930.4 4930.51  4930.6  4934.4  4935.7  4956.7  4956.8
  4973.9    4976  4982.1  4995.7  5007.9  5016.2  5017.4    5024    5052  5060.1
 5060.19  5060.3  5060.4  5062.4  5081.6  5130.7  5131.1 5131.29  5131.4 5131.51
  5149.1    5197  5202.9  5240.7  5246.3  5269.9  5290.8  5315.8  5324.2
  136.35  136.35  137.28  137.32  138.11  138.11  138.47  138.49  138.73  138.71
  138.67  140.97  140.97  140.66  140.66  140.67  140.78  140.78   140.8   140.8
  140.82  140.82  140.83  140.84  140.85  140.86  140.86  140.83  140.74  140.71
  140.71  140.71  140.71   140.7  140.58  140.29  140.29  140.29  140.29  137.99
  137.79  137.23  137.17  136.81  136.76  136.35  135.99   134.9  134.53
  136.25  134.61  134.99     135  135.33  135.33  135.79  135.89  137.65  137.71
  137.22   137.2  137.17  132.82  132.79  134.27  134.38  134.38   134.4   134.4
  134.42  134.42  134.43  134.44  134.45  134.46  134.46  134.43  134.34  134.31
  134.31     132  132.04  133.02  138.21  137.13  137.11   137.1  137.09  137.09
  136.19  135.64  135.57  135.26  135.18  134.85  134.39  133.83  134.43
Pier Skew, UpSta & Num, DnSta & Num=  ,4973.9, 2 ,4973.9, 2 , 0 , 0 , 0 ,,
     1.4     1.4
  120.08  135.52
     1.4     1.4
  119.98  135.42
Pier Skew, UpSta & Num, DnSta & Num=  ,5017.4, 2 ,5017.4, 2 , 0 , 0 , 0 ,,
     1.4     1.4
  119.13  135.56
     1.4     1.4
  119.03  135.46
Abutment Skew #Up #Dn= , 2 , 2
  4930.4  4956.8
  134.37  124.88
  4930.4  4956.8
  134.27  124.78
BR Coef= 1 , 1 , 0 ,1.25, 0 ,,,0.8,0,2,0,
WSPro=,,,, 1 ,,,, 0 ,,,, 0 ,,,,-1 ,-1 ,-1 , 0 , 0 , 0 , 0 , 0
BR U #Sta/Elev= 49
  4724.3  136.35  4724.5  134.71  4778.7  135.09  4780.8   135.1  4830.2  135.43
  4830.5  135.43  4870.8  135.89  4872.9  135.99  4910.1  137.75  4911.4  137.81
 4913.29  137.32  4913.4   137.3 4913.51  137.27  4930.4  132.92 4930.51  132.89
  4930.6  132.87  4934.4  131.89  4935.7  131.56  4956.7   124.9  4956.8  124.88
  4973.9  120.92    4976   121.4  4982.1  119.38  4995.7  119.03  5007.9  119.29
  5016.2  120.08  5017.4  120.19    5024  121.79    5052  128.05  5060.1     132
 5060.19  132.04  5060.3   132.1  5060.4  132.14  5062.4  133.12  5081.6  138.31
  5130.7  137.23  5131.1  137.21 5131.29   137.2  5131.4  137.19 5131.51  137.19
  5149.1  136.29    5197  135.74  5202.9  135.67  5240.7  135.36  5246.3  135.28
  5269.9  134.95  5290.8  134.49  5315.8  133.93  5324.2  134.53
BR U #Mann= 3
  4724.3      .1  4911.4    .035  5081.6      .1
BR U Banks=4911.4,5081.6
BR D #Sta/Elev= 49
  4724.3  136.25  4724.5  134.61  4778.7  134.99  4780.8     135  4830.2  135.33
  4830.5  135.33  4870.8  135.79  4872.9  135.89  4910.1  137.65  4911.4  137.71
 4913.29  137.22  4913.4   137.2 4913.51  137.17  4930.4  132.82 4930.51  132.79
  4930.6  132.77  4934.4  131.79  4935.7  131.46  4956.7   124.8  4956.8  124.78
  4973.9  120.82    4976   121.3  4982.1  119.28  4995.7  118.93  5007.9  119.19
  5016.2  119.98  5017.4  120.09    5024  121.69    5052  127.95  5060.1   131.9
 5060.19  131.94  5060.3     132  5060.4  132.04  5062.4  133.02  5081.6  138.21
  5130.7  137.13  5131.1  137.11 5131.29   137.1  5131.4  137.09 5131.51  137.09
  5149.1  136.19    5197  135.64  5202.9  135.57  5240.7  135.26  5246.3  135.18
  5269.9  134.85  5290.8  134.39  5315.8  133.83  5324.2  134.43
BR D #Mann= 3
  4724.3      .1  4911.4    .035  5081.6      .1
BR D Banks=4911.4,5081.6
BC Design=,, 0 ,, 0 ,,,,,,
BC HTab HWMax=138.31
BC Use User HTab Curves=0
BC User HTab FreeFlow(D)= 0

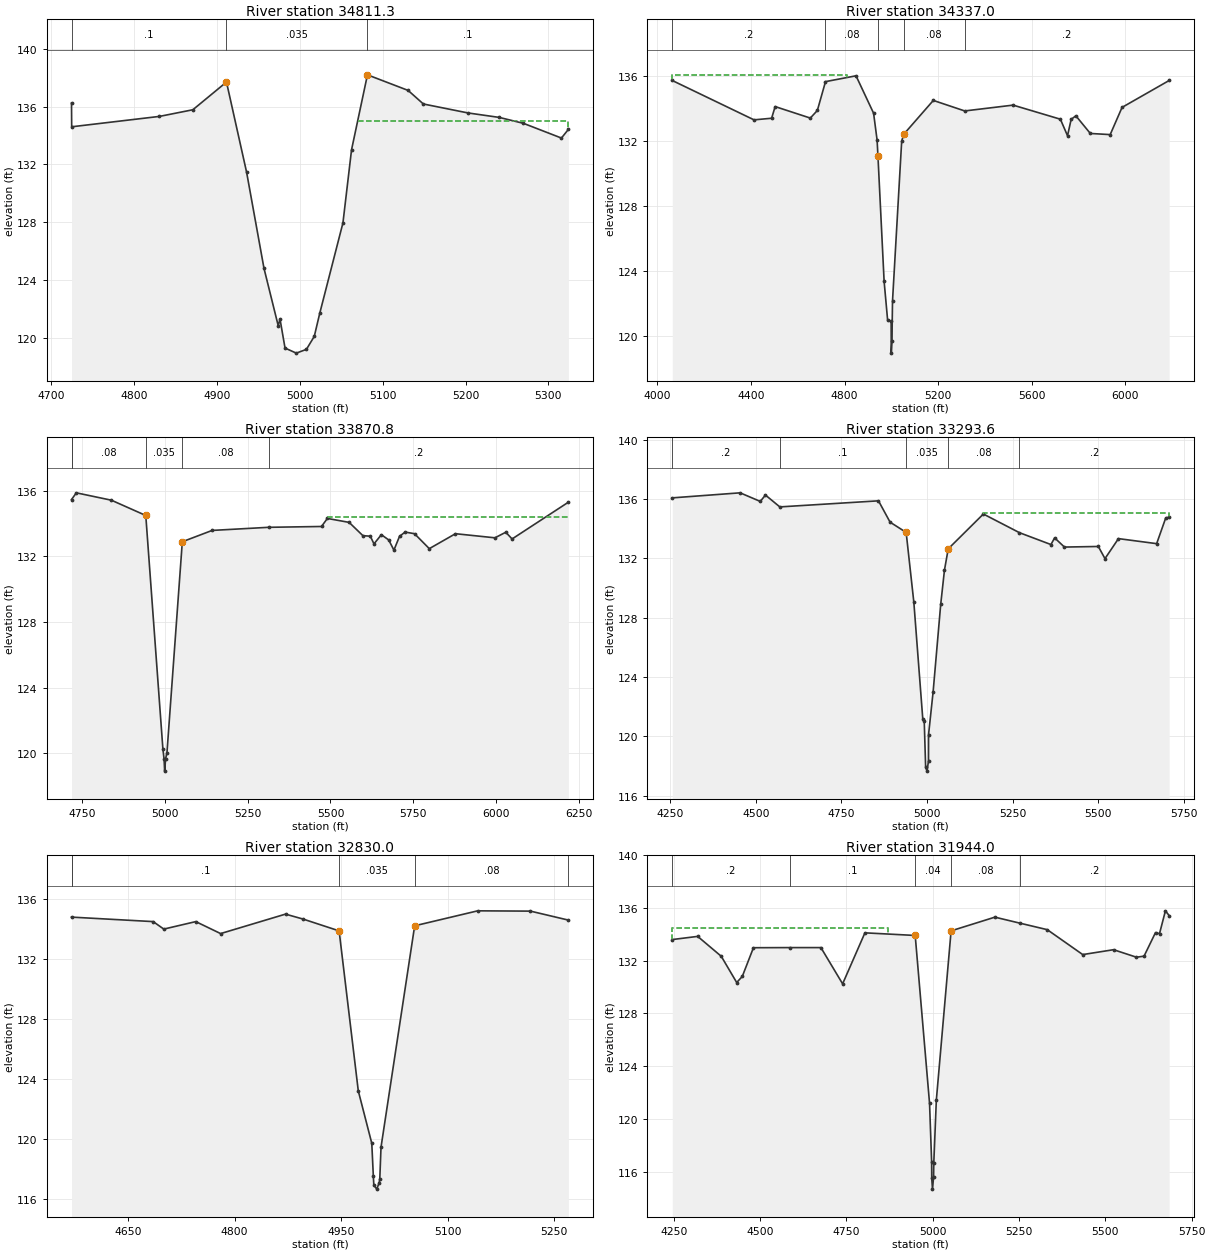
Type RM Length L Ch R = 1 ,34811.3 ,474.3,474.3,474.3
BEGIN DESCRIPTION:
Downstream Section of Bridge/Culvert/Weir
END DESCRIPTION:
XS GIS Cut Line= 2
      2991160.32     13852430.16      2991107.16     13851832.58
#Sta/Elev= 24
  4724.3  136.25  4724.5  134.61  4830.5  135.33  4870.8  135.79  4911.4  137.71
  4935.7  131.46  4956.7   124.8  4973.9  120.82    4976   121.3  4982.1  119.28
  4995.7  118.93  5007.9  119.19  5017.4  120.09    5024  121.69    5052  127.95
  5062.4  133.02  5081.6  138.21  5130.7  137.13  5149.1  136.19  5202.9  135.57
  5240.7  135.26  5269.9  134.85  5315.8  133.83  5324.2  134.43
#Mann= 3 , 1 , 0
  4724.3      .1       0  4911.4    .035       0  5081.6      .1       0
#XS Ineff= 2 , 0
       0    4920     135    5070       0     135
Permanent Ineff=
       F       F
Bank Sta=4911.4,5081.6
XS Rating Curve= 0 ,0
Exp/Cntr=0.5,0.3

Type RM Length L Ch R = 1 ,34337.0 ,466.2,466.2,466.2
BEGIN DESCRIPTION:
Cross Section 34256.5-Interpolated
END DESCRIPTION:
XS GIS Cut Line= 6
       2991530.3     13853104.02      2991583.81     13852360.22
      2991587.72     13852164.44      2991575.98      13851980.4
      2991423.27     13851400.87      2991141.31     13851118.93
#Sta/Elev= 30
  4063.2  135.75  4412.7  133.32  4487.9  133.42    4503  134.14  4653.3  133.43
  4683.4   133.9  4718.2  135.68  4848.7  136.04  4923.8  133.73  4938.8  132.07
  4942.4  131.09  4968.8  123.35  4983.8  120.95  4998.8  120.89  4999.4  118.92
  5002.3  119.68  5004.7  122.14  5043.9  132.01  5052.7  132.43  5179.1  134.52
  5313.4  133.87  5520.1  134.23  5722.3  133.36  5752.8  132.34  5768.3  133.35
  5788.4  133.57  5850.3  132.48  5935.2  132.41  5985.9  134.09  6187.2  135.75
#Mann= 5 , 1 , 0
  4063.2      .2       0  4718.2     .08       0  4942.4    .035       0
  5052.7     .08       0  5313.4      .2       0
#XS Ineff= 2 , 0
       0    4810   136.1    5180       0   134.5
Permanent Ineff=
       F       F
Bank Sta=4942.4,5052.7
XS Rating Curve= 0 ,0
Exp/Cntr=0.3,0.1

Type RM Length L Ch R = 1 ,33870.8 ,574.4,577.2,569.1
BEGIN DESCRIPTION:
Cross Section 33870.8
END DESCRIPTION:
XS GIS Cut Line= 5
      2992151.84     13852332.37      2991993.84     13851985.28
      2991857.91     13851588.83       2991683.9     13851252.81
      2991410.85     13851083.77
#Sta/Elev= 30
  4718.2  135.46  4732.8  135.87  4838.7  135.42  4942.4  134.49    4994  120.29
  4997.6  119.66  4999.4  118.92  5002.3  119.68  5006.3  120.03  5052.7  132.89
  5142.7  133.58  5313.4  133.77  5472.9  133.82  5490.6  134.31  5556.3  134.07
  5597.9  133.26  5620.2  133.23  5631.3  132.76  5653.6  133.32  5675.8     133
  5691.5  132.38  5708.4  133.22  5725.3  133.48  5753.7  133.38  5798.3  132.47
  5877.3  133.38  5996.5  133.13  6029.2  133.47  6048.2  133.06  6218.2   135.3
#Mann= 5 , 1 , 0
  4718.2      .2       0  4718.2     .08       0  4942.4    .035       0
  5052.7     .08       0  5313.4      .2       0
#XS Ineff= 2 , 0
       0                    5491       0   134.4
Permanent Ineff=
       F       F
Bank Sta=4942.4,5052.7
XS Rating Curve= 0 ,0
Exp/Cntr=0.3,0.1

Type RM Length L Ch R = 1 ,33293.6 ,460.9,463.6,479
BEGIN DESCRIPTION:
Cross Section 33293.6-Interpolated
END DESCRIPTION:
XS GIS Cut Line= 5
      2992646.47     13852575.29      2992696.92     13852173.74
      2992573.97     13851866.36       2992509.7     13851751.79
      2992130.54     13851307.88
#Sta/Elev= 30
  4256.2  136.09  4454.4  136.43  4513.2  135.85  4528.3  136.28  4570.3  135.48
  4858.4  135.89  4892.3  134.45  4939.2  133.76  4961.6  129.06  4987.7  121.19
    4992  121.04  4996.1  117.92  5000.2  117.65  5004.5  118.35  5004.6  120.11
    5018  123.01  5040.1   128.9  5051.1  131.22  5062.1  132.65  5164.7     135
  5270.1  133.74    5362  132.94  5372.8  133.39  5401.4  132.77  5500.4  132.81
  5519.8  131.99  5559.2  133.34  5670.7     133  5697.3  134.74  5707.2  134.78
#Mann= 5 , 1 , 0
  4256.2      .2       0  4570.3      .1       0  4939.2    .035       0
  5062.1     .08       0  5270.1      .2       0
#XS Ineff= 2 , 0
       0                    5165       0  135.05
Permanent Ineff=
       F       F
Bank Sta=4939.2,5062.1
XS Rating Curve= 0 ,0
Exp/Cntr=0.3,0.1

Type RM Length L Ch R = 1 ,32830.0 ,889.1,886,882.8
BEGIN DESCRIPTION:
Cross Section 32830.0
END DESCRIPTION:
XS GIS Cut Line= 3
      2993146.49     13852099.25      2993048.06     13851814.32
      2992908.18     13851441.33
#Sta/Elev= 20
  4570.3   134.8  4685.3   134.5  4700.3     134  4745.3   134.5  4780.3   133.7
  4871.7     135  4896.4  134.67  4947.2  133.88  4974.2  123.19  4993.2  119.69
  4995.4  117.48  4996.1   116.9  5000.2  116.63  5003.7  117.07  5004.5  117.33
  5006.2  119.43  5053.6  134.22  5142.4  135.22  5216.7   135.2  5270.1   134.6
#Mann= 5 , 1 , 0
  4570.3      .2       0  4570.3      .1       0  4947.2    .035       0
  5053.6     .08       0  5270.1      .2       0
Bank Sta=4947.2,5053.6
XS Rating Curve= 0 ,0
Exp/Cntr=0.3,0.1

Type RM Length L Ch R = 1 ,31944.0 ,1117.6,1117.6,1117.6
BEGIN DESCRIPTION:
Cross Section 31944.0-Interpolated
END DESCRIPTION:
XS GIS Cut Line= 4
      2994105.52     13852058.71      2993874.49     13851479.19
      2993753.11     13851193.34      2993510.33     13850750.87
#Sta/Elev= 30
  4245.7  133.61  4319.3  133.85  4387.6  132.34  4432.3  130.35  4448.5  130.81
  4480.8  132.99    4587     133  4676.2     133  4739.1  130.25  4803.7  134.12
  4949.3  133.92  4990.9  121.17  4996.9  116.74  4997.2  115.48  4999.4  114.67
  5002.6   115.6  5003.1  116.62  5010.5  121.42  5053.3  134.27  5180.1  135.31
  5253.2  134.85  5331.8  134.36  5434.5  132.47  5523.8  132.84  5590.1  132.27
  5612.1  132.35  5645.3  134.14  5656.9  134.06    5674  135.79  5684.8  135.43
#Mann= 5 , 1 , 0
  4245.7      .2       0    4587      .1       0  4949.3     .04       0
  5053.3     .08       0  5253.2      .2       0
#XS Ineff= 2 , 0
       0    4870   134.5               0
Permanent Ineff=
       F       F
Bank Sta=4949.3,5053.3
XS Rating Curve= 0 ,0
Exp/Cntr=0.3,0.1