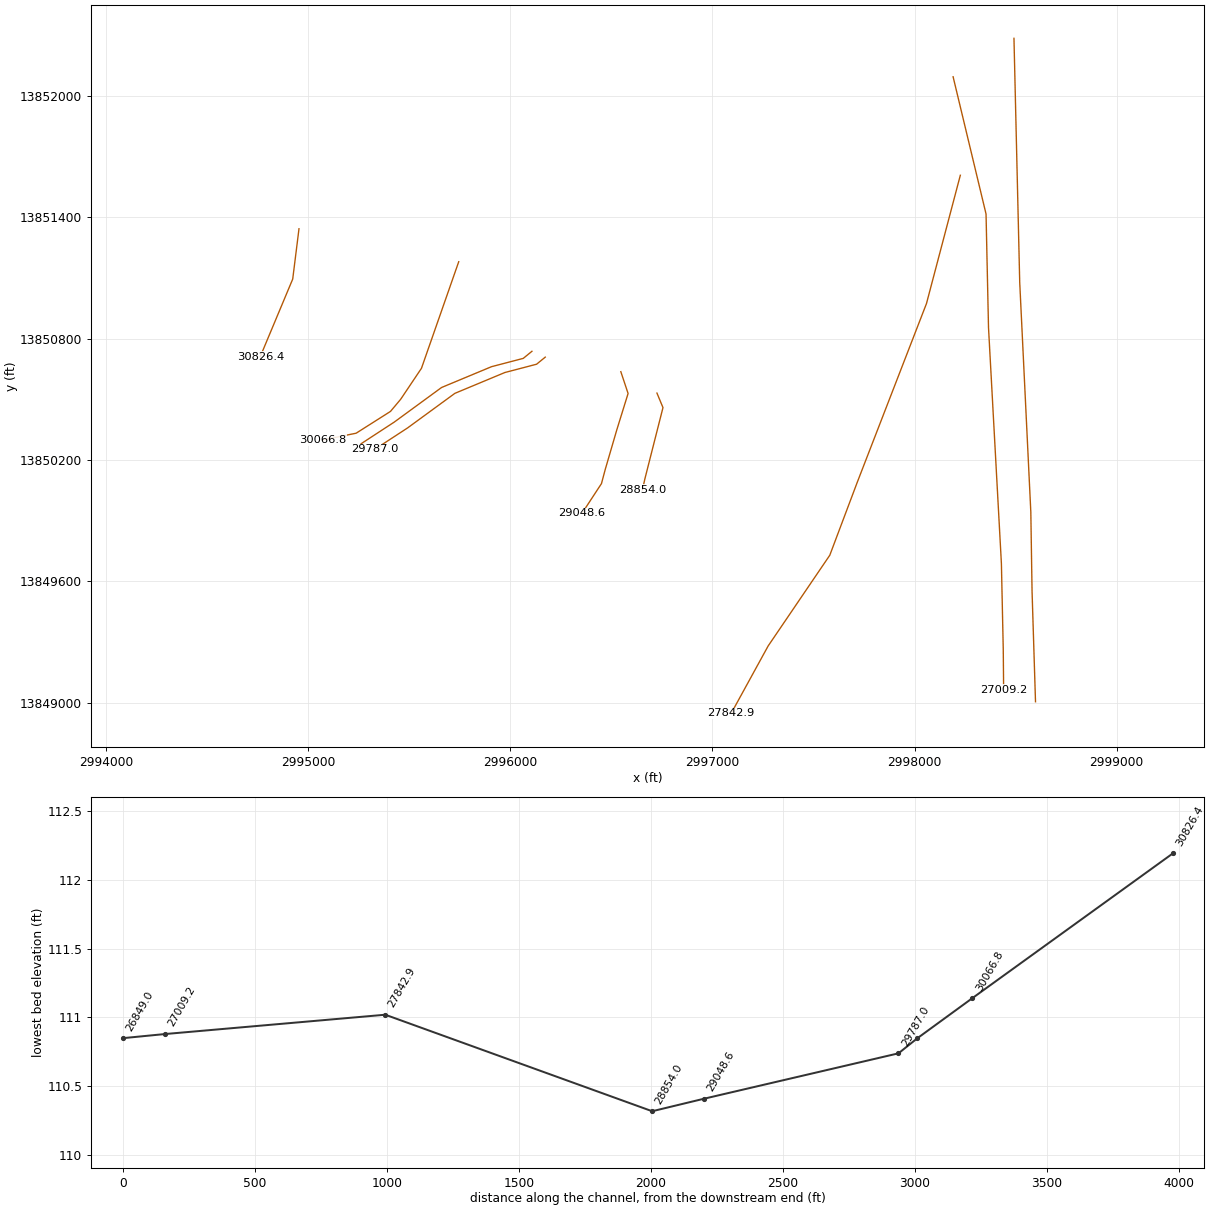
HEC-RAS study T101-00-00.PRJ: T101-00-00

--- T101-00-00.g01 (geometry) --- (continued)

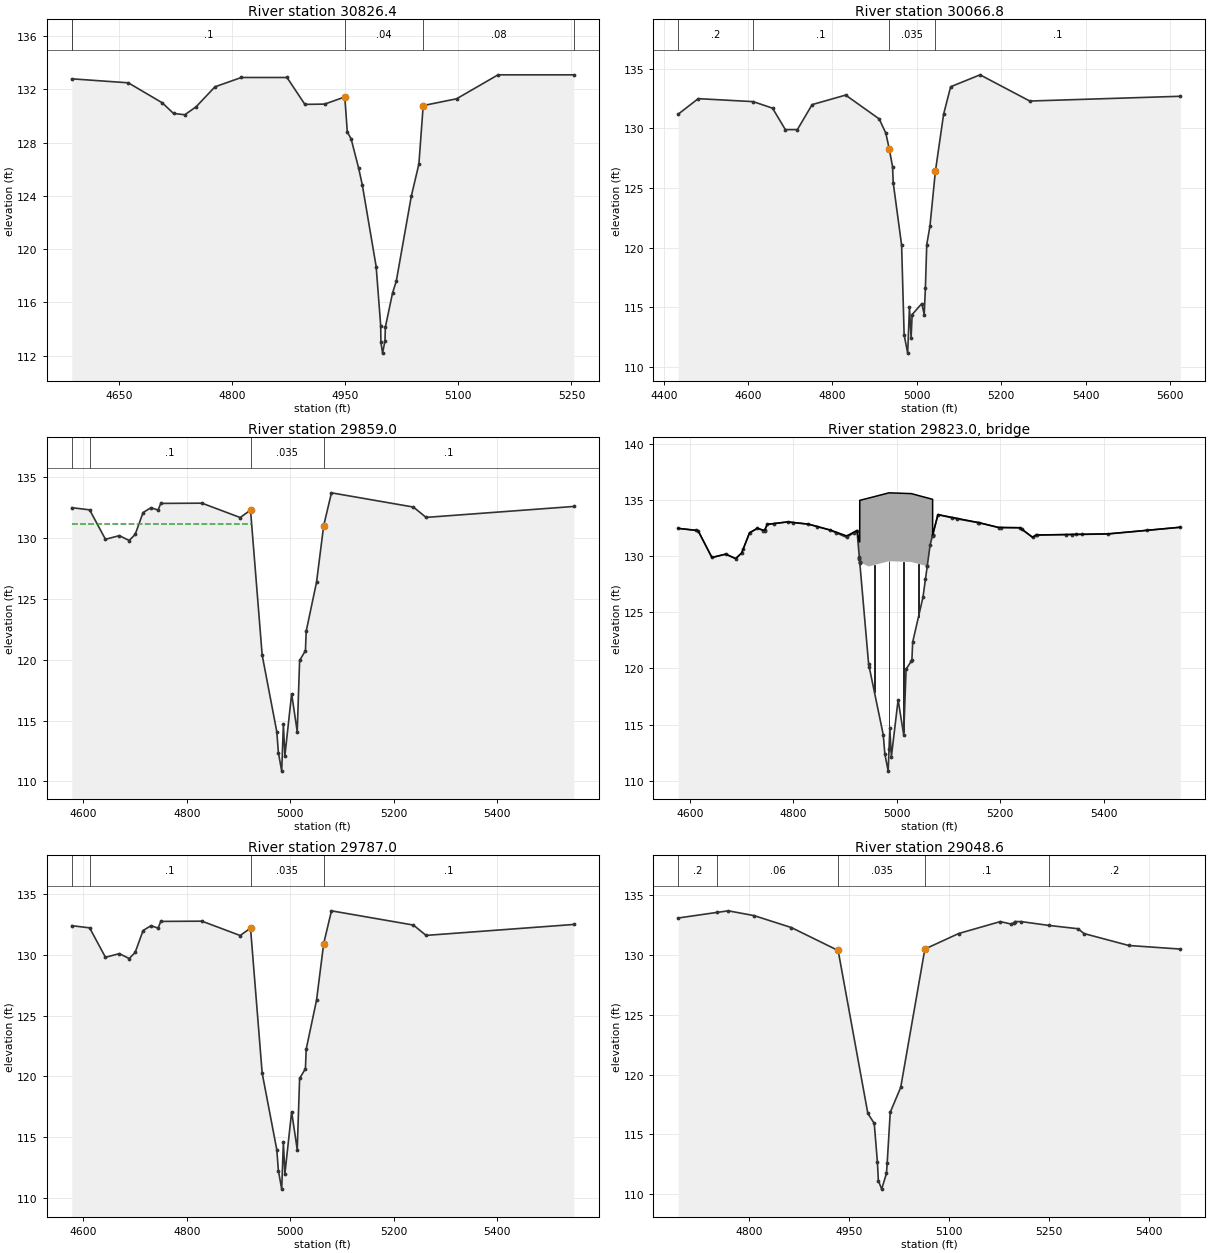
Type RM Length L Ch R = 1 ,30826.4 ,753.8,759.6,743.2
BEGIN DESCRIPTION:
Cross Section 30826.4
END DESCRIPTION:
XS GIS Cut Line= 3
      2994954.46      13851342.9      2994923.38     13851094.24
      2994762.79     13850710.89
#Sta/Elev= 30
    4587   132.8    4662   132.5    4707     131    4722   130.2    4737   130.1
    4752   130.7    4777   132.2    4812   132.9  4872.6   132.9  4896.3  130.88
  4922.6   130.9  4949.3  131.44  4952.6   128.8  4957.6   128.3  4967.6   126.1
  4972.6   124.8  4990.9  118.69  4996.9  114.26  4997.2     113  4999.4  112.19
  5002.6  113.12  5003.1  114.14  5012.6   116.7  5017.6   117.6  5037.6     124
  5047.6   126.4  5053.3  130.79  5097.6   131.3  5152.6   133.1  5253.2   133.1
#Mann= 5 , 1 , 0
    4587      .2       0    4587      .1       0  4949.3     .04       0
  5053.3     .08       0  5253.2      .2       0
Bank Sta=4949.3,5053.3
XS Rating Curve= 0 ,0
Exp/Cntr=0.3,0.1

Type RM Length L Ch R = 1 ,30066.8 ,207.8,207.8,207.8
BEGIN DESCRIPTION:
Cross Section 30066.8-Interpolated
END DESCRIPTION:
XS GIS Cut Line= 6
      2995744.78     13851180.08      2995560.43     13850653.37
      2995457.49     13850500.15      2995407.21      13850440.3
      2995237.23     13850332.56      2995072.03     13850299.04
#Sta/Elev= 30
  4434.2   131.2  4481.6   132.5    4612  132.25  4657.9   131.7  4688.2   129.9
  4716.7   129.9  4751.7     132  4831.2   132.8  4910.7   130.8  4926.5   129.6
  4934.5   128.3  4942.4   126.8    4944  125.44  4963.9   120.2  4969.9  112.67
  4978.3  111.14  4982.5  114.98  4986.4  112.42  4988.9  114.38  5011.8   115.3
  5017.5  114.38  5020.3   116.6  5023.5  120.24  5031.1   121.8    5044   126.4
  5063.5   131.2  5080.2   133.5    5150   134.5  5267.8   132.3  5624.8   132.7
#Mann= 4 , 1 , 0
  4434.2      .2       0    4612      .1       0  4934.5    .035       0
    5044      .1       0
Bank Sta=4934.5,5044
XS Rating Curve= 0 ,0
Exp/Cntr=0.5,0.3

Type RM Length L Ch R = 1 ,29859.0 ,72,72,72
BEGIN DESCRIPTION:
Upstream Section of Bridge/Culvert/Weir
END DESCRIPTION:
XS GIS Cut Line= 6
      2996106.99     13850737.38      2996064.07     13850702.39
       2995906.9     13850661.27      2995659.89     13850558.49
      2995426.15     13850387.74      2995262.38     13850280.88
#Sta/Elev= 30
 4577.47  132.51    4612  132.33 4642.58  129.91 4669.39  130.21 4688.54  129.81
 4700.03  130.31 4715.35  132.11 4730.67  132.51 4744.31  132.31 4749.59  132.86
 4829.18  132.88  4903.1   131.7 4923.09  132.31 4945.61  120.39 4973.88  114.09
 4976.94  112.38 4983.38  110.85  4986.6  114.69 4989.58  112.13  5002.6  117.21
  5013.4  114.09    5018  119.95 5029.26  120.75 5030.72  122.35 5050.71  126.38
 5064.57  131.04 5079.59  133.73    5238  132.56 5262.51  131.71 5548.23  132.61
#Mann= 4 , 1 , 0
 4577.47      .2       0    4612      .1       0 4923.09    .035       0
 5064.57      .1       0
#XS Ineff= 2 , 0
       0  4925.2   131.2  5063.9       0   130.8
Permanent Ineff=
       F       F
Bank Sta=4923.09,5064.57
XS Rating Curve= 0 ,0
Exp/Cntr=0.5,0.3

Type RM Length L Ch R = 3 ,29823.0 ,,,
BEGIN DESCRIPTION:
COLONIAL PARKWAY - 40 Degree Skew
Structure ID: T01-19
END DESCRIPTION:
Bridge Culvert--1,0,-1,-1, 0
Deck Dist Width WeirC Skew NumUp NumDn MinLoCord MaxHiCord MaxSubmerge Is_Ogee
10,52,2.6,0, 34, 34, , , 0.95, 0, 1,1,,
 4577.47 4615.77 4642.58 4669.39 4688.54 4700.03 4715.35 4730.67 4744.31 4749.59
 4788.81 4829.18 4871.47  4903.1 4923.09 4927.54 4927.84 4928.32 4928.43 4945.61
 4985.06 5028.04 5058.87 5064.57  5069.3 5069.41 5079.59 5159.86 5197.09    5238
 5262.51 5270.02 5408.43 5548.23
   132.5   132.3   129.9   130.2   129.8   130.3  132.11  132.51  132.31  132.86
  133.08  132.88  132.35  131.83  132.31  131.29  131.29   131.3     135   135.2
  135.67   135.6  135.22  135.15  135.09  131.91  133.73     133  132.58  132.56
  131.71  131.91  132.01   132.6
   132.5   132.3   129.9   130.2   129.8   130.3   132.1   132.5   132.3  132.85
  133.07  132.87  132.34  131.69   132.3  129.94  129.79  129.53  129.47   129.1
  129.57   129.5  129.12  131.03  131.88   131.9  133.72  132.99  132.57  132.55
   131.7   131.9     132   132.6
 4577.47 4615.77 4642.58 4669.39 4688.54 4700.03 4715.35 4730.67 4744.31 4749.59
 4788.81 4829.18 4871.47  4903.1 4923.09 4927.54 4927.84 4928.32 4928.43 4945.61
 4985.06 5028.04 5058.87 5064.57  5069.3 5069.41 5079.59 5159.86 5197.09    5238
 5262.51 5270.02 5408.43 5548.23
   132.5   132.3   129.9   130.2   129.8   130.3  132.11  132.51  132.31  132.86
  133.08  132.88  132.35  131.83  132.31  131.29  131.29   131.3     135   135.2
  135.67   135.6  135.22  135.15  135.09  131.91  133.73     133  132.58  132.56
  131.71  131.91  132.01   132.6
   132.4   132.2   129.8   130.1   129.7   130.2     132   132.4   132.2  132.75
  132.97  132.77  132.24  131.59   132.2  129.84  129.69  129.43  129.37     129
  129.47   129.4  129.02  130.93  131.78   131.8  133.62  132.89  132.47  132.45
   131.6   131.8   131.9   132.5
Pier Skew, UpSta & Num, DnSta & Num=  ,4956.6, 2 ,4956.6, 2 , 0 , 0 , 0 ,,
     1.4     1.4
  116.78  130.24
     1.4     1.4
  116.68  130.14
Pier Skew, UpSta & Num, DnSta & Num=  ,4984.8, 2 ,4984.8, 2 , 0 , 0 , 0 ,,
     1.4     1.4
  110.74  130.57
     1.4     1.4
  110.64  130.47
Pier Skew, UpSta & Num, DnSta & Num=  ,5013.6, 2 ,5013.6, 2 , 0 , 0 , 0 ,,
     1.4     1.4
  113.24  130.52
     1.4     1.4
  113.14  130.42
Pier Skew, UpSta & Num, DnSta & Num=  ,5041.7, 2 ,5041.7, 2 , 0 , 0 , 0 ,,
     1.4     1.4
  123.41  130.34
     1.4     1.4
  123.31  130.24
Abutment Skew #Up #Dn= , 2 , 2
 4927.64 4946.92
  129.79  120.09
 4927.64 4946.92
  129.69  119.99
Abutment Skew #Up #Dn= , 2 , 2
 5055.54 5059.07
  127.99  129.12
 5055.54 5059.07
  127.89  129.02
BR Coef= 1 , 1 , 0 ,1.25, 0 ,,,0.8,0,2,0,
WSPro=,,,, 1 ,,,, 0 ,,,, 0 ,,,,-1 ,-1 ,-1 , 0 , 0 , 0 , 0 , 0
BR U #Sta/Elev= 72
 4577.47   132.5    4612  132.32 4615.77   132.3 4642.58   129.9 4669.39   130.2
 4688.54   129.8 4700.03   130.3 4702.79  130.62 4715.35   132.1 4730.67   132.5
 4742.16   132.3 4744.31   132.3 4744.92  132.36 4749.59  132.85 4762.54  132.92
 4788.81  133.07 4799.08  133.02 4829.18  132.87 4846.19  132.66 4871.47  132.34
 4882.19  132.12  4903.1  131.69 4917.58  132.13 4923.09   132.3 4927.54  129.94
 4927.75  129.83 4927.84  129.79 4928.32  129.53 4928.43  129.47 4928.54  129.42
 4945.61  120.38 4946.92  120.09 4973.88  114.08 4976.94  112.37 4983.38  110.84
 4985.06  112.84  4986.6  114.68 4989.58  112.12  5002.6   117.2  5013.4  114.08
    5018  119.94 5028.04  120.65 5029.26  120.74 5030.72  122.34 5050.71  126.37
 5055.54  127.99 5058.87  129.11 5058.98  129.15 5064.57  131.03 5069.19  131.86
  5069.3  131.88 5069.41   131.9 5069.48  131.91 5079.59  133.72 5106.78  133.44
 5117.12  133.34 5156.49  133.02 5159.86  132.99 5197.09  132.57 5202.22  132.57
    5238  132.55 5241.67  132.42 5262.51   131.7 5270.02   131.9 5270.17   131.9
 5327.62  131.94 5339.11  131.95 5346.77  131.96 5358.26  131.96 5408.43     132
 5483.96  132.32 5548.23   132.6
BR U #Mann= 4
 4577.47      .2    4612      .1 4923.09    .035 5064.57      .1
BR U Banks=4923.09,5064.57
BR D #Sta/Elev= 72
 4577.47   132.4    4612  132.22 4615.77   132.2 4642.58   129.8 4669.39   130.1
 4688.54   129.7 4700.03   130.2 4702.79  130.52 4715.35     132 4730.67   132.4
 4742.16   132.2 4744.31   132.2 4744.92  132.26 4749.59  132.75 4762.54  132.82
 4788.81  132.97 4799.08  132.92 4829.18  132.77 4846.19  132.56 4871.47  132.24
 4882.19  132.02  4903.1  131.59 4917.58  132.03 4923.09   132.2 4927.54  129.84
 4927.75  129.73 4927.84  129.69 4928.32  129.43 4928.43  129.37 4928.54  129.32
 4945.61  120.28 4946.92  119.99 4973.88  113.98 4976.94  112.27 4983.38  110.74
 4985.06  112.74  4986.6  114.58 4989.58  112.02  5002.6   117.1  5013.4  113.98
    5018  119.84 5028.04  120.55 5029.26  120.64 5030.72  122.24 5050.71  126.27
 5055.54  127.89 5058.87  129.01 5058.98  129.05 5064.57  130.93 5069.19  131.76
  5069.3  131.78 5069.41   131.8 5069.48  131.81 5079.59  133.62 5106.78  133.34
 5117.12  133.24 5156.49  132.92 5159.86  132.89 5197.09  132.47 5202.22  132.47
    5238  132.45 5241.67  132.32 5262.51   131.6 5270.02   131.8 5270.17   131.8
 5327.62  131.84 5339.11  131.85 5346.77  131.86 5358.26  131.86 5408.43   131.9
 5483.96  132.22 5548.23   132.5
BR D #Mann= 4
 4577.47      .2    4612      .1 4923.09    .035 5064.57      .1
BR D Banks=4923.09,5064.57
BC Design=,, 0 ,, 0 ,,,,,,
BC HTab HWMax=133.73
BC Use User HTab Curves=0
BC User HTab FreeFlow(D)= 0

Type RM Length L Ch R = 1 ,29787.0 ,738.4,738.4,738.4
BEGIN DESCRIPTION:
Downstream Section of Bridge/Culvert/Weir
END DESCRIPTION:
XS GIS Cut Line= 6
      2996172.97     13850708.57      2996130.05     13850673.57
      2995972.88     13850632.45      2995725.87     13850529.67
      2995492.13     13850358.92      2995328.37     13850252.07
#Sta/Elev= 30
 4577.47   132.4    4612  132.22 4642.58   129.8 4669.39   130.1 4688.54   129.7
 4700.03   130.2 4715.35     132 4730.67   132.4 4744.31   132.2 4749.59  132.75
 4829.18  132.77  4903.1  131.59 4923.09   132.2 4945.61  120.28 4973.88  113.98
 4976.94  112.27 4983.38  110.74  4986.6  114.58 4989.58  112.02  5002.6   117.1
  5013.4  113.98    5018  119.84 5029.26  120.64 5030.72  122.24 5050.71  126.27
 5064.57  130.93 5079.59  133.62    5238  132.45 5262.51   131.6 5548.23   132.5
#Mann= 4 , 1 , 0
 4577.47      .2       0    4612      .1       0 4923.09    .035       0
 5064.57      .1       0
#XS Ineff= 2 , 0
       0  4925.2     131  5063.9       0   130.6
Permanent Ineff=
       F       F
Bank Sta=4923.09,5064.57
XS Rating Curve= 0 ,0
Exp/Cntr=0.5,0.3

Type RM Length L Ch R = 1 ,29048.6 ,191.9,194.6,198.1
BEGIN DESCRIPTION:
Cross Section 29048.6-Interpolated
END DESCRIPTION:
XS GIS Cut Line= 6
      2996546.81     13850636.61      2996582.72     13850528.88
      2996527.66     13850351.71       2996470.2      13850155.4
      2996451.05     13850083.57      2996355.28     13849937.53
#Sta/Elev= 27
  4694.1   133.1  4752.4  133.57  4769.2   133.7  4807.7   133.3  4863.7   132.3
  4933.8  130.38  4978.3  116.75  4987.9  115.91  4992.7  112.64  4994.1  111.13
    4999  110.41  5006.2  111.72  5007.3  112.58  5011.9  116.84  5027.6  118.93
  5063.8   130.5  5114.4   131.8  5176.9   132.8  5192.6   132.6  5197.7   132.7
  5198.3   132.8  5208.1   132.8  5249.4  132.48  5293.6   132.2  5302.2   131.8
  5369.4   130.8  5446.7   130.5
#Mann= 5 , 1 , 0
  4694.1      .2       0  4752.4     .06       0  4933.8    .035       0
  5063.8      .1       0  5249.4      .2       0
Bank Sta=4933.8,5063.8
XS Rating Curve= 0 ,0
Exp/Cntr=0.3,0.1

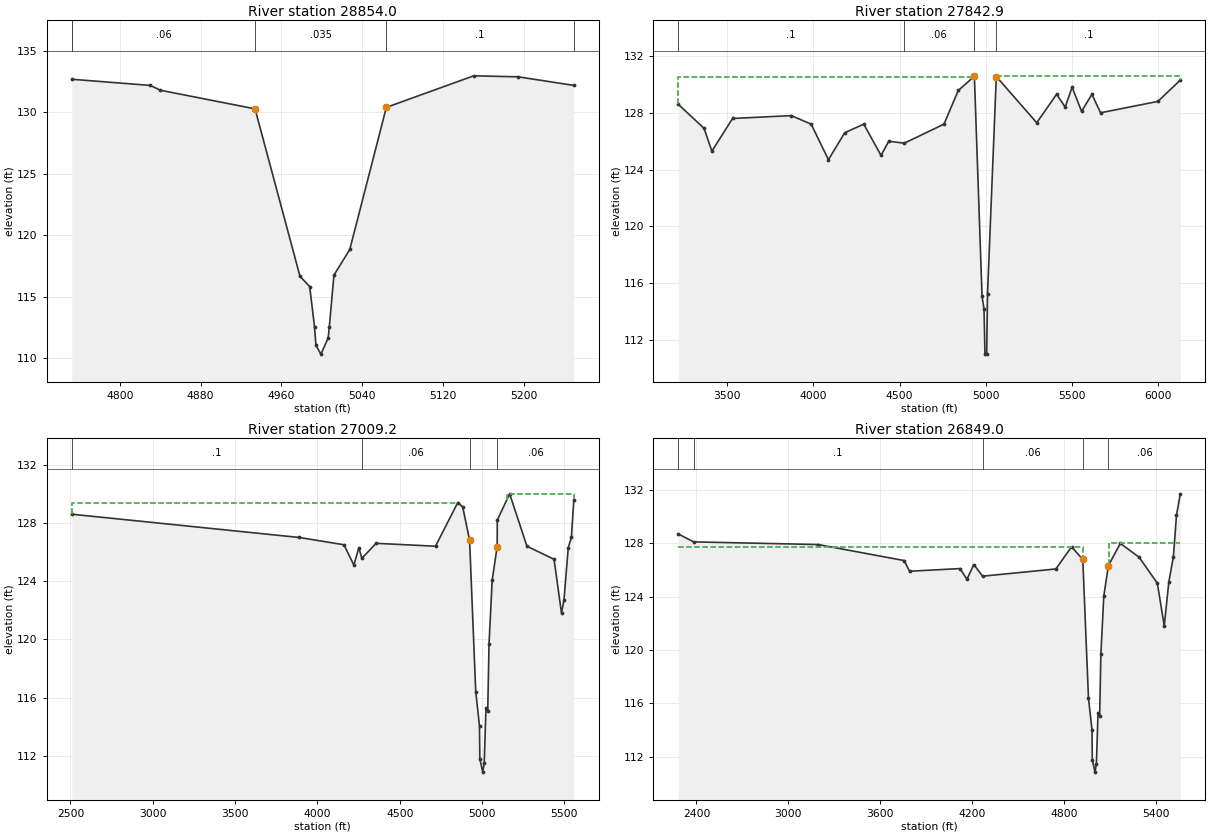
Type RM Length L Ch R = 1 ,28854.0 ,1016.7,1011.1,999.6
BEGIN DESCRIPTION:
Cross Section 28854.0
END DESCRIPTION:
XS GIS Cut Line= 4
      2996725.46     13850530.88      2996755.36     13850459.11
      2996665.65     13850106.26      2996653.69     13850052.44
#Sta/Elev= 17
  4752.4   132.7  4830.1   132.2    4840  131.81  4933.8  130.29  4978.3  116.66
  4987.9  115.82  4992.7  112.55  4994.1  111.04    4999  110.32  5006.2  111.63
  5007.3  112.49  5011.9  116.75  5027.6  118.84  5063.8  130.41  5150.2  132.98
  5194.2   132.9  5249.4   132.2
#Mann= 5 , 1 , 0
  4752.4      .2       0  4752.4     .06       0  4933.8    .035       0
  5063.8      .1       0  5249.4      .2       0
Bank Sta=4933.8,5063.8
XS Rating Curve= 0 ,0
Exp/Cntr=0.3,0.1

Type RM Length L Ch R = 1 ,27842.9 ,772.1,833.7,867.9
BEGIN DESCRIPTION:
Cross Section 27842.9
END DESCRIPTION:
XS GIS Cut Line= 6
      2998226.55     13851607.45       2998059.1     13850973.43
      2997718.22      13850094.3      2997580.66     13849729.49
      2997275.66     13849280.96      2997092.81     13848947.91
#Sta/Elev= 30
  3216.9   128.6  3366.9   126.9  3411.9   125.3  3531.9   127.6  3872.6   127.8
  3987.6   127.2  4087.6   124.7  4182.6   126.6  4292.6   127.2  4392.6     125
  4437.6     126  4527.1  125.86  4757.6   127.2  4840.6  129.57  4933.9  130.57
  4978.4  115.09  4989.7   114.2  4995.3  111.02  5005.3  111.05    5010  115.25
    5061  130.55  5295.4   127.3  5410.4   129.3  5460.4   128.4  5500.4   129.8
  5555.4   128.1  5615.4   129.3  5665.4     128  5997.8   128.8  6127.8   130.3
#Mann= 4 , 1 , 0
  3216.9      .1       0  4527.1     .06       0  4933.9    .035       0
    5061      .1       0
#XS Ineff= 2 , 0
       0    4929   130.5    5063       0   130.6
Permanent Ineff=
       F       F
Bank Sta=4933.9,5061
XS Rating Curve= 0 ,0
Exp/Cntr=0.3,0.1

Type RM Length L Ch R = 1 ,27009.2 ,160.2,160.2,160.2
BEGIN DESCRIPTION:
Cross Section  27009.2-Interpolated
END DESCRIPTION:
XS GIS Cut Line= 6
       2998190.8     13852094.07      2998353.75     13851415.92
      2998365.96     13850854.49      2998429.78     13849687.67
      2998438.96     13849262.05      2998440.76     13849065.36
#Sta/Elev= 30
  2507.8   128.6  3891.2     127  4161.5   126.5  4221.6   125.1  4251.7   126.3
    4270  125.57  4356.8   126.6  4717.4   126.4  4852.6   129.4  4882.6   129.1
  4924.4  126.82  4961.8  116.41  4984.7  114.04  4986.6   111.8  5004.3  110.88
  5013.4  111.51  5023.9  115.29  5034.7  115.11  5042.6   119.7  5061.7  124.07
    5092  126.36  5092.8   128.2  5167.8     130  5272.8   126.4  5437.8   125.5
  5482.8   121.8  5497.8   122.7  5523.8   126.3  5542.8     127  5557.8   129.6
#Mann= 4 , 1 , 0
  2507.8      .1       0    4270     .06       0  4924.4    .035       0
    5092     .06       0
#XS Ineff= 2 , 0
       0    4856   129.4    5150       0     130
Permanent Ineff=
       F       F
Bank Sta=4924.4,5092
XS Rating Curve= 0 ,0
Exp/Cntr=0.5,0.3

Type RM Length L Ch R = 1 ,26849.0 ,80,80,80
BEGIN DESCRIPTION:
Upstream Section of Bridge/Culvert/Weir
END DESCRIPTION:
XS GIS Cut Line= 5
       2998491.9     13852284.09      2998520.38     13851077.69
      2998575.31     13849942.61      2998581.41     13849552.04
      2998598.49     13849005.37
#Sta/Elev= 30
    2281   128.7    2381   128.1  3195.8   127.9  3757.4   126.7  3792.4   125.9
  4122.4   126.1  4167.4   125.3  4212.4   126.4    4270  125.53  4748.3  126.07
  4851.2  127.73  4924.4  126.79  4961.7  116.38  4984.7  114.01  4986.6  111.77
  5004.3  110.85  5013.4  111.48  5023.9  115.26  5034.7  115.08  5042.6  119.67
  5061.7  124.04    5092  126.33  5169.9  127.99  5293.3  126.94  5411.7     125
  5456.7   121.8  5486.7   125.1  5516.7     127  5536.7   130.1  5561.7   131.7
#Mann= 5 , 1 , 0
    2281      .2       0    2381      .1       0    4270     .06       0
  4924.4    .035       0    5092     .06       0
#XS Ineff= 2 , 0
       0    4925   127.7    5095       0     128
Permanent Ineff=
       F       F
Bank Sta=4924.4,5092
XS Rating Curve= 0 ,0
Exp/Cntr=0.5,0.3