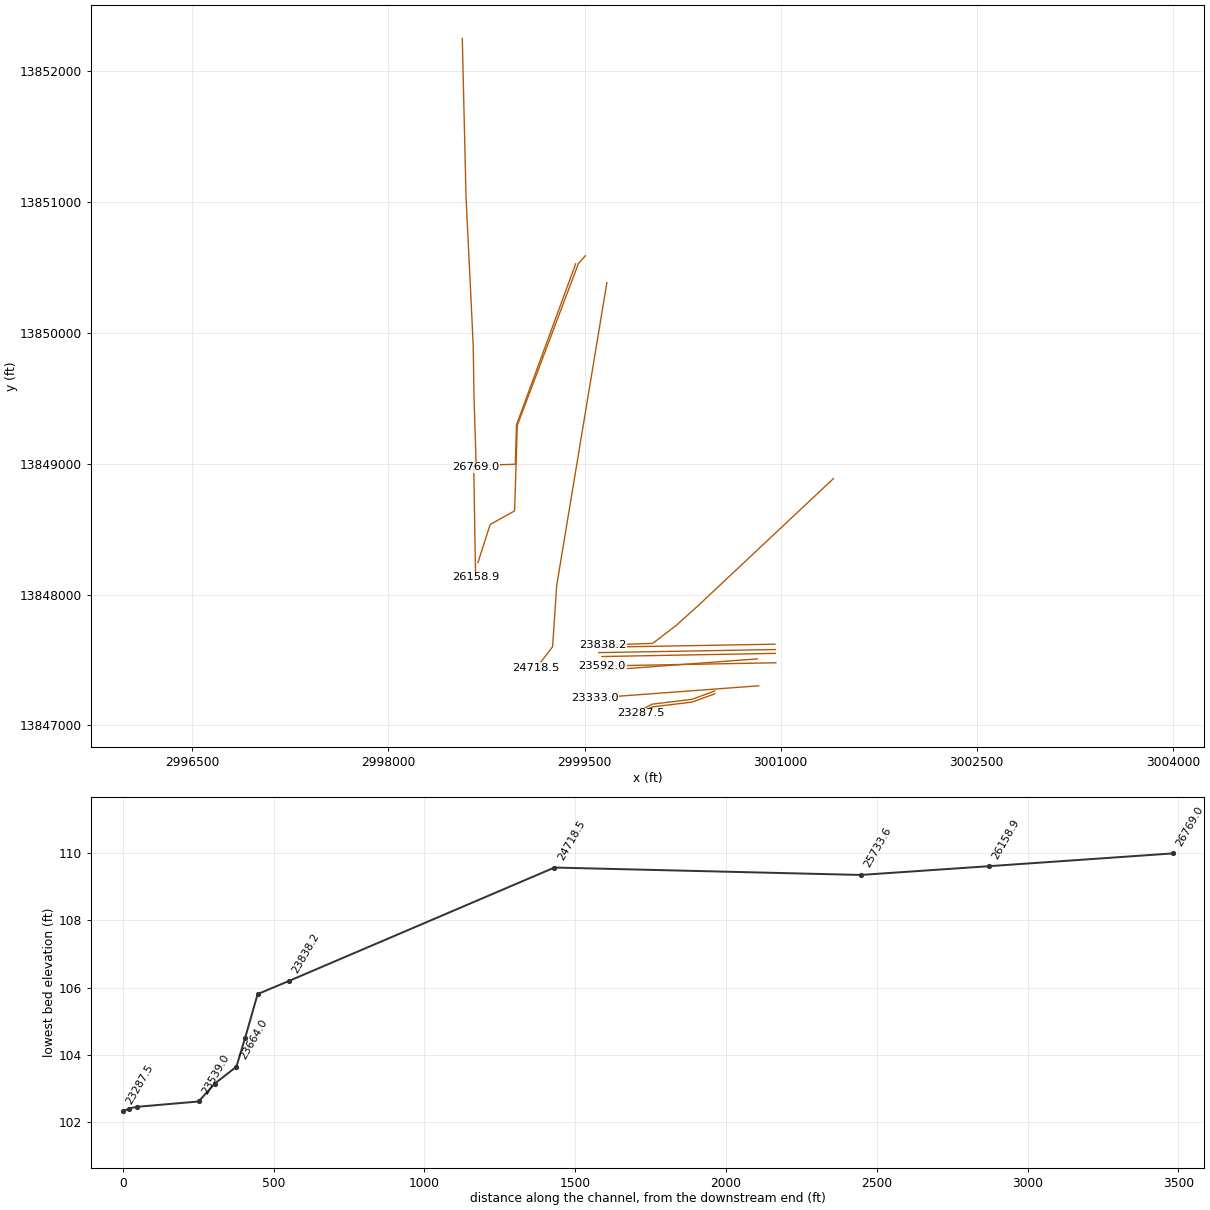
HEC-RAS study T101-00-00.PRJ: T101-00-00

--- T101-00-00.g01 (geometry) --- (continued)

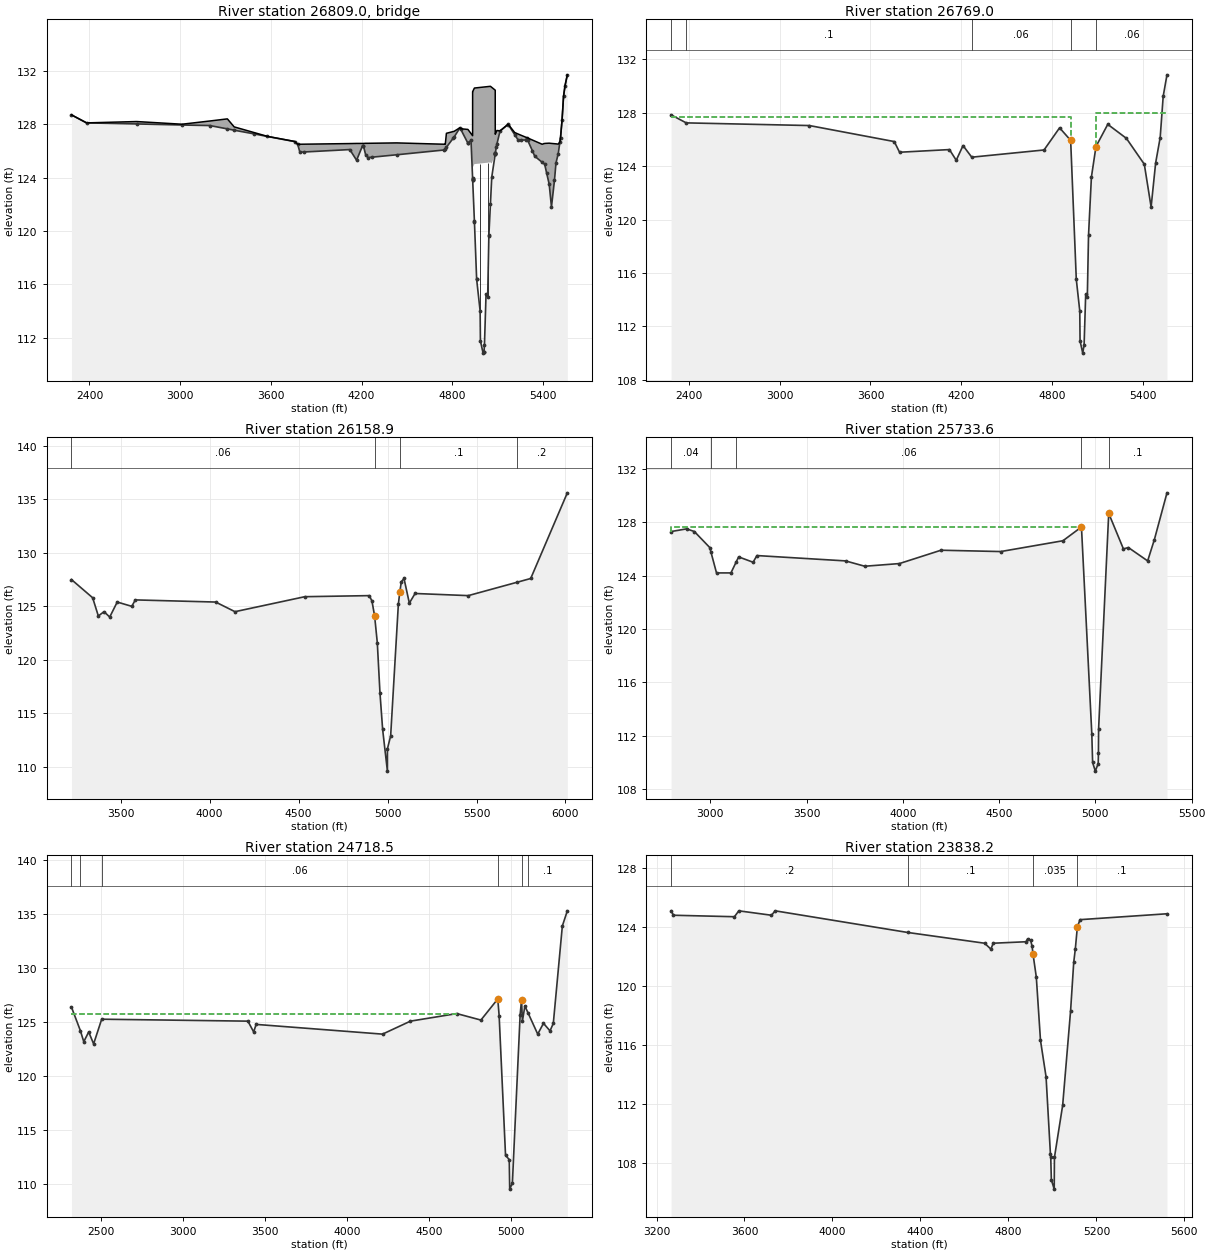
Type RM Length L Ch R = 3 ,26809.0 ,,,
BEGIN DESCRIPTION:
MASON ROAD
Structure ID: T01-17
END DESCRIPTION:
Bridge Culvert--1,0,-1,-1, 0
Deck Dist Width WeirC Skew NumUp NumDn MinLoCord MaxHiCord MaxSubmerge Is_Ogee
10,60,2.6,0, 57, 57, , , 0.95, 0, 1,1,,
    2281    2381  2712.5  3012.5  3195.8  3312.5  3357.5  3577.7  3757.4  3777.4
  3792.4  4122.4  4167.4  4207.4  4212.4  4227.4  4242.4  4432.7  4748.3  4754.2
  4761.7  4813.3  4851.2    4855  4903.9  4924.4 4934.97 4935.08 4935.31  4935.4
  4946.8  5052.9  5061.7  5084.7 5084.81    5092  5095.8  5116.5  5169.9  5213.3
    5237  5288.1  5293.3    5346  5394.8  5411.7  5441.7  5456.7  5476.7  5486.7
  5501.7  5512.5  5516.7  5526.7  5536.7  5546.7  5561.7
   128.7   128.1   128.2     128  128.24   128.4   127.8  127.09  126.71   126.5
   126.5  126.55  126.56  126.56  126.56  126.57  126.57   126.6   126.5   126.5
  127.32  127.47  127.74  127.66  127.61   127.3  127.14  130.44  130.44  130.44
  130.71  130.84  130.76  130.55  127.25  127.43  127.53   127.5     128  127.38
  127.26  127.02     127  126.74   126.5  126.56  126.58  126.56  126.54  126.53
  126.51  126.67     127   128.3   130.1   130.9   131.7
   128.7   128.1  128.02  127.94   127.9  127.65  127.55  127.08   126.7   126.5
   125.9   126.1   125.3   126.4   126.4   125.7   125.5  125.71  126.07  126.16
  126.27  127.05  127.73  127.65  126.58  126.79  123.94  123.92  123.85  124.74
  125.01  125.14  125.06  125.78  125.79  126.33  126.51  127.49  127.99  127.22
   126.8  126.82  126.94   125.6  125.15     125   123.5   121.8   123.8   125.1
   125.8  126.66     127   128.3   130.1   130.9   131.7
    2281    2381  2712.5  3012.5  3195.8  3312.5  3357.5  3577.7  3757.4  3777.4
  3792.4  4122.4  4167.4  4207.4  4212.4  4227.4  4242.4  4432.7  4748.3  4754.2
  4761.7  4813.3  4851.2    4855  4903.9  4924.4 4934.97 4935.08 4935.31  4935.4
  4946.8  5052.9  5061.7  5084.7 5084.81    5092  5095.8  5116.5  5169.9  5213.3
    5237  5288.1  5293.3    5346  5394.8  5411.7  5441.7  5456.7  5476.7  5486.7
  5501.7  5512.5  5516.7  5526.7  5536.7  5546.7  5561.7
   128.7   128.1   128.2     128  128.24   128.4   127.8  127.09  126.71   126.5
   126.5  126.55  126.56  126.56  126.56  126.57  126.57   126.6   126.5   126.5
  127.32  127.47  127.74  127.66  127.61   127.3  127.14  130.44  130.44  130.44
  130.71  130.84  130.76  130.55  127.25  127.43  127.53   127.5     128  127.38
  127.26  127.02     127  126.74   126.5  126.56  126.58  126.56  126.54  126.53
  126.51  126.67     127   128.3   130.1   130.9   131.7
  127.85  127.25  127.17  127.09  127.05   126.8   126.7  126.23  125.85  125.65
  125.05  125.25  124.45  125.55  125.55  124.85  124.65  124.86  125.22  125.31
  125.42   126.2  126.88   126.8  125.73  125.94  123.09  123.07     123  123.89
  124.16  124.29  124.21  124.93  124.94  125.48  125.66  126.64  127.14  126.37
  125.95  125.97  126.09  124.75   124.3  124.15  122.65  120.95  122.95  124.25
  124.95  125.81  126.15  127.45  129.25  130.05  130.85
Pier Skew, UpSta & Num, DnSta & Num=  ,4984.7, 2 ,4984.7, 2 , 0 , 0 , 0 ,,
     1.4     1.4
  112.18  126.06
     1.4     1.4
  111.33  125.21
Pier Skew, UpSta & Num, DnSta & Num=  ,5034.7, 2 ,5034.7, 2 , 0 , 0 , 0 ,,
     1.4     1.4
  114.09  126.12
     1.4     1.4
  113.24  125.27
Abutment Skew #Up #Dn= , 2 , 2
  4935.2  4961.8
  124.74  116.37
  4935.2  4961.8
  123.89  115.52
Abutment Skew #Up #Dn= , 2 , 2
  5042.6 5085.49
  119.67  125.82
  5042.6 5085.49
  118.82  124.97
BR Coef= 1 , 1 , 0 ,1.25, 0 ,,,0.8,0,2,0,
WSPro=,,,, 1 ,,,, 0 ,,,, 0 ,,,,-1 ,-1 ,-1 , 0 , 0 , 0 , 0 , 0
BR U #Sta/Elev= 85
    2281   128.7    2381   128.1  2712.5  128.02  3012.5  127.94  3195.8   127.9
  3312.5  127.65  3357.5  127.55  3487.7  127.28  3577.7  127.08  3757.4   126.7
  3777.4   126.5  3792.4   125.9  3822.7  125.92  4122.4   126.1  4167.4   125.3
  4207.4   126.4  4212.4   126.4  4227.4   125.7  4242.4   125.5    4270  125.53
  4432.7  125.71  4748.3  126.07  4754.2  126.16  4761.7  126.27  4806.6  126.95
  4813.3  127.05  4851.2  127.73    4855  127.65  4902.4  126.61  4903.9  126.58
  4924.4  126.79 4934.97  123.94 4935.08  123.92 4935.19  123.89 4935.31  123.85
  4935.4  123.83  4946.8  120.76  4947.1  120.68  4961.7  116.38  4961.8  116.37
  4984.7  114.01  4986.6  111.77  5004.3  110.85  5007.2  110.91  5010.3  110.92
  5013.4  111.48  5023.9  115.26  5034.7  115.08  5042.5  119.61  5042.6  119.67
  5052.9  122.03  5061.7  124.04 5084.59  125.77  5084.7  125.78 5084.81  125.79
 5085.29  125.82  5085.4  125.83  5085.5  125.84    5092  126.33  5095.8  126.51
  5116.5  127.49  5166.1  127.95  5169.9  127.99  5213.3  127.22    5237   126.8
  5257.3  126.81  5288.1  126.82  5293.3  126.94  5299.4  126.79    5331     126
    5346   125.6  5394.8  125.15  5411.7     125  5424.8  124.34  5441.7   123.5
  5456.7   121.8  5476.7   123.8  5486.7   125.1  5501.7   125.8  5512.5  126.66
  5516.7     127  5526.7   128.3  5536.7   130.1  5546.7   130.9  5561.7   131.7
BR U #Mann= 5
    2281      .2    2381      .1    4270     .06  4924.4    .035    5092     .06
BR U Banks=4924.4,5092
BR D #Sta/Elev= 85
    2281  127.85    2381  127.25  2712.5  127.17  3012.5  127.09  3195.8  127.05
  3312.5   126.8  3357.5   126.7  3487.7  126.43  3577.7  126.23  3757.4  125.85
  3777.4  125.65  3792.4  125.05  3822.7  125.07  4122.4  125.25  4167.4  124.45
  4207.4  125.55  4212.4  125.55  4227.4  124.85  4242.4  124.65    4270  124.68
  4432.7  124.86  4748.3  125.22  4754.2  125.31  4761.7  125.42  4806.6   126.1
  4813.3   126.2  4851.2  126.88    4855   126.8  4902.4  125.76  4903.9  125.73
  4924.4  125.94 4934.97  123.09 4935.08  123.07 4935.19  123.04 4935.31     123
  4935.4  122.98  4946.8  119.91  4947.1  119.83  4961.7  115.53  4961.8  115.52
  4984.7  113.16  4986.6  110.92  5004.3     110  5007.2  110.06  5010.3  110.07
  5013.4  110.63  5023.9  114.41  5034.7  114.23  5042.5  118.76  5042.6  118.82
  5052.9  121.18  5061.7  123.19 5084.59  124.92  5084.7  124.93 5084.81  124.94
 5085.29  124.97  5085.4  124.98  5085.5  124.99    5092  125.48  5095.8  125.66
  5116.5  126.64  5166.1   127.1  5169.9  127.14  5213.3  126.37    5237  125.95
  5257.3  125.96  5288.1  125.97  5293.3  126.09  5299.4  125.94    5331  125.15
    5346  124.75  5394.8   124.3  5411.7  124.15  5424.8  123.49  5441.7  122.65
  5456.7  120.95  5476.7  122.95  5486.7  124.25  5501.7  124.95  5512.5  125.81
  5516.7  126.15  5526.7  127.45  5536.7  129.25  5546.7  130.05  5561.7  130.85
BR D #Mann= 5
    2281      .2    2381      .1    4270     .06  4924.4    .035    5092     .06
BR D Banks=4924.4,5092
BC Design=,, 0 ,, 0 ,,,,,,
BC HTab HWMax=131.7
BC Use User HTab Curves=0
BC User HTab FreeFlow(D)= 0

Type RM Length L Ch R = 1 ,26769.0 ,610.1,610.1,610.1
BEGIN DESCRIPTION:
Downstream Section of Bridge/Culvert/Weir
END DESCRIPTION:
XS GIS Cut Line= 5
      2998564.65     13852250.83      2998593.14     13851044.43
      2998648.07     13849909.35      2998654.17     13849518.78
      2998671.25     13848972.11
#Sta/Elev= 30
    2281  127.84    2381  127.24  3195.8  127.04  3757.4  125.84  3792.4  125.04
  4122.4  125.24  4167.4  124.44  4212.4  125.54    4270  124.67  4748.3  125.21
  4851.2  126.87  4924.4  125.93  4961.7  115.52  4984.7  113.15  4986.6  110.91
  5004.3  109.99  5013.4  110.62  5023.9   114.4  5034.7  114.22  5042.6  118.81
  5061.7  123.18    5092  125.47  5169.9  127.13  5293.3  126.08  5411.7  124.14
  5456.7  120.94  5486.7  124.24  5516.7  126.14  5536.7  129.24  5561.7  130.84
#Mann= 5 , 1 , 0
    2281      .2       0    2381      .1       0    4270     .06       0
  4924.4    .035       0    5092     .06       0
#XS Ineff= 2 , 0
       0    4925   127.7    5095       0     128
Permanent Ineff=
       F       F
Bank Sta=4924.4,5092
XS Rating Curve= 0 ,0
Exp/Cntr=0.5,0.3

Type RM Length L Ch R = 1 ,26158.9 ,338.5,425.3,451.5
BEGIN DESCRIPTION:
Cross Section 26158.9-Interpolated
END DESCRIPTION:
XS GIS Cut Line= 6
      2999432.31     13850527.69      2998979.49     13849297.02
      2998970.24      13848995.7      2998807.56     13848990.15
      2998652.28     13848986.46      2998666.51     13848131.06
#Sta/Elev= 30
    3224   127.5  3343.1   125.8    3375   124.1    3407   124.5    3439     124
  3481.1   125.4  3562.9     125  3582.8   125.6  4034.2   125.4  4142.8   124.5
  4535.3   125.9  4897.5     126  4912.5   125.5  4927.5   124.1  4942.6   121.6
  4957.6   116.9  4972.6   113.5  4999.4  109.61  4999.5   111.7  5017.6   112.9
  5060.9   125.2  5069.2  126.35  5077.6   127.3  5092.6   127.6  5122.6   125.3
  5154.9   126.2  5453.7     126  5726.2  127.24  5804.6   127.6  6010.4   135.6
#Mann= 4 , 1 , 0
    3224     .06       0  4927.5    .035       0  5069.2      .1       0
  5726.2      .2       0
#XS Ineff= 2 , 0
       0  4897.5     126               0
Permanent Ineff=
       F       F
Bank Sta=4927.5,5069.2
XS Rating Curve= 0 ,0
Exp/Cntr=0.3,0.1

Type RM Length L Ch R = 1 ,25733.6 ,654.4,1015.1,1101.4
BEGIN DESCRIPTION:
Cross Section 25733.6
END DESCRIPTION:
XS GIS Cut Line= 6
       2999506.2     13850589.49      2999452.84     13850528.86
      2998985.58     13849293.22      2998964.82     13848639.06
      2998777.91     13848535.23      2998684.46     13848244.48
#Sta/Elev= 30
  2796.3   127.3  2877.1   127.5  2917.1   127.3  2997.1   126.1  3003.5  125.75
  3032.1   124.2  3107.1   124.2  3133.3  124.99  3147.1   125.4  3222.1     125
  3242.1   125.5  3702.1   125.1  3802.1   124.7  3982.1   124.9  4198.1   125.9
  4508.1   125.8  4831.4  126.61  4927.6  127.64  4981.3  112.16  4985.6     110
  4999.5  109.35  5014.6  109.92  5015.7   110.7  5016.6  112.51  5069.2  128.66
  5145.5     126  5171.4   126.1  5271.4   125.1  5306.4   126.7  5371.8   130.2
#Mann= 5 , 1 , 0
  2796.3     .04       0  3003.5      .1       0  3133.3     .06       0
  4927.6    .035       0  5069.2      .1       0
#XS Ineff= 2 , 0
       0  4927.6  127.64  5069.2       0  128.66
Permanent Ineff=
       F       F
Bank Sta=4927.6,5069.2
XS Rating Curve= 0 ,0
Exp/Cntr=0.3,0.1

Type RM Length L Ch R = 1 ,24718.5 ,1057.7,880.3,804.6
BEGIN DESCRIPTION:
Cross Section 24718.5
END DESCRIPTION:
XS GIS Cut Line= 5
       2999670.9      13850383.5      2999670.89     13850383.49
      2999286.71     13848067.97      2999255.55     13847600.71
      2999130.36     13847437.81
#Sta/Elev= 30
  2322.2   126.4  2376.3  124.23  2397.2   123.2  2427.2   124.1  2457.2     123
  2506.4  125.28  3397.2   125.1  3432.2   124.1  3447.2   124.8  4217.2   123.9
  4387.2   125.1  4669.4   125.8  4816.6   125.2  4919.3  127.15  4927.6  125.62
  4966.6   112.7  4989.2   112.3    4992  109.57  5008.3  110.12  5055.6   125.7
  5064.1  127.05  5069.4   125.1  5084.4   126.5  5105.1  125.82  5162.7   123.9
  5197.7   124.9  5237.7   124.2  5257.7   124.9  5312.7   133.9  5343.1   135.3
#Mann= 6 , 1 , 0
  2322.2     .04       0  2376.3      .1       0  2506.4     .06       0
  4919.3    .035       0  5064.1     .06       0  5105.1      .1       0
#XS Ineff= 2 , 0
       0    4675   125.8    5085       0  126.44
Permanent Ineff=
       F       F
Bank Sta=4919.3,5064.1
XS Rating Curve= 0 ,0
Exp/Cntr=0.3,0.1

Type RM Length L Ch R = 1 ,23838.2 ,103.7,103.7,103.7
BEGIN DESCRIPTION:
Cross Section 23838.2-Interpolated
END DESCRIPTION:
XS GIS Cut Line= 6
      3001403.98     13848885.95      3000364.55     13847910.73
      3000201.28     13847763.97      3000036.18     13847637.39
      3000019.67     13847626.38       2999638.1     13847613.54
#Sta/Elev= 30
  3266.4   125.1    3277   124.8  3554.4   124.7  3574.2   125.1  3722.7   124.8
  3739.5   125.1  4342.2  123.63  4691.7   122.9  4720.3   122.5  4730.9   122.9
  4879.6     123  4887.4   123.2  4900.9   123.1  4907.6   122.7  4911.5   122.2
  4926.8   120.6  4945.8   116.3  4971.1  113.83  4990.9  108.61  4992.4  108.38
  4995.2  106.83  5008.2   106.2  5009.2  108.35  5046.6  111.89  5082.6   118.3
  5096.9   121.6  5104.1   122.5  5113.4     124  5125.5   124.5  5520.9   124.9
#Mann= 4 , 1 , 0
  3266.4      .2       0  4342.2      .1       0  4911.5    .035       0
  5113.4      .1       0
Bank Sta=4911.5,5113.4
XS Rating Curve= 0 ,0
Exp/Cntr=0.5,0.3

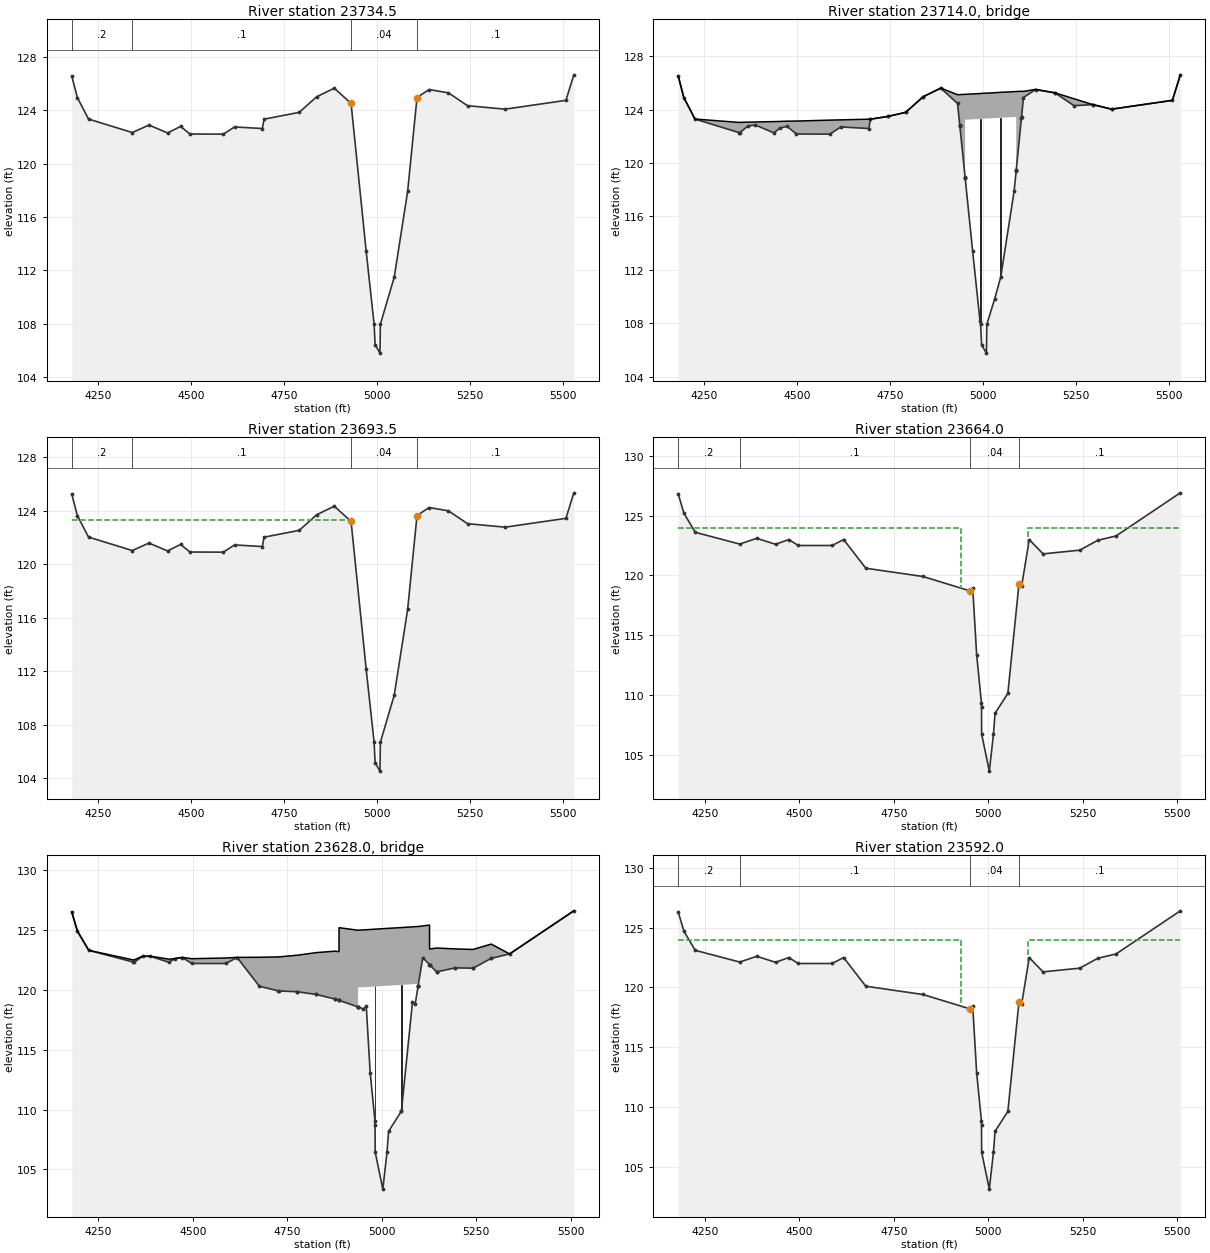
Type RM Length L Ch R = 1 ,23734.5 ,41,41,41
BEGIN DESCRIPTION:
Upstream Section of Bridge/Culvert/Weir
END DESCRIPTION:
XS GIS Cut Line= 2
       3000956.8      13847620.4        2999607.     13847596.81
#Sta/Elev= 30
  4179.5  126.55  4194.5  124.94  4224.5  123.33  4342.2  122.32  4387.1  122.88
  4437.1  122.29  4472.1  122.78  4497.1  122.21  4587.1   122.2  4617.1  122.74
  4692.1  122.62  4696.4  123.32  4790.9  123.83  4838.1     125  4885.3  125.64
  4930.5   124.5  4971.1  113.44  4992.4  107.99  4995.2  106.44  5008.2  105.81
  5009.2  107.96  5046.6   111.5  5082.6  117.91  5107.8  124.94  5140.3  125.54
  5192.4  125.29  5243.6  124.33  5344.8  124.07  5508.2  124.73  5529.5  126.64
#Mann= 4 , 1 , 0
  4179.5      .2       0  4342.2      .1       0  4930.5     .04       0
  5107.8      .1       0
#XS Ineff= 2 , 0
       0    4930   123.4    5108       0   123.5
Permanent Ineff=
       F       F
Bank Sta=4930.5,5107.8
XS Rating Curve= 0 ,0
Exp/Cntr=0.5,0.3

Type RM Length L Ch R = 3 ,23714.0 ,,,
BEGIN DESCRIPTION:
MISSOURI KANSAS TEXAS RAILROAD
Structure ID: T01-15
END DESCRIPTION:
Bridge Culvert--1,0,-1,-1, 0
Deck Dist Width WeirC Skew NumUp NumDn MinLoCord MaxHiCord MaxSubmerge Is_Ogee
10,21,2.6,0, 56, 56, , , 0.95, 0, 1,1,,
  4179.5  4194.5  4224.5  4342.2  4344.5  4367.1  4387.1  4437.1  4452.1  4472.1
  4497.1  4587.1  4617.1  4692.1  4696.3  4696.4  4743.8  4743.9  4790.8  4790.9
  4838.1  4838.2  4885.3  4930.5 4936.49  4936.6 4936.71 4950.81  4950.9    4951
  4971.1  4990.9  4992.4  4995.2  5008.2  5009.2  5030.6  5046.6  5082.6  5088.2
 5088.29  5088.4 5102.29  5102.4 5102.51  5107.8  5140.3  5192.3  5192.4  5243.6
  5294.4  5294.5  5344.7  5344.8  5508.2  5529.5
  126.51   124.9  123.29  123.04  123.04  123.06  123.07   123.1  123.11  123.13
  123.14  123.21  123.23  123.28  123.28  123.28  123.49  123.49  123.79  123.79
  124.96  124.96  125.61  125.11  125.12  125.12  125.12  125.14  125.14  125.14
  125.17   125.2   125.2  125.21  125.23  125.23  125.26  125.29  125.34  125.35
  125.35  125.35  125.37  125.37  125.37  125.36  125.51  125.25  125.25  124.81
  124.37  124.37  124.03  124.03  124.69   126.6
  126.51   124.9  123.29  122.28  122.26  122.77  122.84  122.25  122.61  122.74
  122.17  122.16   122.7  122.58  123.26  123.28  123.49  123.49  123.79  123.79
  124.96  124.96   125.6  124.46  122.83   122.8  122.77  118.93  123.24  123.24
  123.27   123.3   123.3  123.31  123.33  123.33  123.36  123.39  123.44  123.45
  123.45  119.49  123.36  123.39  123.42   124.9   125.5  125.25  125.25  124.29
  124.37  124.37  124.03  124.03  124.69   126.6
  4179.5  4194.5  4224.5  4342.2  4344.5  4367.1  4387.1  4437.1  4452.1  4472.1
  4497.1  4587.1  4617.1  4692.1  4696.3  4696.4  4743.8  4743.9  4790.8  4790.9
  4838.1  4838.2  4885.3  4930.5 4936.49  4936.6 4936.71 4950.81  4950.9    4951
  4971.1  4990.9  4992.4  4995.2  5008.2  5009.2  5030.6  5046.6  5082.6  5088.2
 5088.29  5088.4 5102.29  5102.4 5102.51  5107.8  5140.3  5192.3  5192.4  5243.6
  5294.4  5294.5  5344.7  5344.8  5508.2  5529.5
  126.51   124.9  123.29  123.04  123.04  123.06  123.07   123.1  123.11  123.13
  123.14  123.21  123.23  123.28  123.28  123.28  123.49  123.49  123.79  123.79
  124.96  124.96  125.61  125.11  125.12  125.12  125.12  125.14  125.14  125.14
  125.17   125.2   125.2  125.21  125.23  125.23  125.26  125.29  125.34  125.35
  125.35  125.35  125.37  125.37  125.37  125.36  125.51  125.25  125.25  124.81
  124.37  124.37  124.03  124.03  124.69   126.6
  125.56  123.95  122.34  121.33  121.31  121.82  121.89   121.3  121.66  121.79
  121.22  121.21  121.75  121.63  122.31  122.33  122.54  122.54  122.84  122.84
  124.01  124.01  124.65  123.51  121.88  121.85  121.82  117.98  122.29  122.29
  122.32  122.35  122.35  122.36  122.38  122.38  122.41  122.44  122.49   122.5
   122.5  118.54  122.41  122.44  122.47  123.95  124.55   124.3   124.3  123.34
  123.42  123.42  123.08  123.08  123.74  125.65
Pier Skew, UpSta & Num, DnSta & Num=  ,4992.4, 2 ,4992.4, 2 , 0 , 0 , 0 ,,
       2       2
   106.4   124.3
       2       2
  105.45  123.35
Pier Skew, UpSta & Num, DnSta & Num=  ,5046.6, 2 ,5046.6, 2 , 0 , 0 , 0 ,,
       2       2
  110.36  124.39
       2       2
  109.41  123.44
BR Coef= 1 , 1 , 0 ,1.25, 0 ,,,0.8,0,2,0,
WSPro=,,,, 1 ,,,, 0 ,,,, 0 ,,,,-1 ,-1 ,-1 , 0 , 0 , 0 , 0 , 0
BR U #Sta/Elev= 56
  4179.5  126.51  4194.5   124.9  4224.5  123.29  4342.2  122.28  4344.5  122.26
  4367.1  122.77  4387.1  122.84  4437.1  122.25  4452.1  122.61  4472.1  122.74
  4497.1  122.17  4587.1  122.16  4617.1   122.7  4692.1  122.58  4696.3  123.26
  4696.4  123.28  4743.8  123.49  4743.9  123.49  4790.8  123.79  4790.9  123.79
  4838.1  124.96  4838.2  124.96  4885.3   125.6  4930.5  124.46 4936.49  122.83
  4936.6   122.8 4936.71  122.77 4950.81  118.93  4950.9   118.9    4951  118.88
  4971.1   113.4  4990.9  108.18  4992.4  107.95  4995.2   106.4  5008.2  105.77
  5009.2  107.92  5030.6  109.85  5046.6  111.46  5082.6  117.87  5088.2  119.43
 5088.29  119.46  5088.4  119.49 5102.29  123.36  5102.4  123.39 5102.51  123.42
  5107.8   124.9  5140.3   125.5  5192.3  125.25  5192.4  125.25  5243.6  124.29
  5294.4  124.37  5294.5  124.37  5344.7  124.03  5344.8  124.03  5508.2  124.69
  5529.5   126.6
BR U #Mann= 4
  4179.5      .2  4342.2      .1  4930.5     .04  5107.8      .1
BR U Banks=4930.5,5107.8
BR D #Sta/Elev= 56
  4179.5  125.56  4194.5  123.95  4224.5  122.34  4342.2  121.33  4344.5  121.31
  4367.1  121.82  4387.1  121.89  4437.1   121.3  4452.1  121.66  4472.1  121.79
  4497.1  121.22  4587.1  121.21  4617.1  121.75  4692.1  121.63  4696.3  122.31
  4696.4  122.33  4743.8  122.54  4743.9  122.54  4790.8  122.84  4790.9  122.84
  4838.1  124.01  4838.2  124.01  4885.3  124.65  4930.5  123.51 4936.49  121.88
  4936.6  121.85 4936.71  121.82 4950.81  117.98  4950.9  117.95    4951  117.93
  4971.1  112.45  4990.9  107.23  4992.4     107  4995.2  105.45  5008.2  104.82
  5009.2  106.97  5030.6   108.9  5046.6  110.51  5082.6  116.92  5088.2  118.48
 5088.29  118.51  5088.4  118.54 5102.29  122.41  5102.4  122.44 5102.51  122.47
  5107.8  123.95  5140.3  124.55  5192.3   124.3  5192.4   124.3  5243.6  123.34
  5294.4  123.42  5294.5  123.42  5344.7  123.08  5344.8  123.08  5508.2  123.74
  5529.5  125.65
BR D #Mann= 4
  4179.5      .2  4342.2      .1  4930.5     .04  5107.8      .1
BR D Banks=4930.5,5107.8
BC Design=,, 0 ,, 0 ,,,,,,
BC HTab HWMax=126.64
BC Use User HTab Curves=0
BC User HTab FreeFlow(D)= 0

Type RM Length L Ch R = 1 ,23693.5 ,29.5,29.5,29.5
BEGIN DESCRIPTION:
Downstream Section of Bridge/Culvert/Weir
END DESCRIPTION:
XS GIS Cut Line= 2
      3000958.87     13847579.45      2999609.08     13847555.86
#Sta/Elev= 30
  4179.5  125.26  4194.5  123.65  4224.5  122.04  4342.2  121.03  4387.1  121.59
  4437.1     121  4472.1  121.49  4497.1  120.92  4587.1  120.91  4617.1  121.45
  4692.1  121.33  4696.4  122.03  4790.9  122.54  4838.1  123.71  4885.3  124.35
  4930.5  123.21  4971.1  112.15  4992.4   106.7  4995.2  105.15  5008.2  104.52
  5009.2  106.67  5046.6  110.21  5082.6  116.62  5107.8  123.65  5140.3  124.25
  5192.4     124  5243.6  123.04  5344.8  122.78  5508.2  123.44  5529.5  125.35
#Mann= 4 , 1 , 0
  4179.5      .2       0  4342.2      .1       0  4930.5     .04       0
  5107.8      .1       0
#XS Ineff= 2 , 0
       0    4930   123.3    5108       0   123.4
Permanent Ineff=
       F       F
Bank Sta=4930.5,5107.8
XS Rating Curve= 0 ,0
Exp/Cntr=0.5,0.3

Type RM Length L Ch R = 1 ,23664.0 ,72,72,72
BEGIN DESCRIPTION:
Upstream Section of Bridge/Culvert/Weir
END DESCRIPTION:
XS GIS Cut Line= 2
      3000960.38     13847550.19       2999631.9     13847526.02
#Sta/Elev= 30
  4179.5   126.8  4194.5   125.2  4224.5   123.6  4342.2  122.62  4387.1   123.1
  4437.1   122.6  4472.1     123  4497.1   122.5  4587.1   122.5  4617.1     123
  4675.9   120.6    4827  119.91  4951.4  118.71  4958.9  118.91  4969.2  113.38
  4981.8  109.37  4982.1  109.03  4982.5  106.74  5002.7  103.65  5013.8  106.76
  5017.9  108.48  5051.8  110.14  5081.1  119.25  5088.4  119.13  5108.4  122.99
    5145   121.8  5242.1  122.11  5289.4  122.93  5338.3   123.3  5508.2   126.9
#Mann= 4 , 1 , 0
  4179.5      .2       0  4342.2      .1       0  4951.4     .04       0
  5081.1      .1       0
#XS Ineff= 2 , 0
       0    4927     124    5106       0     124
Permanent Ineff=
       F       F
Bank Sta=4951.4,5081.1
XS Rating Curve= 0 ,0
Exp/Cntr=0.5,0.3

Type RM Length L Ch R = 3 ,23628.0 ,,,
BEGIN DESCRIPTION:
I-10 WEST ACCESS
Structure ID: T01-15
END DESCRIPTION:
Bridge Culvert--1,0,-1,-1, 0
Deck Dist Width WeirC Skew NumUp NumDn MinLoCord MaxHiCord MaxSubmerge Is_Ogee
10,52,2.6,0, 60, 60, , , 0.95, 0, 1,1,,
  4179.5  4194.5  4224.5  4342.2  4344.5  4367.1  4387.1  4437.1  4452.1  4472.1
  4497.1  4587.1  4617.1  4675.9  4726.4    4727  4775.7  4776.1  4826.9    4827
  4876.6  4876.7 4886.79  4886.9 4887.01  4936.9 4937.01  4937.1  4937.2  4951.4
  4958.9  4969.2  4981.8  4982.1  4982.5  5002.7  5013.8  5017.9  5051.6  5051.8
  5081.1  5088.4  5095.9 5095.99  5096.1  5096.2  5108.4 5126.19  5126.3 5126.41
    5145  5145.3  5193.6  5193.8  5241.3  5242.1  5289.4  5289.6  5338.3  5508.2
   126.5   124.9   123.3   122.5   122.5  122.81  122.81  122.56  122.61  122.71
   122.6  122.66  122.71  122.72  122.75  122.75  122.89  122.89  123.11  123.11
  123.23  123.23  123.19  125.19  125.19  124.98  124.98  124.98  124.98  125.01
  125.02  125.04  125.07  125.07  125.07  125.11  125.13  125.14   125.2   125.2
  125.26  125.28  125.29  125.29  125.29  125.29  125.34  125.41  125.41  123.41
  123.49  123.49  123.42  123.42  123.37  123.38  123.82  123.82     123   126.6
   126.5   124.9   123.3  122.32   122.3   122.8   122.8   122.3   122.6   122.7
   122.2   122.2   122.7   120.3  119.91  119.91  119.84  119.84  119.61  119.61
  119.23  119.23  119.12  119.12  119.12  118.57  118.57  120.19  120.19  120.22
  120.23  120.25  120.28  120.28  120.28  120.32  120.34  120.35  120.41  120.41
  120.47  120.49   120.5   120.5  120.32  120.34  122.69  122.11  122.11   122.1
   121.5   121.5  121.83  121.83  121.81  121.81  122.63  122.63     123   126.6
  4179.5  4194.5  4224.5  4342.2  4344.5  4367.1  4387.1  4437.1  4452.1  4472.1
  4497.1  4587.1  4617.1  4675.9  4726.4    4727  4775.7  4776.1  4826.9    4827
  4876.6  4876.7 4886.79  4886.9 4887.01  4936.9 4937.01  4937.1  4937.2  4951.4
  4958.9  4969.2  4981.8  4982.1  4982.5  5002.7  5013.8  5017.9  5051.6  5051.8
  5081.1  5088.4  5095.9 5095.99  5096.1  5096.2  5108.4 5126.19  5126.3 5126.41
    5145  5145.3  5193.6  5193.8  5241.3  5242.1  5289.4  5289.6  5338.3  5508.2
   126.5   124.9   123.3   122.5   122.5  122.81  122.81  122.56  122.61  122.71
   122.6  122.66  122.71  122.72  122.75  122.75  122.89  122.89  123.11  123.11
  123.23  123.23  123.19  125.19  125.19  124.98  124.98  124.98  124.98  125.01
  125.02  125.04  125.07  125.07  125.07  125.11  125.13  125.14   125.2   125.2
  125.26  125.28  125.29  125.29  125.29  125.29  125.34  125.41  125.41  123.41
  123.49  123.49  123.42  123.42  123.37  123.38  123.82  123.82     123   126.6
   126.4   124.8   123.2  122.22   122.2   122.7   122.7   122.2   122.5   122.6
   122.1   122.1   122.6   120.2  119.81  119.81  119.74  119.74  119.51  119.51
  119.13  119.13  119.02  119.02  119.02  118.47  118.47  120.09  120.09  120.12
  120.13  120.15  120.18  120.18  120.18  120.22  120.24  120.25  120.31  120.31
  120.37  120.39   120.4   120.4  120.22  120.24  122.59  122.01  122.01     122
   121.4   121.4  121.73  121.73  121.71  121.71  122.53  122.53   122.9   126.5
Pier Skew, UpSta & Num, DnSta & Num=  ,4981.8, 2 ,4981.8, 2 , 0 , 0 , 0 ,,
     1.4     1.4
  105.44  121.28
     1.4     1.4
  105.34  121.18
Pier Skew, UpSta & Num, DnSta & Num=  ,5051.6, 2 ,5051.6, 2 , 0 , 0 , 0 ,,
     1.4     1.4
  108.82  121.41
     1.4     1.4
  108.72  121.31
BR Coef= 1 , 1 , 0 ,1.25, 0 ,,,0.8,0,2,0,
WSPro=,,,, 1 ,,,, 0 ,,,, 0 ,,,,-1 ,-1 ,-1 , 0 , 0 , 0 , 0 , 0
BR U #Sta/Elev= 60
  4179.5   126.5  4194.5   124.9  4224.5   123.3  4342.2  122.32  4344.5   122.3
  4367.1   122.8  4387.1   122.8  4437.1   122.3  4452.1   122.6  4472.1   122.7
  4497.1   122.2  4587.1   122.2  4617.1   122.7  4675.9   120.3  4726.4  119.91
    4727  119.91  4775.7  119.84  4776.1  119.84  4826.9  119.61    4827  119.61
  4876.6  119.23  4876.7  119.23 4886.79  119.12  4886.9  119.12 4887.01  119.12
  4936.9  118.57 4937.01  118.57  4937.1  118.57  4937.2  118.57  4951.4  118.41
  4958.9  118.61  4969.2  113.08  4981.8  109.07  4982.1  108.73  4982.5  106.44
  5002.7  103.35  5013.8  106.46  5017.9  108.18  5051.6  109.85  5051.8  109.84
  5081.1  118.95  5088.4  118.83  5095.9  120.28 5095.99  120.29  5096.1  120.32
  5096.2  120.34  5108.4  122.69 5126.19  122.11  5126.3  122.11 5126.41   122.1
    5145   121.5  5145.3   121.5  5193.6  121.83  5193.8  121.83  5241.3  121.81
  5242.1  121.81  5289.4  122.63  5289.6  122.63  5338.3     123  5508.2   126.6
BR U #Mann= 4
  4179.5      .2  4342.2      .1  4951.4     .04  5081.1      .1
BR U Banks=4951.4,5081.1
BR D #Sta/Elev= 60
  4179.5   126.4  4194.5   124.8  4224.5   123.2  4342.2  122.22  4344.5   122.2
  4367.1   122.7  4387.1   122.7  4437.1   122.2  4452.1   122.5  4472.1   122.6
  4497.1   122.1  4587.1   122.1  4617.1   122.6  4675.9   120.2  4726.4  119.81
    4727  119.81  4775.7  119.74  4776.1  119.74  4826.9  119.51    4827  119.51
  4876.6  119.13  4876.7  119.13 4886.79  119.02  4886.9  119.02 4887.01  119.02
  4936.9  118.47 4937.01  118.47  4937.1  118.47  4937.2  118.47  4951.4  118.31
  4958.9  118.51  4969.2  112.98  4981.8  108.97  4982.1  108.63  4982.5  106.34
  5002.7  103.25  5013.8  106.36  5017.9  108.08  5051.6  109.75  5051.8  109.74
  5081.1  118.85  5088.4  118.73  5095.9  120.18 5095.99  120.19  5096.1  120.22
  5096.2  120.24  5108.4  122.59 5126.19  122.01  5126.3  122.01 5126.41     122
    5145   121.4  5145.3   121.4  5193.6  121.73  5193.8  121.73  5241.3  121.71
  5242.1  121.71  5289.4  122.53  5289.6  122.53  5338.3   122.9  5508.2   126.5
BR D #Mann= 4
  4179.5      .2  4342.2      .1  4951.4     .04  5081.1      .1
BR D Banks=4951.4,5081.1
BC Design=,, 0 ,, 0 ,,,,,,
BC HTab HWMax=126.9
BC Use User HTab Curves=0
BC User HTab FreeFlow(D)= 0

Type RM Length L Ch R = 1 ,23592.0 ,53,53,53
BEGIN DESCRIPTION:
Downstream Section of Bridge/Culvert/Weir
END DESCRIPTION:
XS GIS Cut Line= 2
      3000964.02     13847478.28      2999635.54     13847454.11
#Sta/Elev= 30
  4179.5   126.3  4194.5   124.7  4224.5   123.1  4342.2  122.12  4387.1   122.6
  4437.1   122.1  4472.1   122.5  4497.1     122  4587.1     122  4617.1   122.5
  4675.9   120.1    4827  119.41  4951.4  118.21  4958.9  118.41  4969.2  112.88
  4981.8  108.87  4982.1  108.53  4982.5  106.24  5002.7  103.15  5013.8  106.26
  5017.9  107.98  5051.8  109.64  5081.1  118.75  5088.4  118.63  5108.4  122.49
    5145   121.3  5242.1  121.61  5289.4  122.43  5338.3   122.8  5508.2   126.4
#Mann= 4 , 1 , 0
  4179.5      .2       0  4342.2      .1       0  4951.4     .04       0
  5081.1      .1       0
#XS Ineff= 2 , 0
       0    4927     124    5106       0     124
Permanent Ineff=
       F       F
Bank Sta=4951.4,5081.1
XS Rating Curve= 0 ,0
Exp/Cntr=0.5,0.3

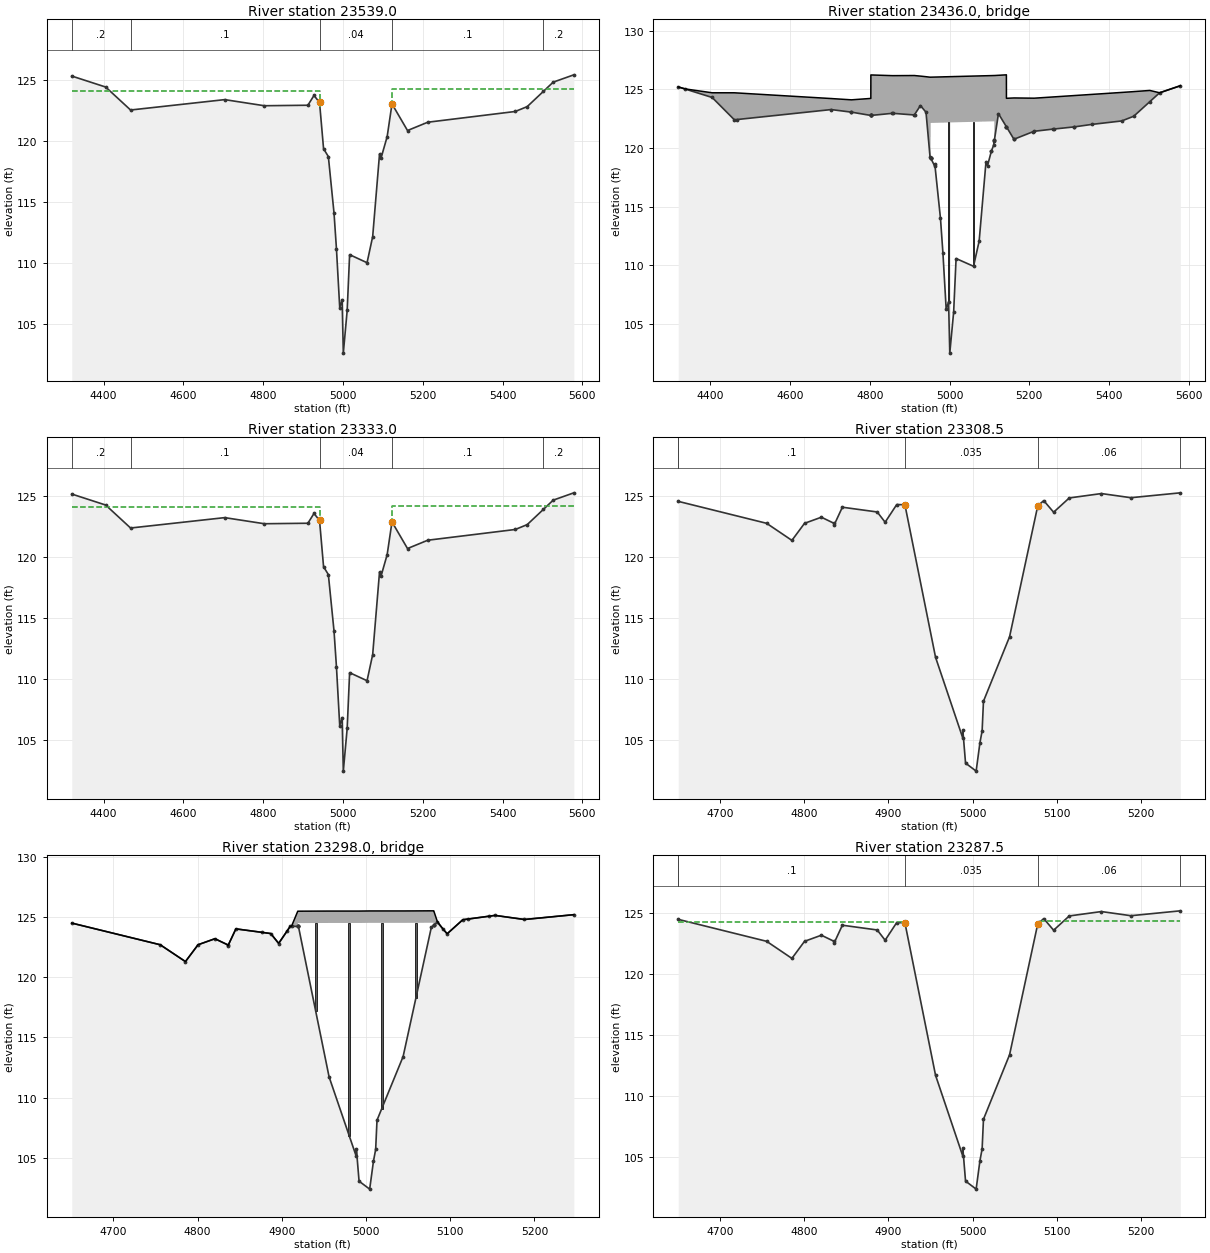
Type RM Length L Ch R = 1 ,23539.0 ,206,206,206
BEGIN DESCRIPTION:
Upstream Section of Bridge/Culvert/Weir
END DESCRIPTION:
XS GIS Cut Line= 2
      3000821.98     13847508.06      2999567.04     13847414.82
#Sta/Elev= 30
  4320.1   125.3  4405.1   124.4  4467.5  122.52  4703.4  123.37  4802.7  122.87
  4911.9  122.91  4927.2  123.71  4941.1  123.14  4951.2  119.35  4963.2  118.71
  4977.4  114.09  4983.5  111.16  4991.7  106.34  4997.7     107  5000.7  102.62
  5010.4  106.12  5016.5  110.68  5060.2  110.02  5074.3  112.16  5091.5  118.93
  5095.3  118.59  5110.6  120.34  5122.7  123.02  5161.6  120.84  5212.3  121.52
  5431.7   122.4  5461.7   122.8    5502  124.04  5526.7   124.8  5578.5   125.4
#Mann= 5 , 1 , 0
  4320.1      .2       0  4467.5      .1       0  4941.1     .04       0
  5122.7      .1       0    5502      .2       0
#XS Ineff= 2 , 0
       0    4942   124.1    5122       0   124.2
Permanent Ineff=
       F       F
Bank Sta=4941.1,5122.7
XS Rating Curve= 0 ,0
Exp/Cntr=0.5,0.3

Type RM Length L Ch R = 3 ,23436.0 ,,,
BEGIN DESCRIPTION:
I-10/U.S. ROUTE 90
Structure ID: T01-12
END DESCRIPTION:
Bridge Culvert--1,0,-1,-1, 0
Deck Dist Width WeirC Skew NumUp NumDn MinLoCord MaxHiCord MaxSubmerge Is_Ogee
10,186,2.6,0, 27, 27, , , 0.95, 0, 1,1,,
  4320.1  4337.5  4405.1  4460.7  4703.4  4754.2 4802.79  4802.9  4856.8  4911.9
  4927.2  4941.1  4951.2 4952.61  4952.7 5112.29  5112.4  5122.7  5142.6 5142.71
  5161.6  5212.3  5431.7  5461.7    5502  5526.7  5578.5
   125.2  125.03   124.7   124.7  124.21   124.1  124.22  126.22  126.16  126.17
  126.12  126.07  126.03  126.03  126.03  126.17  126.17  126.19  126.23  124.23
  124.26  124.24  124.73   124.8   124.9   124.7   125.3
   125.2  125.02   124.3   122.4  123.27  123.05  122.77  122.77  122.95  122.81
  123.61  123.04  119.25  119.15  122.13  122.27  120.64  122.92   121.8   121.8
  120.74  121.42   122.3   122.7  123.94   124.7   125.3
  4320.1  4337.5  4405.1  4460.7  4703.4  4754.2 4802.79  4802.9  4856.8  4911.9
  4927.2  4941.1  4951.2 4952.61  4952.7 5112.29  5112.4  5122.7  5142.6 5142.71
  5161.6  5212.3  5431.7  5461.7    5502  5526.7  5578.5
   125.2  125.03   124.7   124.7  124.21   124.1  124.22  126.22  126.16  126.17
  126.12  126.07  126.03  126.03  126.03  126.17  126.17  126.19  126.23  124.23
  124.26  124.24  124.73   124.8   124.9   124.7   125.3
  125.16  124.98  124.26  122.36  123.23  123.01  122.73  122.73  122.91  122.77
  123.57     123  119.21  119.11  122.09  122.23   120.6  122.88  121.76  121.76
   120.7  121.38  122.26  122.66   123.9  124.66  125.26
Pier Skew, UpSta & Num, DnSta & Num=  ,4997.7, 2 ,4997.7, 2 , 0 , 0 , 0 ,,
     1.4     1.4
  104.88  123.17
     1.4     1.4
  104.84  123.13
Pier Skew, UpSta & Num, DnSta & Num=  ,5060.2, 2 ,5060.2, 2 , 0 , 0 , 0 ,,
     1.4     1.4
  108.93  123.22
     1.4     1.4
  108.89  123.18
Abutment Skew #Up #Dn= , 2 , 2
    5105 5112.49
  119.73  122.27
    5105 5112.49
  119.69  122.23
BR Coef= 1 , 1 , 0 ,1.25, 0 ,,,0.8,0,2,0,
WSPro=,,,, 1 ,,,, 0 ,,,, 0 ,,,,-1 ,-1 ,-1 , 0 , 0 , 0 , 0 , 0
BR U #Sta/Elev= 61
  4320.1   125.2  4337.5  125.02  4405.1   124.3  4460.7   122.4  4467.5  122.42
  4703.4  123.27  4754.2  123.05  4754.3  123.05  4802.7  122.77 4802.79  122.77
  4802.9  122.77 4803.01  122.77  4803.3  122.77  4856.8  122.95  4857.6  122.95
  4911.9  122.81  4912.4  122.84  4927.2  123.61  4941.1  123.04  4951.2  119.25
  4952.5  119.16 4952.61  119.15  4952.7  119.15  4952.8  119.14    4963  118.45
  4963.2  118.61  4977.4  113.99  4983.5  111.06  4991.7  106.24  4997.7   106.9
  5000.7  102.52  5010.4  106.02  5016.5  110.58  5060.2  109.92  5074.3  112.06
  5091.5  118.83  5095.3  118.49  5104.9  119.72    5105  119.73  5110.6  120.24
 5112.29  120.61  5112.4  120.64  5112.5  120.66  5122.7  122.92 5142.49  121.81
  5142.6   121.8 5142.71   121.8  5161.5  120.74  5161.6  120.74  5209.8  121.39
  5212.3  121.42  5260.6  121.61  5261.3  121.61  5311.6  121.79  5311.7  121.79
  5357.8  122.01  5431.7   122.3  5461.7   122.7    5502  123.94  5526.7   124.7
  5578.5   125.3
BR U #Mann= 5
  4320.1      .2  4467.5      .1  4941.1     .04  5122.7      .1    5502      .2
BR U Banks=4941.1,5122.7
BR D #Sta/Elev= 61
  4320.1  125.16  4337.5  124.98  4405.1  124.26  4460.7  122.36  4467.5  122.38
  4703.4  123.23  4754.2  123.01  4754.3  123.01  4802.7  122.73 4802.79  122.73
  4802.9  122.73 4803.01  122.73  4803.3  122.73  4856.8  122.91  4857.6  122.91
  4911.9  122.77  4912.4   122.8  4927.2  123.57  4941.1     123  4951.2  119.21
  4952.5  119.12 4952.61  119.11  4952.7  119.11  4952.8   119.1    4963  118.41
  4963.2  118.57  4977.4  113.95  4983.5  111.02  4991.7   106.2  4997.7  106.86
  5000.7  102.48  5010.4  105.98  5016.5  110.54  5060.2  109.88  5074.3  112.02
  5091.5  118.79  5095.3  118.45  5104.9  119.68    5105  119.69  5110.6   120.2
 5112.29  120.57  5112.4   120.6  5112.5  120.62  5122.7  122.88 5142.49  121.77
  5142.6  121.76 5142.71  121.76  5161.5   120.7  5161.6   120.7  5209.8  121.35
  5212.3  121.38  5260.6  121.57  5261.3  121.57  5311.6  121.75  5311.7  121.75
  5357.8  121.97  5431.7  122.26  5461.7  122.66    5502   123.9  5526.7  124.66
  5578.5  125.26
BR D #Mann= 5
  4320.1      .2  4467.5      .1  4941.1     .04  5122.7      .1    5502      .2
BR D Banks=4941.1,5122.7
BC Design=,, 0 ,, 0 ,,,,,,
BC HTab HWMax=125.4
BC Use User HTab Curves=0
BC User HTab FreeFlow(D)= 0

Type RM Length L Ch R = 1 ,23333.0 ,24.5,24.5,24.5
BEGIN DESCRIPTION:
Downstream Section of Bridge/Culvert/Weir
END DESCRIPTION:
XS GIS Cut Line= 2
      3000832.41     13847302.33      2999577.47     13847209.08
#Sta/Elev= 30
  4320.1  125.14  4405.1  124.24  4467.5  122.36  4703.4  123.21  4802.7  122.71
  4911.9  122.75  4927.2  123.55  4941.1  122.98  4951.2  119.19  4963.2  118.55
  4977.4  113.93  4983.5     111  4991.7  106.18  4997.7  106.84  5000.7  102.46
  5010.4  105.96  5016.5  110.52  5060.2  109.86  5074.3     112  5091.5  118.77
  5095.3  118.43  5110.6  120.18  5122.7  122.86  5161.6  120.68  5212.3  121.36
  5431.7  122.24  5461.7  122.64    5502  123.88  5526.7  124.64  5578.5  125.24
#Mann= 5 , 1 , 0
  4320.1      .2       0  4467.5      .1       0  4941.1     .04       0
  5122.7      .1       0    5502      .2       0
#XS Ineff= 2 , 0
       0    4942   124.1    5122       0   124.2
Permanent Ineff=
       F       F
Bank Sta=4941.1,5122.7
XS Rating Curve= 0 ,0
Exp/Cntr=0.5,0.3

Type RM Length L Ch R = 1 ,23308.5 ,21,21,21
BEGIN DESCRIPTION:
Upstream Section of Bridge/Culvert/Weir
END DESCRIPTION:
XS GIS Cut Line= 4
      3000495.77     13847262.61      3000321.71     13847198.73
      3000016.69       13847162.      2999925.66      13847112.5
#Sta/Elev= 28
  4650.5  124.53  4755.5  122.73  4785.5  121.33  4800.5  122.73  4820.5  123.23
  4835.5  122.73  4835.9  122.63 4845.42  124.05 4886.82  123.66 4896.22  122.82
 4910.02  124.27 4919.72  124.25 4956.12  111.74 4988.32  105.15 4988.52  105.76
 4991.72  103.07 5004.32  102.41 5008.82  104.74 5011.42  105.71 5013.02  108.14
 5044.02  113.43 5077.52  124.17 5084.62  124.59 5096.32  123.64 5114.92  124.81
 5153.12  125.17  5188.1  124.83  5246.8  125.23
#Mann= 5 , 1 , 0
  4650.5      .2       0  4650.5      .1       0 4919.72    .035       0
 5077.52     .06       0  5246.8      .2       0
#XS Ineff= 2 , 0
       0    4919  124.23 5080.42       0  124.32
Permanent Ineff=
       F       F
Bank Sta=4919.72,5077.52
XS Rating Curve= 0 ,0
Exp/Cntr=0.5,0.3

Type RM Length L Ch R = 3 ,23298.0 ,,,
BEGIN DESCRIPTION:
12" PIPELINE
Structure ID: PL1_T01-12
END DESCRIPTION:
Bridge Culvert--1,0,-1,-1, 0
Deck Dist Width WeirC Skew NumUp NumDn MinLoCord MaxHiCord MaxSubmerge Is_Ogee
10,1,2.6,0, 40, 40, , , 0.95, 0, 1,1,,
  4650.5  4755.5  4785.5  4800.5  4820.5  4835.5  4835.9 4845.42  4876.5 4886.82
 4896.22  4906.5 4910.02  4911.5 4918.92 4919.03 4919.12 4919.72 4956.12 4988.32
 4988.52 4991.72 5004.32 5008.82 5011.42 5013.02 5044.02 5077.52 5080.31 5080.42
 5080.52 5084.62  5091.5 5096.32 5114.92  5121.5  5145.9 5153.12  5188.1  5246.8
  124.51  122.71  121.31  122.71  123.21  122.71  122.61  124.03  123.74  123.64
  122.84  123.88  124.25  124.25   125.5   125.5   125.5   125.5  125.51  125.51
  125.51  125.51  125.52  125.52  125.52  125.52  125.52  125.53  125.53  125.53
  125.51  124.65  124.01  123.62  124.79  124.85  125.08  125.15  124.81  125.21
  124.51  122.71  121.31  122.71  123.21  122.71  122.61  124.03  123.74  123.64
   122.8  123.88  124.25  124.25  124.23  124.23  124.51  124.51  124.52  124.52
  124.52  124.52  124.53  124.53  124.53  124.53  124.53  124.54  124.54  124.32
  124.33  124.57  124.01  123.62  124.79  124.85  125.08  125.15  124.81  125.21
  4650.5  4755.5  4785.5  4800.5  4820.5  4835.5  4835.9 4845.42  4876.5 4886.82
 4896.22  4906.5 4910.02  4911.5 4918.92 4919.03 4919.12 4919.72 4956.12 4988.32
 4988.52 4991.72 5004.32 5008.82 5011.42 5013.02 5044.02 5077.52 5080.31 5080.42
 5080.52 5084.62  5091.5 5096.32 5114.92  5121.5  5145.9 5153.12  5188.1  5246.8
   124.5   122.7   121.3   122.7   123.2   122.7   122.6  124.02  123.74  123.64
  122.84  123.88  124.25  124.25   125.5   125.5   125.5   125.5  125.51  125.51
  125.51  125.51  125.52  125.52  125.52  125.52  125.52  125.53  125.53  125.53
  125.51  124.65  124.01  123.62  124.79  124.85  125.08  125.14   124.8   125.2
  124.49  122.69  121.29  122.69  123.19  122.69  122.59  124.01  123.72  123.62
  122.78  123.86  124.23  124.23  124.21  124.21  124.49  124.49   124.5   124.5
   124.5   124.5  124.51  124.51  124.51  124.51  124.51  124.52  124.52   124.3
  124.31  124.55  123.99   123.6  124.77  124.83  125.06  125.13  124.79  125.19
Pier Skew, UpSta & Num, DnSta & Num=  ,4940.2, 2 ,4940.2, 2 , 0 , 0 , 0 ,,
       2       2
  115.84  125.52
       2       2
  115.82   125.5
Pier Skew, UpSta & Num, DnSta & Num=  ,4980.1, 2 ,4980.1, 2 , 0 , 0 , 0 ,,
       2       2
   105.6  125.52
       2       2
  105.58   125.5
Pier Skew, UpSta & Num, DnSta & Num=  ,5018.7, 2 ,5018.7, 2 , 0 , 0 , 0 ,,
       2       2
  107.92  125.53
       2       2
   107.9  125.51
Pier Skew, UpSta & Num, DnSta & Num=  ,5059.2, 2 ,5059.2, 2 , 0 , 0 , 0 ,,
       2       2
  116.96  125.53
       2       2
  116.94  125.51
BR Coef= 1 , 1 , 0 ,1.25, 0 ,,,0.8,0,2,0,
WSPro=,,,, 1 ,,,, 0 ,,,, 0 ,,,,-1 ,-1 ,-1 , 0 , 0 , 0 , 0 , 0
BR U #Sta/Elev= 40
  4650.5  124.51  4755.5  122.71  4785.5  121.31  4800.5  122.71  4820.5  123.21
  4835.5  122.71  4835.9  122.61 4845.42  124.03  4876.5  123.74 4886.82  123.64
 4896.22   122.8  4906.5  123.88 4910.02  124.25  4911.5  124.25 4918.92  124.23
 4919.03  124.23 4919.12  124.23 4919.72  124.23 4956.12  111.72 4988.32  105.13
 4988.52  105.74 4991.72  103.05 5004.32  102.39 5008.82  104.72 5011.42  105.69
 5013.02  108.12 5044.02  113.41 5077.52  124.15 5080.31  124.32 5080.42  124.32
 5080.52  124.33 5084.62  124.57  5091.5  124.01 5096.32  123.62 5114.92  124.79
  5121.5  124.85  5145.9  125.08 5153.12  125.15  5188.1  124.81  5246.8  125.21
BR U #Mann= 5
  4650.5      .2  4650.5      .1 4919.72    .045 5077.52     .06  5246.8      .2
BR U Banks=4919.72,5077.52
BR D #Sta/Elev= 40
  4650.5  124.49  4755.5  122.69  4785.5  121.29  4800.5  122.69  4820.5  123.19
  4835.5  122.69  4835.9  122.59 4845.42  124.01  4876.5  123.72 4886.82  123.62
 4896.22  122.78  4906.5  123.86 4910.02  124.23  4911.5  124.23 4918.92  124.21
 4919.03  124.21 4919.12  124.21 4919.72  124.21 4956.12   111.7 4988.32  105.11
 4988.52  105.72 4991.72  103.03 5004.32  102.37 5008.82   104.7 5011.42  105.67
 5013.02   108.1 5044.02  113.39 5077.52  124.13 5080.31   124.3 5080.42   124.3
 5080.52  124.31 5084.62  124.55  5091.5  123.99 5096.32   123.6 5114.92  124.77
  5121.5  124.83  5145.9  125.06 5153.12  125.13  5188.1  124.79  5246.8  125.19
BR D #Mann= 5
  4650.5      .2  4650.5      .1 4919.72    .045 5077.52     .06  5246.8      .2
BR D Banks=4919.72,5077.52
BC Design=,, 0 ,, 0 ,,,,,,
BC HTab HWMax=125.23
BC Use User HTab Curves=0
BC User HTab FreeFlow(D)= 0

Type RM Length L Ch R = 1 ,23287.5 ,450,450,450
BEGIN DESCRIPTION:
Downstream Section of Bridge/Culvert/Weir
END DESCRIPTION:
XS GIS Cut Line= 4
      3000497.29     13847241.67      3000323.23     13847177.79
      3000018.21     13847141.06      2999927.18     13847091.56
#Sta/Elev= 28
  4650.5  124.45  4755.5  122.65  4785.5  121.25  4800.5  122.65  4820.5  123.15
  4835.5  122.65  4835.9  122.55 4845.42  123.97 4886.82  123.58 4896.22  122.74
 4910.02  124.19 4919.72  124.17 4956.12  111.66 4988.32  105.07 4988.52  105.68
 4991.72  102.99 5004.32  102.33 5008.82  104.66 5011.42  105.63 5013.02  108.06
 5044.02  113.35 5077.52  124.09 5084.62  124.51 5096.32  123.56 5114.92  124.73
 5153.12  125.09  5188.1  124.75  5246.8  125.15
#Mann= 5 , 1 , 0
  4650.5      .2       0  4650.5      .1       0 4919.72    .035       0
 5077.52     .06       0  5246.8      .2       0
#XS Ineff= 2 , 0
       0    4919  124.23 5080.42       0  124.32
Permanent Ineff=
       F       F
Bank Sta=4919.72,5077.52
XS Rating Curve= 0 ,0
Exp/Cntr=0.5,0.3