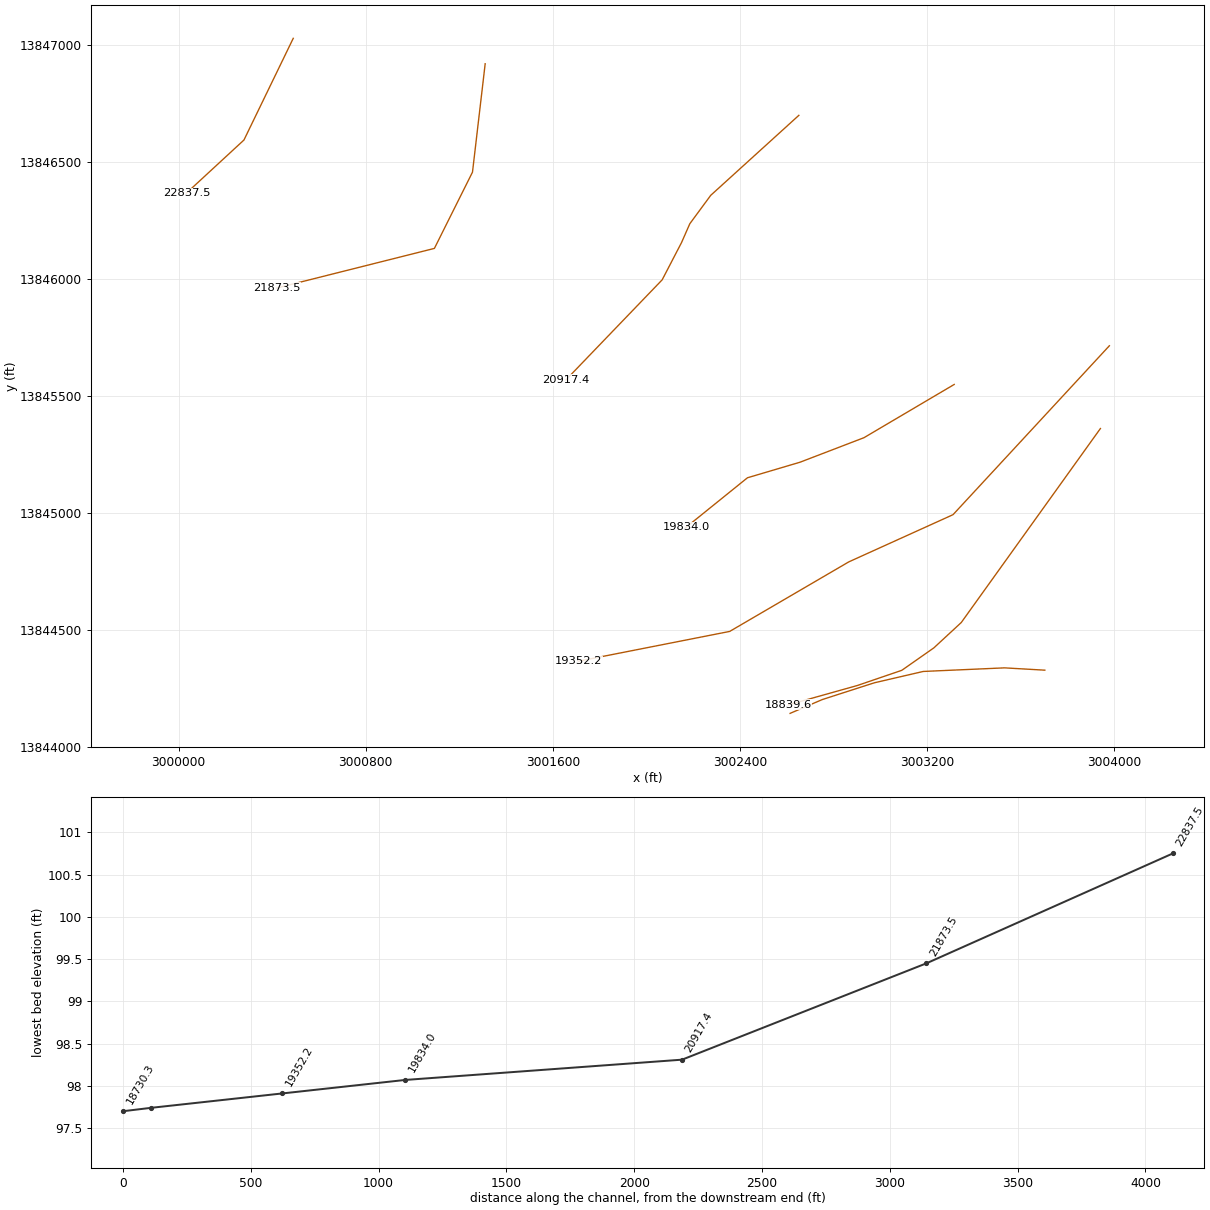
HEC-RAS study T101-00-00.PRJ: T101-00-00

--- T101-00-00.g01 (geometry) --- (continued)

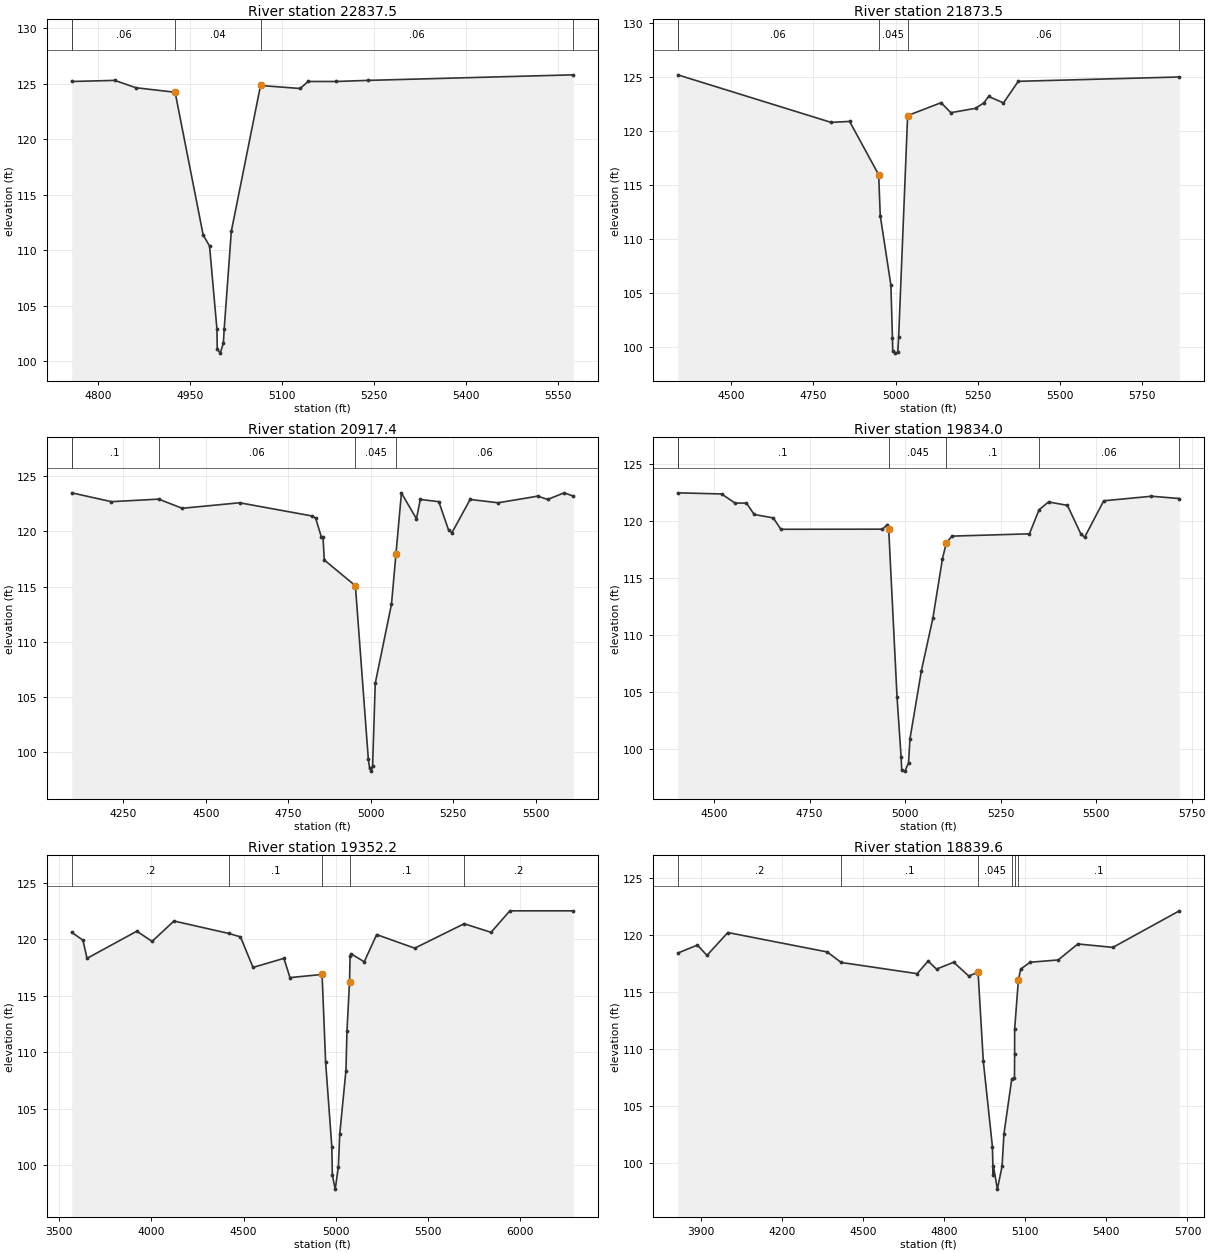
Type RM Length L Ch R = 1 ,22837.5 ,944.8,964,945.9
BEGIN DESCRIPTION:
Cross Section 22837.5
END DESCRIPTION:
XS GIS Cut Line= 3
      3000490.14     13847026.97      3000279.35      13846592.6
      3000033.42     13846365.84
#Sta/Elev= 18
  4757.6   125.2  4827.6   125.3    4862  124.64    4926  124.23  4971.7  111.39
  4982.1  110.39  4994.1  102.95  4994.7   101.1  4999.6  100.75  5004.6  101.65
    5006  102.94  5017.6  111.72  5065.2  124.84  5129.8  124.57  5142.6   125.2
  5187.6   125.2  5240.4   125.3  5574.9   125.8
#Mann= 5 , 1 , 0
  4757.6      .2       0  4757.6     .06       0    4926     .04       0
  5065.2     .06       0  5574.9      .2       0
Bank Sta=4926,5065.2
XS Rating Curve= 0 ,0
Exp/Cntr=0.3,0.1

Type RM Length L Ch R = 1 ,21873.5 ,959.7,956.1,912.6
BEGIN DESCRIPTION:
Cross Section 21873.5
END DESCRIPTION:
XS GIS Cut Line= 4
      3001310.97     13846918.38      3001256.68     13846455.27
      3001093.79     13846129.49      3000419.88     13845960.21
#Sta/Elev= 20
  4337.7   125.2    4804   120.8  4860.3  120.89  4948.7  115.96  4953.5  112.18
  4985.9  105.74  4990.6  100.84  4991.6   99.62  4999.4   99.45  5006.9   99.52
  5009.4   100.9  5036.8  121.43  5138.5  122.62  5168.2   121.7  5243.2   122.1
  5268.2   122.6  5283.2   123.2  5328.2   122.6  5373.2   124.6  5863.1     125
#Mann= 5 , 1 , 0
  4337.7      .2       0  4337.7     .06       0  4948.7    .045       0
  5036.8     .06       0  5863.1      .2       0
Bank Sta=4948.7,5036.8
XS Rating Curve= 0 ,0
Exp/Cntr=0.3,0.1

Type RM Length L Ch R = 1 ,20917.4 ,1083.4,1083.4,1083.4
BEGIN DESCRIPTION:
Cross Section 20917.4
END DESCRIPTION:
XS GIS Cut Line= 6
      3002652.41       13846698.      3002275.53     13846356.25
       3002186.1     13846234.89      3002150.97     13846155.04
      3002067.93     13845995.35      3001655.92     13845567.36
#Sta/Elev= 30
  4093.9   123.5  4213.9   122.7  4357.2  122.93  4428.9   122.1  4602.7   122.6
  4823.4   121.4  4833.4   121.2  4850.6   119.5  4855.6   119.5  4859.5  117.42
  4953.8  115.09    4993   99.41  4996.9   98.58  5002.2   98.31    5006   98.75
    5014  106.26  5063.2  113.41  5076.9     118  5093.4  123.48    5139  121.15
  5150.6   122.9  5206.7   122.7  5236.7   120.1  5246.7   119.9  5301.7   122.9
  5386.7   122.6  5506.7   123.2  5536.7   122.9  5586.7   123.5  5614.7   123.2
#Mann= 5 , 1 , 0
  4093.9      .2       0  4093.9      .1       0  4357.2     .06       0
  4953.8    .045       0  5076.9     .06       0
Bank Sta=4953.8,5076.9
XS Rating Curve= 0 ,0
Exp/Cntr=0.3,0.1

Type RM Length L Ch R = 1 ,19834.0 ,463.5,481.8,480.1
BEGIN DESCRIPTION:
Cross Section 19834.0
END DESCRIPTION:
XS GIS Cut Line= 5
      3003316.74      13845548.2      3002930.92      13845320.8
      3002657.52     13845216.04      3002432.67      13845149.6
      3002169.49     13844937.53
#Sta/Elev= 30
  4404.8   122.5  4519.8   122.4  4554.8   121.6  4584.8   121.6  4604.8   120.6
  4654.8   120.3  4674.8   119.3  4940.5  119.31  4953.8  119.71    4957  119.34
  4978.8   104.6  4989.5   99.32  4991.2   98.16  4999.5   98.07  5008.9    98.8
  5012.7   100.9  5042.7   106.9  5072.7   111.5  5097.7   116.7  5107.7   118.1
  5122.7   118.7  5325.4   118.9  5350.6  121.01  5375.4   121.7  5424.9   121.4
  5459.9   118.9  5469.9   118.6  5519.9   121.8  5644.9   122.2  5717.9     122
#Mann= 6 , 1 , 0
  4404.8      .2       0  4404.8      .1       0    4957    .045       0
  5107.7      .1       0  5350.6     .06       0  5717.9      .2       0
Bank Sta=4957,5107.7
XS Rating Curve= 0 ,0
Exp/Cntr=0.3,0.1

Type RM Length L Ch R = 1 ,19352.2 ,474.6,512.6,514.8
BEGIN DESCRIPTION:
Cross Section 19352.2-Interpolated
END DESCRIPTION:
XS GIS Cut Line= 5
      3003980.35     13845713.58      3003311.75     13844991.91
      3002866.01     13844790.27       3002356.6     13844493.12
      3001709.22     13844365.76
#Sta/Elev= 30
  3567.2   120.6  3628.1   119.9  3650.1   118.3  3920.3   120.7  4003.3   119.8
    4122   121.6  4419.6   120.5  4482.9   120.2    4551   117.5  4718.7   118.3
  4751.6   116.6  4925.8  116.88  4945.1  109.11  4978.7  101.64  4981.6   99.14
  4997.1   97.91  5014.4    99.9  5021.4  102.74  5055.3  108.39    5061  111.91
  5074.7  116.19  5077.8   118.5  5083.1   118.7  5154.6     118    5222   120.4
  5428.7   119.2  5696.8  121.36  5842.7   120.6  5944.9   122.5  6289.7   122.5
#Mann= 5 , 1 , 0
  3567.2      .2       0  4419.6      .1       0  4925.8    .045       0
  5074.7      .1       0  5696.8      .2       0
Bank Sta=4925.8,5074.7
XS Rating Curve= 0 ,0
Exp/Cntr=0.3,0.1

Type RM Length L Ch R = 1 ,18839.6 ,109.3,109.3,109.3
BEGIN DESCRIPTION:
Cross Section 18839.6-Interpolated
10-2012 Modified to reflect trail construction  LJA Eng.
END DESCRIPTION:
XS GIS Cut Line= 6
      3003942.01     13845359.94      3003346.93     13844531.08
      3003229.49     13844422.63      3003092.62     13844326.93
       3002902.3     13844262.01      3002607.22     13844179.39
#Sta/Elev= 30
  3815.3   118.4    3888   119.1  3923.4   118.2  4000.5   120.2  4368.1   118.5
  4419.6  117.58  4700.4   116.6  4741.1   117.7  4772.1     117  4835.7   117.6
  4890.9   116.4  4925.8  116.71  4945.1  108.94  4978.7  101.47  4981.6   98.97
  4982.4   99.77  4997.1   97.74  5014.4   99.73  5021.4  102.57 5050.46  107.41
 5060.32  107.47 5060.89  109.59    5061  111.74  5074.7  116.02  5083.3     117
  5118.2   117.6    5222   117.8  5294.6   119.2  5424.2   118.9    5670   122.1
#Mann= 6 ,-1 , 0
  3815.3      .2       0  4419.6      .1       0  4925.8    .045       0
 5050.46    .015       0 5060.89    .045       0  5074.7      .1       0
Bank Sta=4925.8,5074.7
XS Rating Curve= 0 ,0
Exp/Cntr=0.5,0.3

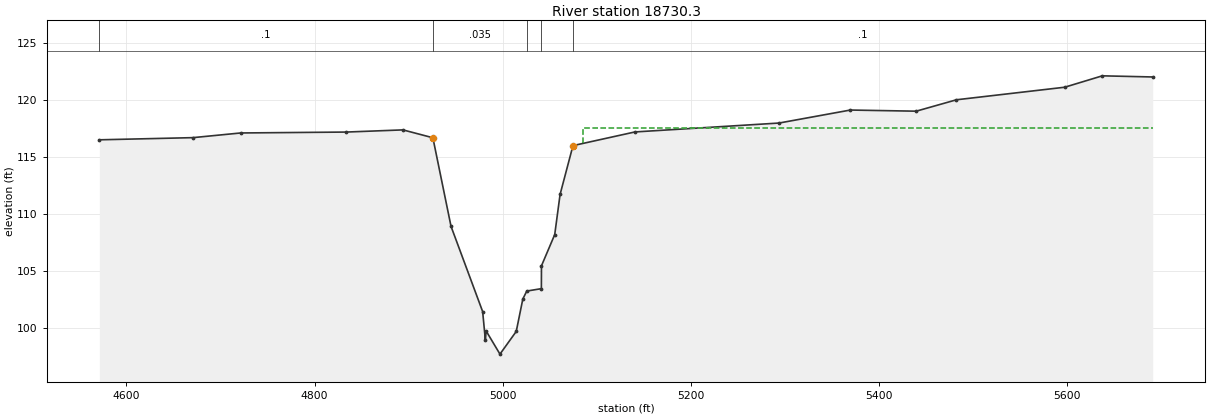
Type RM Length L Ch R = 1 ,18730.3 ,112,112,112
BEGIN DESCRIPTION:
Upstream Section of Bridge/Culvert/Weir
10-2012 Modified to reflect trail construction  LJA Eng.
END DESCRIPTION:
XS GIS Cut Line= 6
      3003704.37     13844327.58      3003531.93     13844337.44
      3003184.43     13844322.11      3002974.91     13844273.56
      3002752.62     13844202.02      3002614.91       13844143.
#Sta/Elev= 27
  4571.3  116.49  4670.8  116.68  4721.5  117.09  4833.8  117.17    4894  117.36
  4925.8  116.67  4945.1   108.9  4978.7  101.43  4981.6   98.93  4982.4   99.73
  4997.1    97.7  5014.4   99.69  5021.4  102.53 5025.61  103.23 5041.11  103.44
 5041.21  105.44  5055.3  108.18    5061   111.7  5074.7  115.98  5140.6  117.18
  5293.7  117.96  5369.5   119.1  5439.5     119  5482.3     120  5597.3   121.1
  5637.3   122.1  5690.9     122
#Mann= 5 ,-1 , 0
  4571.3      .1       0  4925.8    .035       0 5025.61    .015       0
 5041.21    .035       0  5074.7      .1       0
#XS Ineff= 2 , 0
       0    4922     116    5085       0   117.5
Permanent Ineff=
       F       F
Bank Sta=4925.8,5074.7
XS Rating Curve= 0 ,0
Exp/Cntr=0.5,0.3