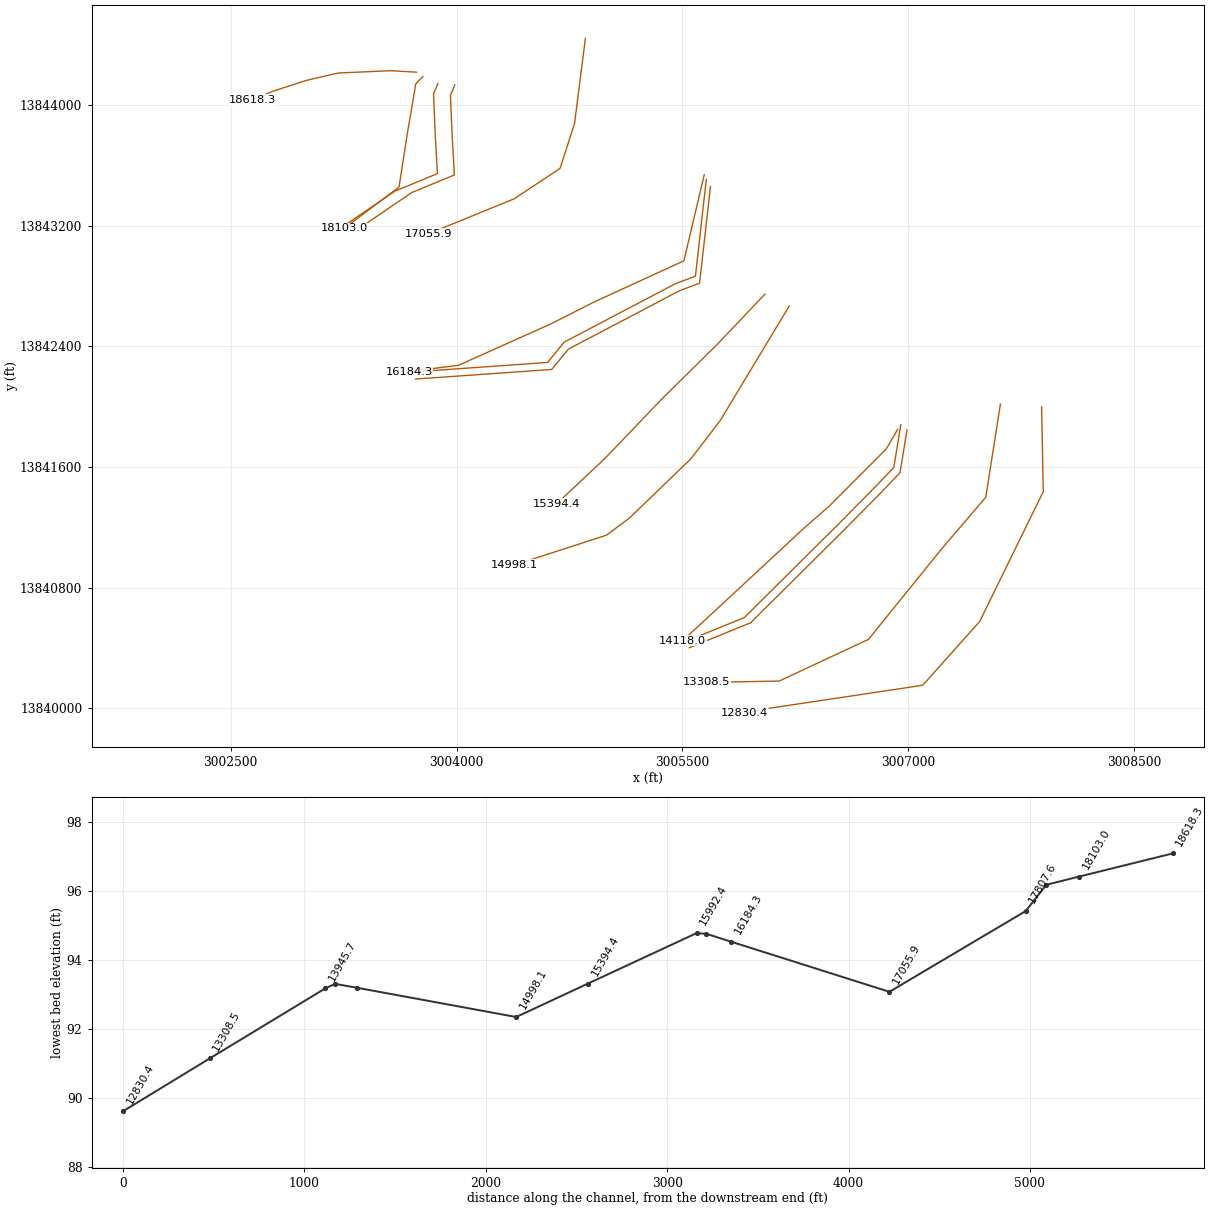
HEC-RAS study T101-00-00.PRJ: T101-00-00

--- T101-00-00.g01 (geometry) --- (continued)

Type RM Length L Ch R = 3 ,18674.3 ,,,
BEGIN DESCRIPTION:
KINGSLAND BLVD
Structure ID: T01-9
END DESCRIPTION:
Bridge Culvert--1,0,-1,-1, 0
Deck Dist Width WeirC Skew NumUp NumDn MinLoCord MaxHiCord MaxSubmerge Is_Ogee
10,92,2.6,0, 55, 55, , , 0.95, 0, 1,1,,
  4571.3  4576.8  4614.1  4670.8  4721.5  4727.3  4777.8    4780  4833.8  4841.9
    4894  4895.6 4921.09  4921.2 4921.31  4925.8  4931.7 4931.81  4931.9    4932
  4945.1  4978.7  4981.6  4982.4  4997.1  5014.4  5021.4  5055.3    5061  5074.7
  5091.4 5091.49  5091.6  5091.7 5108.89    5109 5109.11  5136.8  5140.6  5185.4
  5191.4  5236.7  5243.3  5288.8  5293.7  5307.6  5346.7  5369.5  5439.5  5482.3
  5541.1  5556.1  5597.3  5637.3  5690.9
  116.49  116.51  116.58  116.69   117.1   117.1  117.11  117.11  118.11  118.28
  118.37  118.37  117.51  121.31  121.31  121.16  120.96  120.96  120.96  120.96
  120.96  120.96  120.96  120.96  120.96  120.97  120.97  120.97  120.97  120.97
  120.97  120.97  120.97  120.97  121.34  121.34  117.54  118.14  118.14  118.18
  118.19  118.28  118.33  118.69  118.48  118.17  118.73  119.11  119.09  120.01
  120.57  120.72   121.1   122.1     122
  116.49   116.5  116.57  116.68  117.09  117.09   117.1   117.1  117.17   117.2
  117.36  117.33  116.77  116.77  116.77  116.67  114.29  114.25  115.56  115.56
  115.56  115.56  115.56  115.56  115.56  115.57  115.57  115.57  115.57  115.98
  116.28  116.29  116.29  116.29   116.6   116.6  116.61  117.11  117.18  117.41
  117.44  117.63  117.66  117.93  117.96  118.16  118.72   119.1     119     120
  120.56  120.71   121.1   122.1     122
  4571.3  4576.8  4614.1  4670.8  4721.5  4727.3  4777.8    4780  4833.8  4841.9
    4894  4895.6 4921.09  4921.2 4921.31  4925.8  4931.7 4931.81  4931.9    4932
  4945.1  4978.7  4981.6  4982.4  4997.1  5014.4  5021.4  5055.3    5061  5074.7
  5091.4 5091.49  5091.6  5091.7 5108.89    5109 5109.11  5136.8  5140.6  5185.4
  5191.4  5236.7  5243.3  5288.8  5293.7  5307.6  5346.7  5369.5  5439.5  5482.3
  5541.1  5556.1  5597.3  5637.3  5690.9
  116.49  116.51  116.58  116.69   117.1   117.1  117.11  117.11  118.11  118.28
  118.37  118.37  117.51  121.31  121.31  121.16  120.96  120.96  120.96  120.96
  120.96  120.96  120.96  120.96  120.96  120.97  120.97  120.97  120.97  120.97
  120.97  120.97  120.97  120.97  121.34  121.34  117.54  118.14  118.14  118.18
  118.19  118.28  118.33  118.69  118.48  118.17  118.73  119.11  119.09  120.01
  120.57  120.72   121.1   122.1     122
  115.88  115.89  115.96  116.07  116.48  116.48  116.49  116.49  116.56  116.59
  116.75  116.72  116.16  116.16  116.16  116.06  113.68  113.64  114.95  114.95
  114.95  114.95  114.95  114.95  114.95  114.96  114.96  114.96  114.96  115.37
  115.67  115.68  115.68  115.68  115.99  115.99     116   116.5  116.57   116.8
  116.83  117.02  117.05  117.32  117.35  117.55  118.11  118.49  118.39  119.39
  119.95   120.1  120.49  121.49  121.39
Pier Skew, UpSta & Num, DnSta & Num=  ,4982.4, 2 ,4982.4, 2 , 0 , 0 , 0 ,,
     1.4     1.4
   98.03  116.56
     1.4     1.4
   97.42  115.95
BR Coef= 1 , 1 , 0 ,1.25, 0 ,,,0.8,0,2,0,
WSPro=,,,, 1 ,,,, 0 ,,,, 0 ,,,,-1 ,-1 ,-1 , 0 , 0 , 0 , 0 , 0
BC Design=,, 0 ,, 0 ,,,,,,
BC HTab HWMax=122.1
BC Use User HTab Curves=0
BC User HTab FreeFlow(D)= 0

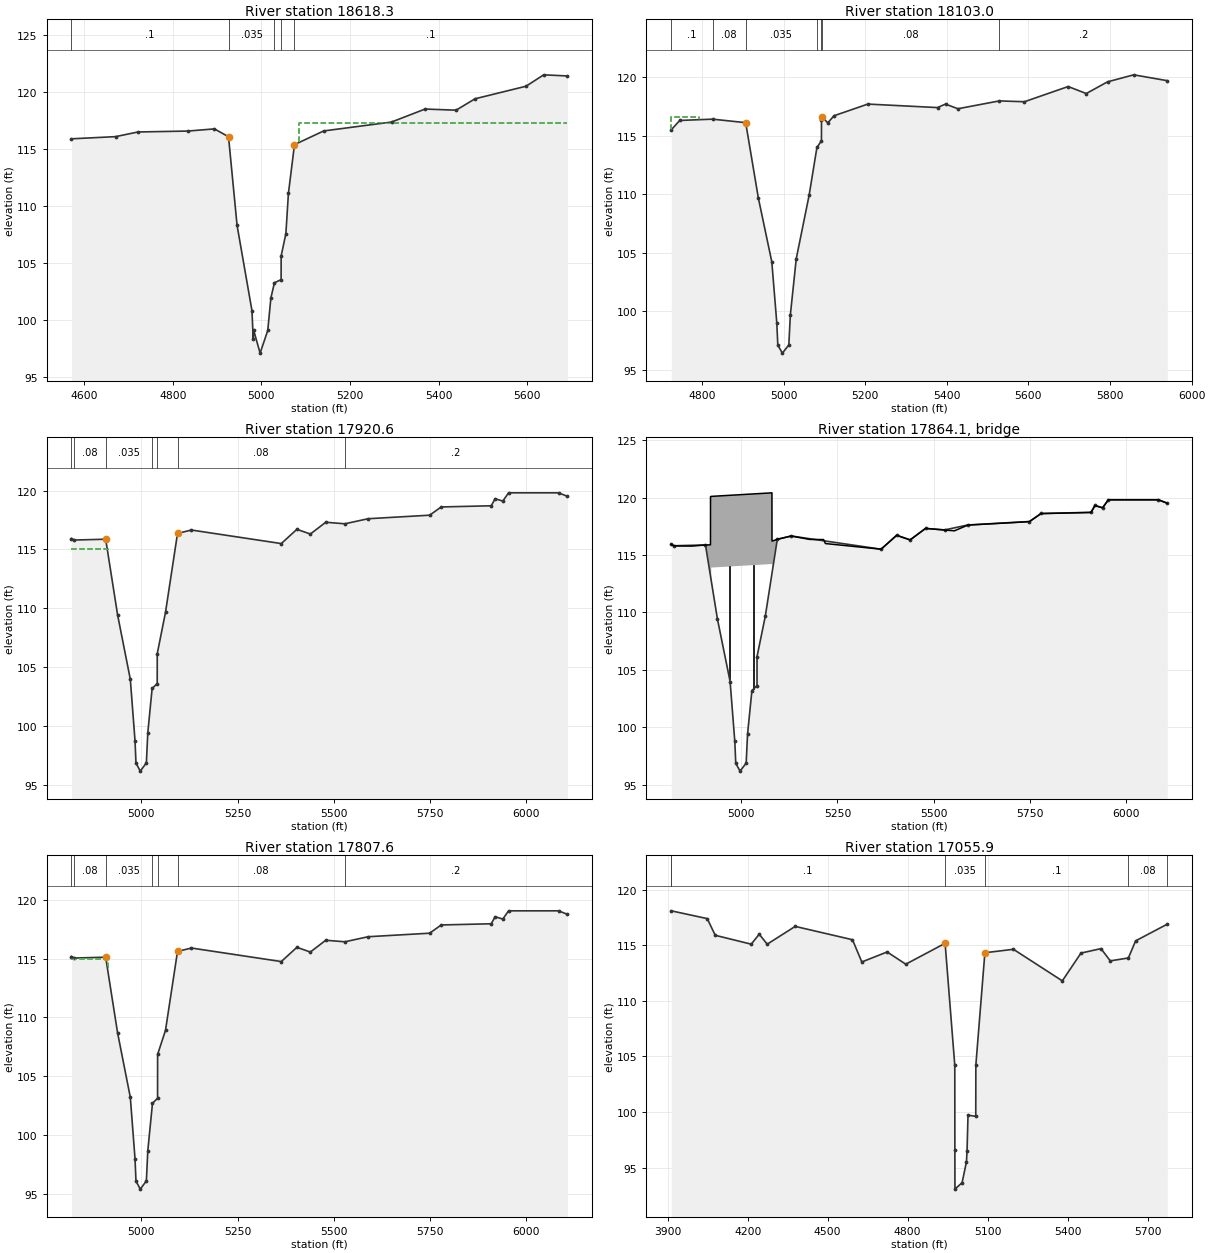
Type RM Length L Ch R = 1 ,18618.3 ,515.3,515.3,515.3
BEGIN DESCRIPTION:
Downstream Section of Bridge/Culvert/Weir
10-2012 Modified to reflect trail construction  LJA Eng.
END DESCRIPTION:
XS GIS Cut Line= 6
      3003733.92     13844219.55      3003561.47      13844229.4
      3003213.97     13844214.07      3003004.45     13844165.52
      3002782.16     13844093.98      3002644.46     13844034.97
#Sta/Elev= 27
  4571.3  115.87  4670.8  116.06  4721.5  116.47  4833.8  116.55    4894  116.74
  4925.8  116.05  4945.1  108.28  4978.7  100.81  4981.6   98.31  4982.4   99.11
  4997.1   97.08  5014.4   99.07  5021.4  101.91 5029.44  103.25 5044.51  103.52
 5044.61   105.6  5055.3  107.56    5061  111.08  5074.7  115.36  5140.6  116.56
  5293.7  117.34  5369.5  118.48  5439.5  118.38  5482.3  119.38  5597.3  120.48
  5637.3  121.48  5690.9  121.38
#Mann= 5 ,-1 , 0
  4571.3      .1       0  4925.8    .035       0 5029.44    .015       0
 5044.61    .035       0  5074.7      .1       0
#XS Ineff= 2 , 0
       0    4922   115.8    5085       0   117.3
Permanent Ineff=
       F       F
Bank Sta=4925.8,5074.7
XS Rating Curve= 0 ,0
Exp/Cntr=0.5,0.3

Type RM Length L Ch R = 1 ,18103.0 ,182.4,182.4,182.4
BEGIN DESCRIPTION:
Cross Section 18103.0-Interpolated
10-2012 Modified to reflect trail construction  LJA Eng.
END DESCRIPTION:
XS GIS Cut Line= 6
      3003776.37     13844190.97      3003728.68     13844141.01
      3003694.97     13843938.76      3003675.31     13843826.41
      3003617.73     13843457.02      3003255.37     13843184.55
#Sta/Elev= 30
  4724.8   115.5  4745.6   116.3  4826.1  116.41  4907.2  116.11  4938.2  109.67
  4971.2  104.21  4983.4      99  4985.9   97.09  4997.1   96.41  5012.9   97.11
  5016.6   99.67  5031.1  104.48  5062.6   109.9 5081.73  113.99 5092.85  114.56
 5092.95  116.33  5093.8   116.6  5108.4   116.1  5123.6   116.7  5206.5   117.7
  5377.2   117.4  5396.8   117.7  5427.2   117.3  5528.6  117.97  5590.2   117.9
  5697.4   119.2  5741.7   118.6  5793.8   119.6    5858   120.2  5940.2   119.7
#Mann= 7 ,-1 , 0
  4724.8      .1       0  4826.1     .08       0  4907.2    .035       0
 5081.73    .015       0 5092.95    .035       0  5093.8     .08       0
  5528.6      .2       0
#XS Ineff= 2 , 0
       0  4793.8   116.6               0
Permanent Ineff=
       F       F
Bank Sta=4907.2,5093.8
XS Rating Curve= 0 ,0
Exp/Cntr=0.5,0.3

Type RM Length L Ch R = 1 ,17920.6 ,113,113,113
BEGIN DESCRIPTION:
Upstream Section of Bridge/Culvert/Weir
10-2012 Modified to reflect trail construction  LJA Eng.
END DESCRIPTION:
XS GIS Cut Line= 6
      3003876.06     13844143.92      3003846.95     13844075.56
      3003859.06     13843793.68      3003872.89     13843546.39
      3003590.13     13843429.94      3003277.15     13843216.76
#Sta/Elev= 30
  4818.3  115.93  4826.1   115.8  4907.2  115.87  4938.2  109.43  4971.2  103.97
  4983.4   98.76  4985.9   96.85  4997.1   96.17  5012.9   96.87  5016.6   99.43
 5027.86  103.19 5041.08  103.61 5041.18  106.15  5062.6  109.66  5093.8  116.36
  5129.9  116.65  5363.4   115.5  5403.9  116.71  5438.9  116.31  5478.9  117.31
  5528.6  117.18  5588.9  117.61  5748.9  117.91  5778.9  118.61  5908.9  118.71
  5918.9  119.31  5938.9  119.11  5953.9  119.81  6083.9  119.81  6106.9  119.51
#Mann= 7 ,-1 , 0
  4818.3      .1       0  4826.1     .08       0  4907.2    .035       0
 5027.86    .015       0 5041.18    .035       0  5093.8     .08       0
  5528.6      .2       0
#XS Ineff= 2 , 0
       0    4912     115    5092       0     115
Permanent Ineff=
       F       F
Bank Sta=4907.2,5093.8
XS Rating Curve= 0 ,0
Exp/Cntr=0.5,0.3

Type RM Length L Ch R = 3 ,17864.1 ,,,
BEGIN DESCRIPTION:
WESTGREEN DRIVE
Structure ID: T01-7
END DESCRIPTION:
Bridge Culvert--1,0,-1,-1, 0
Deck Dist Width WeirC Skew NumUp NumDn MinLoCord MaxHiCord MaxSubmerge Is_Ogee
10,93,2.6,0, 31, 31, , , 0.95, 0, 1,1,,
  4818.3  4824.6  4872.4  4907.2 4920.19  4920.3 4922.11  4922.2  5079.9 5080.01
 5081.49  5081.6  5093.8  5129.8    5178    5214  5218.9  5363.4  5403.9  5438.9
  5478.9  5553.9  5588.9  5748.9  5778.9  5908.9  5918.9  5938.9  5953.9  6083.9
  6106.9
  115.92  115.79  115.77  115.87  115.88  120.08   120.1   120.1  120.41  116.21
  116.22  116.22  116.36  116.65  116.35  116.34  115.99   115.5  116.71  116.31
  117.31   117.1   117.6   117.9   118.6   118.7   119.3   119.1   119.8   119.8
   119.5
  115.92  115.79  115.76  115.86  113.16  113.14  112.76   113.9  114.21  114.21
  114.22  113.73  116.35  116.64  116.34  116.33  115.98  115.49   116.7   116.3
   117.3   117.1   117.6   117.9   118.6   118.7   119.3   119.1   119.8   119.8
   119.5
  4818.3  4824.6  4872.4  4907.2 4920.19  4920.3 4922.11  4922.2  5079.9 5080.01
 5081.49  5081.6  5093.8  5129.8    5178    5214  5218.9  5363.4  5403.9  5438.9
  5478.9  5553.9  5588.9  5748.9  5778.9  5908.9  5918.9  5938.9  5953.9  6083.9
  6106.9
  115.92  115.79  115.77  115.87  115.88  120.08   120.1   120.1  120.41  116.21
  116.22  116.22  116.36  116.65  116.35  116.34  115.99   115.5  116.71  116.31
  117.31   117.1   117.6   117.9   118.6   118.7   119.3   119.1   119.8   119.8
   119.5
   115.2  115.07  115.04  115.14  112.44  112.42  112.04  113.18  113.49  113.49
   113.5  113.01  115.63  115.92  115.62  115.61  115.26  114.77  115.98  115.58
  116.58  116.38  116.88  117.18  117.88  117.98  118.58  118.38  119.08  119.08
  118.78
Pier Skew, UpSta & Num, DnSta & Num=  ,4970, 2 ,4970, 2 , 0 , 0 , 0 ,,
       2       2
  102.96     115
       2       2
  102.24  114.28
Pier Skew, UpSta & Num, DnSta & Num=  ,5031.1, 2 ,5031.1, 2 , 0 , 0 , 0 ,,
       2       2
   102.9  115.12
       2       2
  102.18   114.4
BR Coef= 1 , 1 , 0 ,1.25, 0 ,,,0.8,0,2,0,
WSPro=,,,, 1 ,,,, 0 ,,,, 0 ,,,,-1 ,-1 ,-1 , 0 , 0 , 0 , 0 , 0
BC Design=,, 0 ,, 0 ,,,,,,
BC HTab HWMax=119.81
BC Use User HTab Curves=0
BC User HTab FreeFlow(D)= 0

Type RM Length L Ch R = 1 ,17807.6 ,751.7,751.7,751.7
BEGIN DESCRIPTION:
Downstream Section of Bridge/Culvert/Weir
10-2012 Modified to reflect trail construction  LJA Eng.
END DESCRIPTION:
XS GIS Cut Line= 6
      3003988.71     13844135.06      3003959.61      13844066.7
      3003971.72     13843784.82      3003985.55     13843537.53
      3003702.79     13843421.08       3003389.8      13843207.9
#Sta/Elev= 30
  4818.3  115.17  4826.1  115.04  4907.2  115.11  4938.2  108.67  4971.2  103.21
  4983.4      98  4985.9   96.09  4997.1   95.41  5012.9   96.11  5016.6   98.67
 5028.77   102.7 5041.99  103.13 5042.09  106.85  5062.6   108.9  5093.8   115.6
  5129.9  115.89  5363.4  114.74  5403.9  115.95  5438.9  115.55  5478.9  116.55
  5528.6  116.42  5588.9  116.85  5748.9  117.15  5778.9  117.85  5908.9  117.95
  5918.9  118.55  5938.9  118.35  5953.9  119.05  6083.9  119.05  6106.9  118.75
#Mann= 7 ,-1 , 0
  4818.3      .1       0  4826.1     .08       0  4907.2    .035       0
 5028.77    .015       0 5042.09    .035       0  5093.8     .08       0
  5528.6      .2       0
#XS Ineff= 2 , 0
       0    4912     115    5092       0     115
Permanent Ineff=
       F       F
Bank Sta=4907.2,5093.8
XS Rating Curve= 0 ,0
Exp/Cntr=0.5,0.3

Type RM Length L Ch R = 1 ,17055.9 ,881.5,871.6,855.1
BEGIN DESCRIPTION:
Cross Section 17055.9
END DESCRIPTION:
XS GIS Cut Line= 5
       3004856.1     13844444.12      3004783.94     13843878.84
      3004687.72     13843581.17      3004384.03     13843379.71
      3003815.75     13843148.19
#Sta/Elev= 30
  3913.2   118.1  4048.2   117.4  4078.2   115.9  4213.2   115.1  4243.2     116
  4273.2   115.1  4378.2   116.7  4593.1   115.5  4628.1   113.5  4723.1   114.4
  4793.1   113.3  4940.6  115.18  4976.9   104.2  4977.2   96.57  4977.5   93.07
  5004.3   93.65  5020.7   95.53  5022.9   96.52  5026.5   99.72  5055.6   99.62
  5055.9  104.22  5089.8  114.33  5196.9  114.64  5380.3   111.8  5450.3   114.3
  5525.3   114.7  5560.3   113.6  5628.2  113.86  5655.3   115.4    5774   116.9
#Mann= 6 , 1 , 0
  3913.2      .2       0  3913.2      .1       0  4940.6    .035       0
  5089.8      .1       0  5628.2     .08       0    5774      .2       0
#XS Ineff= 2 , 0
       0                  5196.9       0  114.64
Permanent Ineff=
       F       F
Bank Sta=4940.6,5089.8
XS Rating Curve= 0 ,0
Exp/Cntr=0.3,0.1

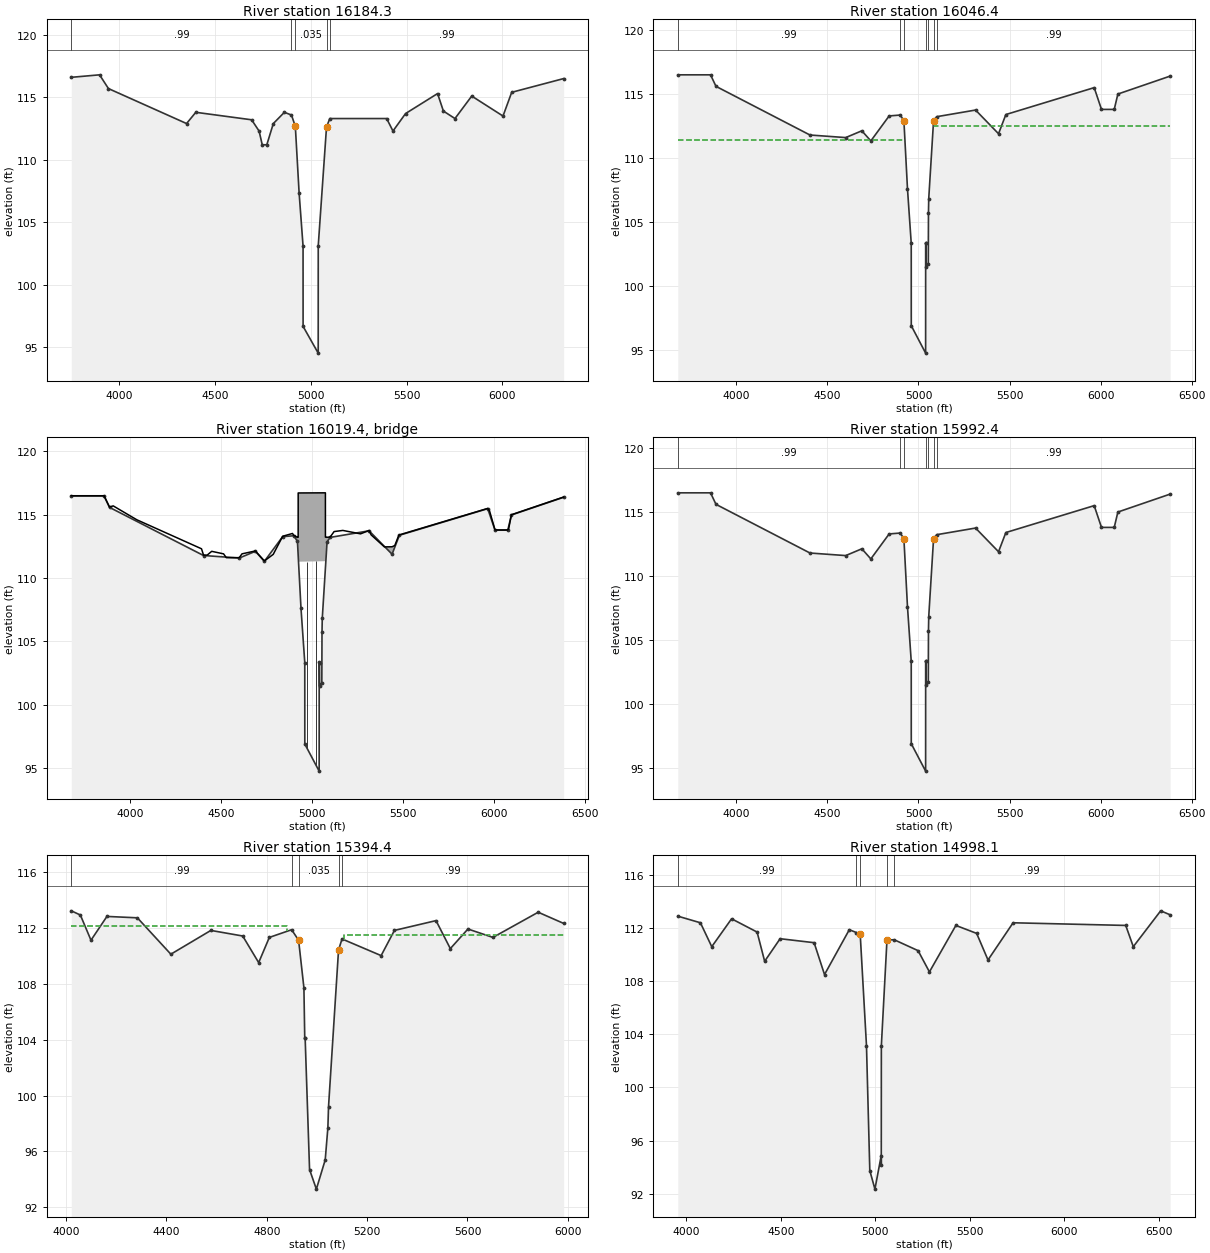
Type RM Length L Ch R = 1 ,16184.3 ,137.9,137.9,137.9
BEGIN DESCRIPTION:
Cross Section 16184.3-Interpolated
END DESCRIPTION:
XS GIS Cut Line= 6
      3005645.75     13843539.48      3005510.43     13842967.84
      3004913.93     13842694.44      3004623.97     13842548.08
      3004013.66     13842274.68      3003685.03     13842233.26
#Sta/Elev= 30
  3751.4   116.6  3898.9   116.8  3945.2   115.7  4352.7   112.9  4400.9   113.8
  4692.1   113.2    4731   112.3  4747.5   111.2  4771.3   111.2  4805.3   112.9
    4863   113.8    4900  113.58  4920.1  112.67  4939.7  107.37  4960.4  103.09
  4960.6   96.66  5039.4   94.52  5039.6  103.12  5082.8  112.63    5100   113.3
  5396.5   113.3  5429.4   112.3  5495.1   113.7    5662   115.3  5692.4   113.9
  5752.8   113.3  5840.3   115.1  6003.4   113.5  6048.7   115.4  6319.8   116.5
#Mann= 5 , 1 , 0
  3751.4     .99       0    4900      .1       0  4920.1    .035       0
  5082.8      .1       0    5100     .99       0
#XS Ineff= 2 , 0
       0    4863   113.8               0
Permanent Ineff=
       F       F
Bank Sta=4920.1,5082.8
XS Rating Curve= 0 ,0
Exp/Cntr=0.5,0.3

Type RM Length L Ch R = 1 ,16046.4 ,54,54,54
BEGIN DESCRIPTION:
Upstream Section of Bridge/Culvert/Weir
END DESCRIPTION:
XS GIS Cut Line= 6
      3005659.19     13843507.14      3005587.06     13842865.85
      3005455.69     13842816.59      3004716.01     13842428.71
      3004604.76     13842293.41      3003699.86     13842229.59
#Sta/Elev= 30
  3678.5  116.48  3858.5  116.48  3888.5  115.58  4404.5  111.78  4600.7  111.58
  4689.2  112.11  4738.6  111.32  4839.1  113.27    4900  113.34  4920.1   112.9
  4939.7   107.6  4960.4  103.32  4960.6   96.89  5039.4   94.75  5039.6  103.35
  5041.3  103.31    5042  101.49    5054  101.72    5055  105.72  5056.5  106.82
  5082.8  112.86    5100  113.21  5313.5  113.73  5439.7  111.88  5479.9  113.38
  5964.9  115.48  6004.9  113.78  6074.9  113.78  6094.9  114.98  6381.8  116.38
#Mann= 7 ,-1 , 0
  3678.5     .99       0    4900      .1       0  4920.1    .035       0
    5042    .015       0    5055    .035       0  5082.8      .1       0
    5100     .99       0
#XS Ineff= 2 , 0
       0  4925.7   111.4  5081.2       0   112.5
Permanent Ineff=
       F       F
Bank Sta=4920.1,5082.8
XS Rating Curve= 0 ,0
Exp/Cntr=0.5,0.3

Type RM Length L Ch R = 3 ,16019.4 ,,,
BEGIN DESCRIPTION:
PARK PINE ROAD
Structure ID: T01-5
END DESCRIPTION:
Bridge Culvert--1,0,-1,-1, 0
Deck Dist Width WeirC Skew NumUp NumDn MinLoCord MaxHiCord MaxSubmerge Is_Ogee
10,34,2.6,0, 46, 46, , , 0.95, 0, 1,1,,
  3678.5  3858.5  3888.5  3908.5  4038.5  4393.5  4404.5  4424.5  4449.5  4514.5
  4529.5  4600.7  4615.7  4689.2  4738.6  4787.2  4839.1    4893    4900  4920.1
 4924.09  4924.2 4926.11  5073.7 5073.81 5073.89    5074  5082.8    5100  5121.4
  5169.4  5266.6  5313.5  5324.7  5397.6  5439.7  5454.7  5474.7  5479.9  5964.9
  5974.9  6004.9  6074.9  6079.9  6094.9  6381.8
   116.5   116.5   115.6   115.7   114.6  112.31  111.81  111.81  112.11  111.91
  111.61  111.61  111.91  112.14  111.35  111.87   113.3  113.52  113.37  113.21
  113.22  116.72  116.72  116.73  113.23  113.23  113.23  113.22  113.24  113.67
  113.76  113.49  113.76  113.41  112.46  112.47  112.57  113.31  113.41   115.5
   115.3   113.8   113.8   113.9     115   116.4
   116.5   116.5   115.6   115.7   114.6   112.3   111.8   111.8   112.1   111.9
   111.6   111.6   111.9  112.13  111.34  111.86  113.29  113.51  113.36  112.92
  111.84  111.81  111.29  111.33  111.33  111.33  110.86  112.88  113.23  113.66
  113.75  113.48  113.75   113.4  112.45   111.9   112.2   113.3   113.4   115.5
   115.3   113.8   113.8   113.9     115   116.4
  3678.5  3858.5  3888.5  3908.5  4038.5  4393.5  4404.5  4424.5  4449.5  4514.5
  4529.5  4600.7  4615.7  4689.2  4738.6  4787.2  4839.1    4893    4900  4920.1
 4924.09  4924.2 4926.11  5073.7 5073.81 5073.89    5074  5082.8    5100  5121.4
  5169.4  5266.6  5313.5  5324.7  5397.6  5439.7  5454.7  5474.7  5479.9  5964.9
  5974.9  6004.9  6074.9  6079.9  6094.9  6381.8
  116.52  116.52  115.62  115.72  114.62  112.32  111.82  111.82  112.12  111.92
  111.62  111.62  111.92  112.15  111.36  111.88  113.31  113.53  113.38  113.21
  113.22  116.72  116.72  116.73  113.23  113.23  113.23  113.22  113.25  113.68
  113.77   113.5  113.77  113.42  112.47  112.47  112.57  113.32  113.42  115.52
  115.32  113.82  113.82  113.92  115.02  116.42
  116.52  116.52  115.62  115.72  114.62  112.32  111.82  111.82  112.12  111.92
  111.62  111.62  111.92  112.15  111.36  111.88  113.31  113.53  113.38  112.94
  111.86  111.83  111.31  111.35  111.35  111.35  110.88   112.9  113.25  113.68
  113.77   113.5  113.77  113.42  112.47  111.92  112.22  113.32  113.42  115.52
  115.32  113.82  113.82  113.92  115.02  116.42
Pier Skew, UpSta & Num, DnSta & Num=  ,4974.5, 2 ,4974.5, 2 , 0 , 0 , 0 ,,
     1.4     1.4
   95.85  112.32
     1.4     1.4
   95.87  112.34
Pier Skew, UpSta & Num, DnSta & Num=  ,5024, 2 ,5024, 2 , 0 , 0 , 0 ,,
     1.4     1.4
   94.09  112.33
     1.4     1.4
   94.11  112.35
Abutment Skew #Up #Dn= , 2 , 2
    4926  4958.7
  111.32   103.3
    4926  4958.7
  111.34  103.32
Abutment Skew #Up #Dn= , 2 , 2
  5056.5 5074.09
  106.84  111.33
  5056.5 5074.09
  106.84  111.35
BR Coef= 1 , 1 , 0 ,1.25, 0 ,,,0.8,0,2,0,
WSPro=,,,, 1 ,,,, 0 ,,,, 0 ,,,,-1 ,-1 ,-1 , 0 , 0 , 0 , 0 , 0
BC Design=,, 0 ,, 0 ,,,,,,
BC HTab HWMax=116.48
BC Use User HTab Curves=0
BC User HTab FreeFlow(D)= 0

Type RM Length L Ch R = 1 ,15992.4 ,598,598,598
BEGIN DESCRIPTION:
Downstream Section of Bridge/Culvert/Weir
END DESCRIPTION:
XS GIS Cut Line= 6
       3005686.8     13843460.73      3005614.66     13842819.45
      3005483.29     13842770.19      3004743.61     13842382.31
      3004632.36     13842247.01      3003727.47     13842183.18
#Sta/Elev= 30
  3678.5   116.5  3858.5   116.5  3888.5   115.6  4404.5   111.8  4600.7   111.6
  4689.2  112.13  4738.6  111.34  4839.1  113.29    4900  113.36  4920.1  112.92
  4939.7  107.62  4960.4  103.34  4960.6   96.91  5039.4   94.77  5039.6  103.37
  5041.3  103.33    5042  101.49    5054  101.72    5055  105.72  5056.5  106.84
  5082.8  112.88    5100  113.23  5313.5  113.75  5439.7   111.9  5479.9   113.4
  5964.9   115.5  6004.9   113.8  6074.9   113.8  6094.9     115  6381.8   116.4
#Mann= 7 ,-1 , 0
  3678.5     .99       0    4900      .1       0  4920.1    .035       0
    5042    .015       0    5055    .035       0  5082.8      .1       0
    5100     .99       0
#XS Ineff= 2 , 0
       0  4925.7   111.2  5081.2       0   112.3
Permanent Ineff=
       F       F
Bank Sta=4920.1,5082.8
XS Rating Curve= 0 ,0
Exp/Cntr=0.5,0.3

Type RM Length L Ch R = 1 ,15394.4 ,387.6,396.3,409.5
BEGIN DESCRIPTION:
Cross Section 15394.4-Interpolated
END DESCRIPTION:
XS GIS Cut Line= 5
      3006048.94     13842746.91      3005734.12     13842415.52
      3005361.31     13842048.23      3004982.97     13841653.33
      3004665.54     13841355.86
#Sta/Elev= 30
    4021   113.2  4057.2   112.9  4099.5   111.1  4163.1   112.8  4284.4   112.7
  4417.8   110.1  4577.3   111.8  4704.2   111.4  4767.8   109.5  4810.3   111.3
  4899.1  111.85  4926.9   111.1  4948.1   107.7  4951.4  104.12    4953  104.12
  4970.6   94.71  4997.7   93.31    5033    95.4  5043.6    97.7  5046.2    99.2
  5086.1   110.4    5100  111.19  5255.8     110  5308.8   111.8  5474.6   112.5
  5531.6   110.5  5601.8   111.9  5701.4   111.3  5881.8   113.1  5983.3   112.3
#Mann= 5 , 1 , 0
    4021     .99       0  4899.1      .1       0  4926.9    .035       0
  5086.1      .1       0    5100     .99       0
#XS Ineff= 2 , 0
       0    4879   112.1    5106       0   111.5
Permanent Ineff=
       F       F
Bank Sta=4926.9,5086.1
XS Rating Curve= 0 ,0
Exp/Cntr=0.3,0.1

Type RM Length L Ch R = 1 ,14998.1 ,892.1,880.1,857.8
BEGIN DESCRIPTION:
Cross Section 14998.1
END DESCRIPTION:
XS GIS Cut Line= 6
      3006210.66     13842668.61      3005753.63     13841910.89
      3005558.19     13841655.32      3005149.26     13841261.43
      3004995.92     13841147.17      3004387.04     13840950.22
#Sta/Elev= 30
  3954.1   112.9  4074.1   112.4  4134.1   110.6  4239.1   112.7  4374.1   111.7
  4414.1   109.5  4495.9   111.2  4675.9   110.9  4730.9   108.5  4862.2  111.88
    4900  111.66  4919.8  111.54    4953  103.15  4970.6   93.74  4997.7   92.34
  5031.1   94.87  5031.3   94.12  5031.7  103.13  5061.5  111.11    5100  111.12
  5226.2   110.3  5286.2   108.7  5426.2   112.2  5536.2   111.6  5596.2   109.6
    5729   112.4  6325.2   112.2  6365.2   110.6  6510.2   113.3  6560.2     113
#Mann= 5 , 1 , 0
  3954.1     .99       0    4900      .1       0  4919.8    .035       0
  5061.5      .1       0    5100     .99       0
#XS Ineff= 2 , 0
       0    4864  111.78    5078       0   111.1
Permanent Ineff=
       F       F
Bank Sta=4919.8,5061.5
XS Rating Curve= 0 ,0
Exp/Cntr=0.3,0.1

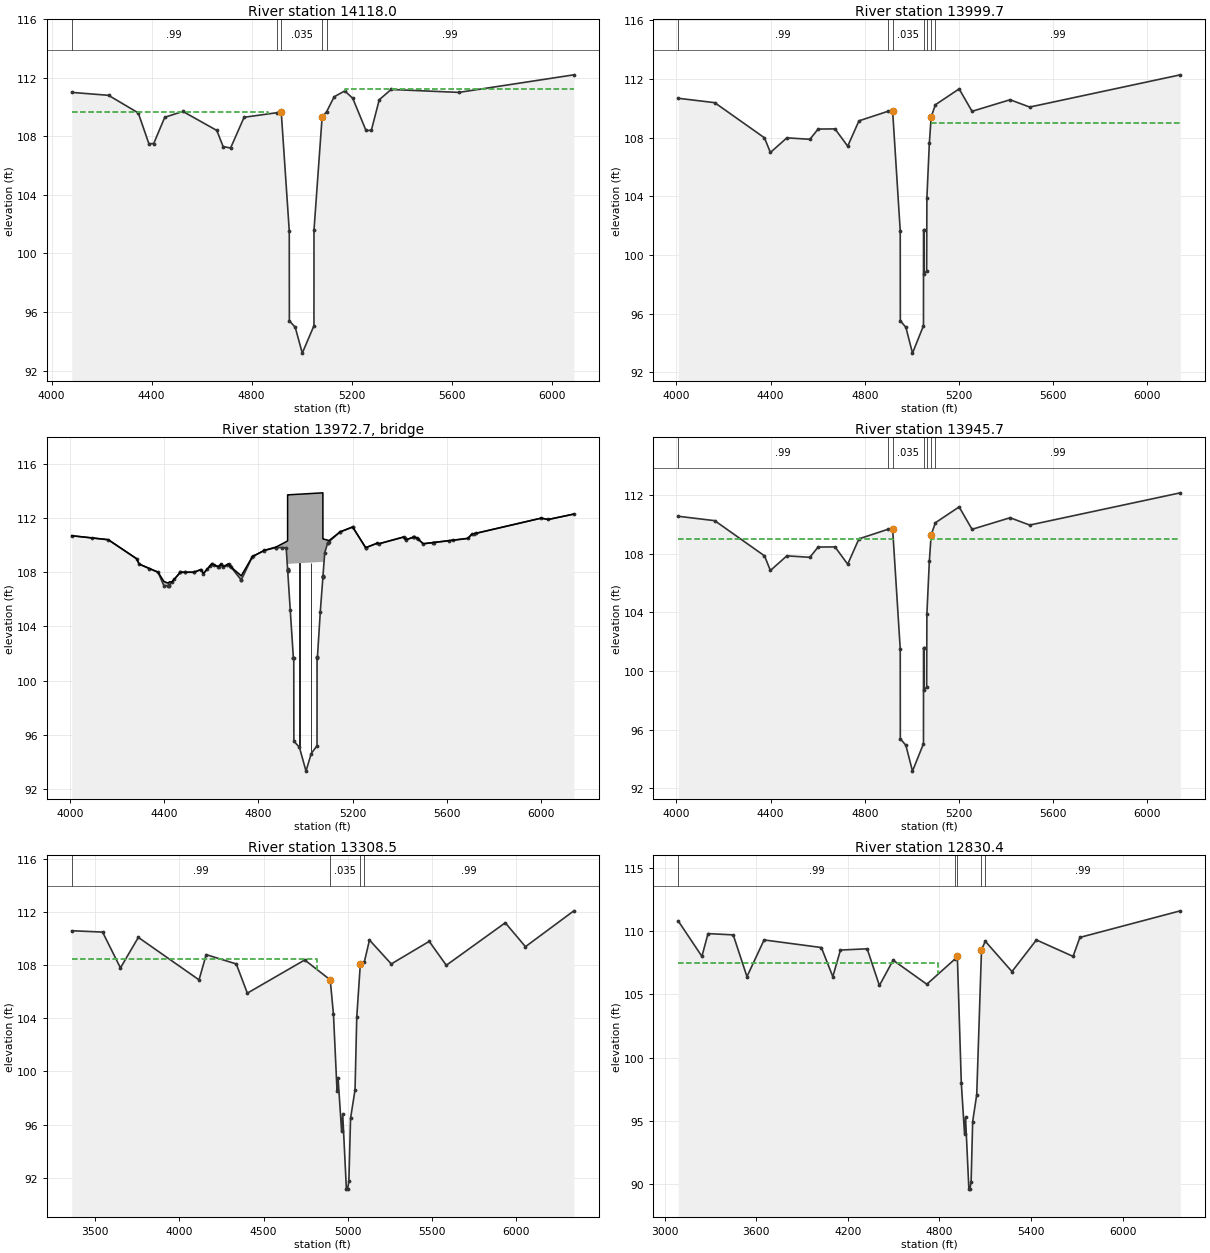
Type RM Length L Ch R = 1 ,14118.0 ,118.3,118.3,118.3
BEGIN DESCRIPTION:
Cross Section 14118.0-Interpolated
END DESCRIPTION:
XS GIS Cut Line= 6
      3006930.93     13841850.08      3006854.88      13841719.1
      3006474.63     13841338.85      3006309.85     13841195.19
      3005959.16     13840869.86      3005502.85     13840447.35
#Sta/Elev= 30
  4080.7     111  4227.8   110.8  4346.6   109.6    4389   107.5  4408.3   107.5
  4452.6   109.3    4525   109.7  4660.9   108.4    4686   107.3  4715.9   107.2
  4769.9   109.3    4900  109.61  4918.4  109.69  4950.6  101.53    4951    95.4
  4974.6   94.95  5002.6   93.19  5049.3   95.06  5049.5  101.59    5082  109.32
    5100  109.68  5130.1   110.7  5172.6   111.1  5204.4   110.6  5257.5   108.4
  5278.7   108.4  5310.6   110.5    5358   111.2    5629     111  6088.8   112.2
#Mann= 5 , 1 , 0
  4080.7     .99       0    4900      .1       0  4918.4    .035       0
    5082      .1       0    5100     .99       0
#XS Ineff= 2 , 0
       0    4867  109.65    5175       0   111.2
Permanent Ineff=
       F       F
Bank Sta=4918.4,5082
XS Rating Curve= 0 ,0
Exp/Cntr=0.5,0.3

Type RM Length L Ch R = 1 ,13999.7 ,54,54,54
BEGIN DESCRIPTION:
Upstream Section of Bridge/Culvert/Weir
END DESCRIPTION:
XS GIS Cut Line= 6
      3006951.28     13841879.98      3006905.18     13841596.65
      3006785.12     13841471.03      3006534.96     13841218.46
      3005912.47     13840600.79      3005506.03     13840435.53
#Sta/Elev= 30
  4007.9  110.69  4162.9  110.39  4374.2  107.99  4399.2  106.99  4469.2  107.99
  4566.9  107.89  4601.9  108.59  4673.7   108.6  4727.5  107.42  4775.3  109.15
    4900  109.81  4918.4   109.8  4950.6  101.64    4951   95.51  4974.6   95.06
  5002.6    93.3  5049.3   95.17  5049.5   101.7  5051.1  101.72  5051.2    98.7
  5062.8    98.9  5063.8   103.9 5074.16  107.61    5082  109.43    5100  110.25
  5200.7  111.33  5255.5   109.8  5417.1  110.59  5500.3  110.09  6139.9  112.29
#Mann= 7 ,-1 , 0
  4007.9     .99       0    4900      .1       0  4918.4    .035       0
  5051.2    .015       0  5063.8    .035       0    5082      .1       0
    5100     .99       0
#XS Ineff= 2 , 0
       0  4921.4     109  5080.1       0     109
Permanent Ineff=
       F       F
Bank Sta=4918.4,5082
XS Rating Curve= 0 ,0
Exp/Cntr=0.5,0.3

Type RM Length L Ch R = 3 ,13972.7 ,,,
BEGIN DESCRIPTION:
PRINCE CREEK DRIVE
Structure ID: T01-4
END DESCRIPTION:
Bridge Culvert--1,0,-1,-1, 0
Deck Dist Width WeirC Skew NumUp NumDn MinLoCord MaxHiCord MaxSubmerge Is_Ogee
10,34,2.6,0, 51, 51, , , 0.95, 0, 1,1,,
  4007.9  4162.9  4282.9  4294.2  4374.2  4399.2  4417.7  4422.7  4432.7  4469.2
  4526.9  4556.9  4566.9  4601.9  4631.9  4641.9  4651.9  4673.7  4683.7  4727.5
  4775.3  4825.5    4876  4918.4 4924.37 4924.48 4924.71  4924.8 5074.27 5074.38
 5074.49  5074.6    5082  5095.1    5100  5147.4  5200.6  5255.5  5257.5  5305.9
  5312.1  5417.1  5427.1  5462.1  5475.3  5500.3  5690.3  5706.2  6001.2  6031.2
  6139.9
   110.7  110.41  109.01  108.61  108.01  107.32   107.2   107.3  107.28  108.01
  108.01  108.21  107.91  108.61  108.41  108.61  108.41  108.62   108.4  107.74
  109.17  109.62  109.87  110.26  110.32  113.72  113.72  113.72  113.87  110.47
  110.47  110.47  110.43  110.37  110.34  110.99  111.35  109.84  109.83  110.16
  110.11  110.61  110.41  110.61  110.51  110.11  110.51  110.81     112   111.9
   112.3
   110.7   110.4     109   108.6     108     107     107  107.07  107.27     108
     108   108.2   107.9   108.6   108.4   108.6   108.4  108.61  108.39  107.43
  109.16  109.61  109.83  109.81  108.22  108.19  108.13  108.62  108.77  108.77
  108.77  107.72  109.44  110.19  110.26  110.98  111.34  109.81  109.82  110.15
   110.1   110.6   110.4   110.6   110.5   110.1   110.5   110.8     112   111.9
   112.3
  4007.9  4162.9  4282.9  4294.2  4374.2  4399.2  4417.7  4422.7  4432.7  4469.2
  4526.9  4556.9  4566.9  4601.9  4631.9  4641.9  4651.9  4673.7  4683.7  4727.5
  4775.3  4825.5    4876  4918.4 4924.37 4924.48 4924.71  4924.8 5074.27 5074.38
 5074.49  5074.6    5082  5095.1    5100  5147.4  5200.6  5255.5  5257.5  5305.9
  5312.1  5417.1  5427.1  5462.1  5475.3  5500.3  5690.3  5706.2  6001.2  6031.2
  6139.9
   110.7  110.41  109.01  108.61  108.01  107.32   107.2   107.3  107.28  108.01
  108.01  108.21  107.91  108.61  108.41  108.61  108.41  108.62   108.4  107.74
  109.17  109.62  109.87  110.26  110.32  113.72  113.72  113.72  113.87  110.47
  110.47  110.47  110.43  110.37  110.34  110.99  111.35  109.84  109.83  110.16
  110.11  110.61  110.41  110.61  110.51  110.11  110.51  110.81     112   111.9
   112.3
  110.59  110.29  108.89  108.49  107.89  106.89  106.89  106.96  107.16  107.89
  107.89  108.09  107.79  108.49  108.29  108.49  108.29   108.5  108.28  107.32
  109.05   109.5  109.72   109.7  108.11  108.08  108.02  108.51  108.66  108.66
  108.66  107.61  109.33  110.08  110.15  110.87  111.23   109.7  109.71  110.04
  109.99  110.49  110.29  110.49  110.39  109.99  110.39  110.69  111.89  111.79
  112.19
Pier Skew, UpSta & Num, DnSta & Num=  ,4974.6, 2 ,4974.6, 2 , 0 , 0 , 0 ,,
     1.4     1.4
   94.03  109.67
     1.4     1.4
   93.92  109.56
Pier Skew, UpSta & Num, DnSta & Num=  ,5024.7, 2 ,5024.7, 2 , 0 , 0 , 0 ,,
     1.4     1.4
   93.57  109.72
     1.4     1.4
   93.46  109.61
Abutment Skew #Up #Dn= , 2 , 2
  4924.6  4948.9
  108.62   101.7
  4924.6  4948.9
  108.51  101.59
Abutment Skew #Up #Dn= , 2 , 2
  5051.1 5074.69
  101.73  108.77
  5051.1 5074.69
  101.62  108.66
BR Coef= 1 , 1 , 0 ,1.25, 0 ,,,0.8,0,2,0,
WSPro=,,,, 1 ,,,, 0 ,,,, 0 ,,,,-1 ,-1 ,-1 , 0 , 0 , 0 , 0 , 0
BR U #Sta/Elev= 101
  4007.9   110.7  4092.7  110.54  4162.9   110.4  4282.9     109  4294.2   108.6
  4337.7  108.27  4374.2     108  4399.2     107  4417.7     107  4419.2     107
  4422.7  107.07  4432.7  107.27  4442.7  107.47  4468.7  107.99  4469.2     108
  4486.9     108  4488.7     108  4526.9     108  4528.7  108.01  4556.9   108.2
  4566.9   107.9  4583.7  108.24  4593.7  108.44  4601.9   108.6  4603.7  108.59
  4613.7  108.52  4628.7  108.42  4631.9   108.4  4633.7  108.44  4641.9   108.6
  4648.7  108.46  4651.9   108.4  4668.7  108.56  4673.7  108.61  4678.7   108.5
  4683.7  108.39  4727.4  107.43  4727.5  107.43  4775.3  109.16  4776.7  109.17
  4824.7   109.6  4825.5  109.61    4876  109.83  4876.8  109.83    4900  109.82
  4918.4  109.81 4924.37  108.22 4924.48  108.19 4924.59  108.16 4924.71  108.13
  4924.8  108.11  4935.6  105.23  4948.8   101.7  4948.9   101.7  4950.6  101.65
    4951   95.52  4974.6   95.07  5002.6   93.31  5024.7   94.61  5049.3   95.18
  5049.5  101.71    5051   101.7  5051.1  101.73  5063.2  105.08 5074.16  107.62
 5074.27  107.65 5074.38  107.67 5074.49   107.7  5074.6  107.72    5082  109.44
  5094.5  110.16  5095.1  110.19    5100  110.26  5147.4  110.98    5149  110.99
  5200.6  111.34  5200.7  111.34  5255.5  109.81  5257.5  109.82  5305.9  110.15
  5312.1   110.1  5417.1   110.6    5421  110.52  5427.1   110.4    5456  110.57
    5461  110.59  5462.1   110.6  5475.3   110.5    5476  110.49  5500.3   110.1
    5541  110.19    5546   110.2    5611  110.33    5626  110.36  5690.3   110.5
  5706.2   110.8    5716  110.84  5725.7  110.88  6001.2     112  6031.2   111.9
  6139.9   112.3
BR U #Mann= 5
  4007.9     .99    4900      .1  4918.4    .035    5082      .1    5100     .99
BR U Banks=4918.4,5082
BR D #Sta/Elev= 101
  4007.9  110.59  4092.7  110.43  4162.9  110.29  4282.9  108.89  4294.2  108.49
  4337.7  108.16  4374.2  107.89  4399.2  106.89  4417.7  106.89  4419.2  106.89
  4422.7  106.96  4432.7  107.16  4442.7  107.36  4468.7  107.88  4469.2  107.89
  4486.9  107.89  4488.7  107.89  4526.9  107.89  4528.7   107.9  4556.9  108.09
  4566.9  107.79  4583.7  108.13  4593.7  108.33  4601.9  108.49  4603.7  108.48
  4613.7  108.41  4628.7  108.31  4631.9  108.29  4633.7  108.33  4641.9  108.49
  4648.7  108.35  4651.9  108.29  4668.7  108.45  4673.7   108.5  4678.7  108.39
  4683.7  108.28  4727.4  107.32  4727.5  107.32  4775.3  109.05  4776.7  109.06
  4824.7  109.49  4825.5   109.5    4876  109.72  4876.8  109.72    4900  109.71
  4918.4   109.7 4924.37  108.11 4924.48  108.08 4924.59  108.05 4924.71  108.02
  4924.8     108  4935.6  105.12  4948.8  101.59  4948.9  101.59  4950.6  101.54
    4951   95.41  4974.6   94.96  5002.6    93.2  5024.7    94.5  5049.3   95.07
  5049.5   101.6    5051  101.59  5051.1  101.62  5063.2  104.97 5074.16  107.51
 5074.27  107.54 5074.38  107.56 5074.49  107.59  5074.6  107.61    5082  109.33
  5094.5  110.05  5095.1  110.08    5100  110.15  5147.4  110.87    5149  110.88
  5200.6  111.23  5200.7  111.23  5255.5   109.7  5257.5  109.71  5305.9  110.04
  5312.1  109.99  5417.1  110.49    5421  110.41  5427.1  110.29    5456  110.46
    5461  110.48  5462.1  110.49  5475.3  110.39    5476  110.38  5500.3  109.99
    5541  110.08    5546  110.09    5611  110.22    5626  110.25  5690.3  110.39
  5706.2  110.69    5716  110.73  5725.7  110.77  6001.2  111.89  6031.2  111.79
  6139.9  112.19
BR D #Mann= 5
  4007.9     .99    4900      .1  4918.4    .035    5082      .1    5100     .99
BR D Banks=4918.4,5082
BC Design=,, 0 ,, 0 ,,,,,,
BC HTab HWMax=112.29
BC Use User HTab Curves=0
BC User HTab FreeFlow(D)= 0

Type RM Length L Ch R = 1 ,13945.7 ,637.2,637.2,637.2
BEGIN DESCRIPTION:
Downstream Section of Bridge/Culvert/Weir
END DESCRIPTION:
XS GIS Cut Line= 6
      3006992.45     13841845.03      3006946.34     13841561.71
      3006826.28     13841436.09      3006576.12     13841183.52
      3005953.63     13840565.85      3005547.19     13840400.58
#Sta/Elev= 30
  4007.9  110.56  4162.9  110.26  4374.2  107.86  4399.2  106.86  4469.2  107.86
  4566.9  107.76  4601.9  108.46  4673.7  108.47  4727.5  107.29  4775.3  109.02
    4900  109.68  4918.4  109.67  4950.6  101.51    4951   95.38  4974.6   94.93
  5002.6   93.17  5049.3   95.04  5049.5  101.57  5051.1  101.59  5051.2    98.7
  5062.8    98.9  5063.8   103.9 5074.16  107.48    5082   109.3    5100  110.12
  5200.7   111.2  5255.5  109.67  5417.1  110.46  5500.3  109.96  6139.9  112.16
#Mann= 7 ,-1 , 0
  4007.9     .99       0    4900      .1       0  4918.4    .035       0
  5051.2    .015       0  5063.8    .035       0    5082      .1       0
    5100     .99       0
#XS Ineff= 2 , 0
       0  4921.4     109  5080.1       0     109
Permanent Ineff=
       F       F
Bank Sta=4918.4,5082
XS Rating Curve= 0 ,0
Exp/Cntr=0.5,0.3

Type RM Length L Ch R = 1 ,13308.5 ,482,478.1,474.5
BEGIN DESCRIPTION:
Cross Section 13308.5-Interpolated
END DESCRIPTION:
XS GIS Cut Line= 6
      3007613.29     13842016.97      3007516.06     13841398.93
      3007222.47     13841055.77      3006736.58      13840455.8
      3006142.96     13840179.06       3005661.3     13840170.61
#Sta/Elev= 30
  3359.6   110.6  3542.9   110.5  3649.2   107.8  3755.5   110.1  4116.5   106.9
  4159.1   108.8    4338   108.1  4403.8   105.9  4745.2   108.4  4896.8   106.9
  4916.1   104.3  4937.4    98.5  4943.3   99.53  4964.3   95.53    4971    96.8
  4992.8   91.17  4999.9   91.14  5007.6   91.73  5017.7   96.48  5044.3   98.61
  5054.6   104.1  5075.9   108.1    5100  108.27  5130.2   109.9  5259.8   108.1
  5485.5   109.8  5587.1     108  5937.9   111.2  6057.9   109.4  6345.7   112.1
#Mann= 4 , 1 , 0
  3359.6     .99       0  4896.8    .035       0  5075.9      .1       0
    5100     .99       0
#XS Ineff= 2 , 0
       0    4821   108.5               0
Permanent Ineff=
       F       F
Bank Sta=4896.8,5075.9
XS Rating Curve= 0 ,0
Exp/Cntr=0.3,0.1

Type RM Length L Ch R = 1 ,12830.4 ,454.2,455.5,435.2
BEGIN DESCRIPTION:
Cross Section 12830.4
END DESCRIPTION:
XS GIS Cut Line= 6
      3007887.04     13841998.56      3007898.17     13841436.54
      3007475.27     13840574.04      3007096.88     13840151.14
      3006056.32     13839995.34      3005914.42     13839964.73
#Sta/Elev= 30
  3089.8   110.8  3244.8     108  3284.8   109.8  3449.8   109.7  3539.8   106.4
  3651.9   109.3  4026.9   108.7  4101.9   106.4  4151.9   108.5  4326.9   108.6
  4406.9   105.7  4496.9   107.7  4717.5   105.8    4900  107.77  4917.4  108.01
  4943.3      98  4964.3      94    4971   95.27  4992.8   89.64  4999.9   89.61
  5007.6    90.2  5017.7   94.95  5044.3   97.08  5075.5   108.5    5100   109.2
    5275   106.8    5435   109.3    5675     108    5720   109.5  6377.3   111.6
#Mann= 5 , 1 , 0
  3089.8     .99       0    4900      .1       0  4917.4    .035       0
  5075.5      .1       0    5100     .99       0
#XS Ineff= 2 , 0
       0    4791   107.5               0
Permanent Ineff=
       F       F
Bank Sta=4917.4,5075.5
XS Rating Curve= 0 ,0
Exp/Cntr=0.3,0.1