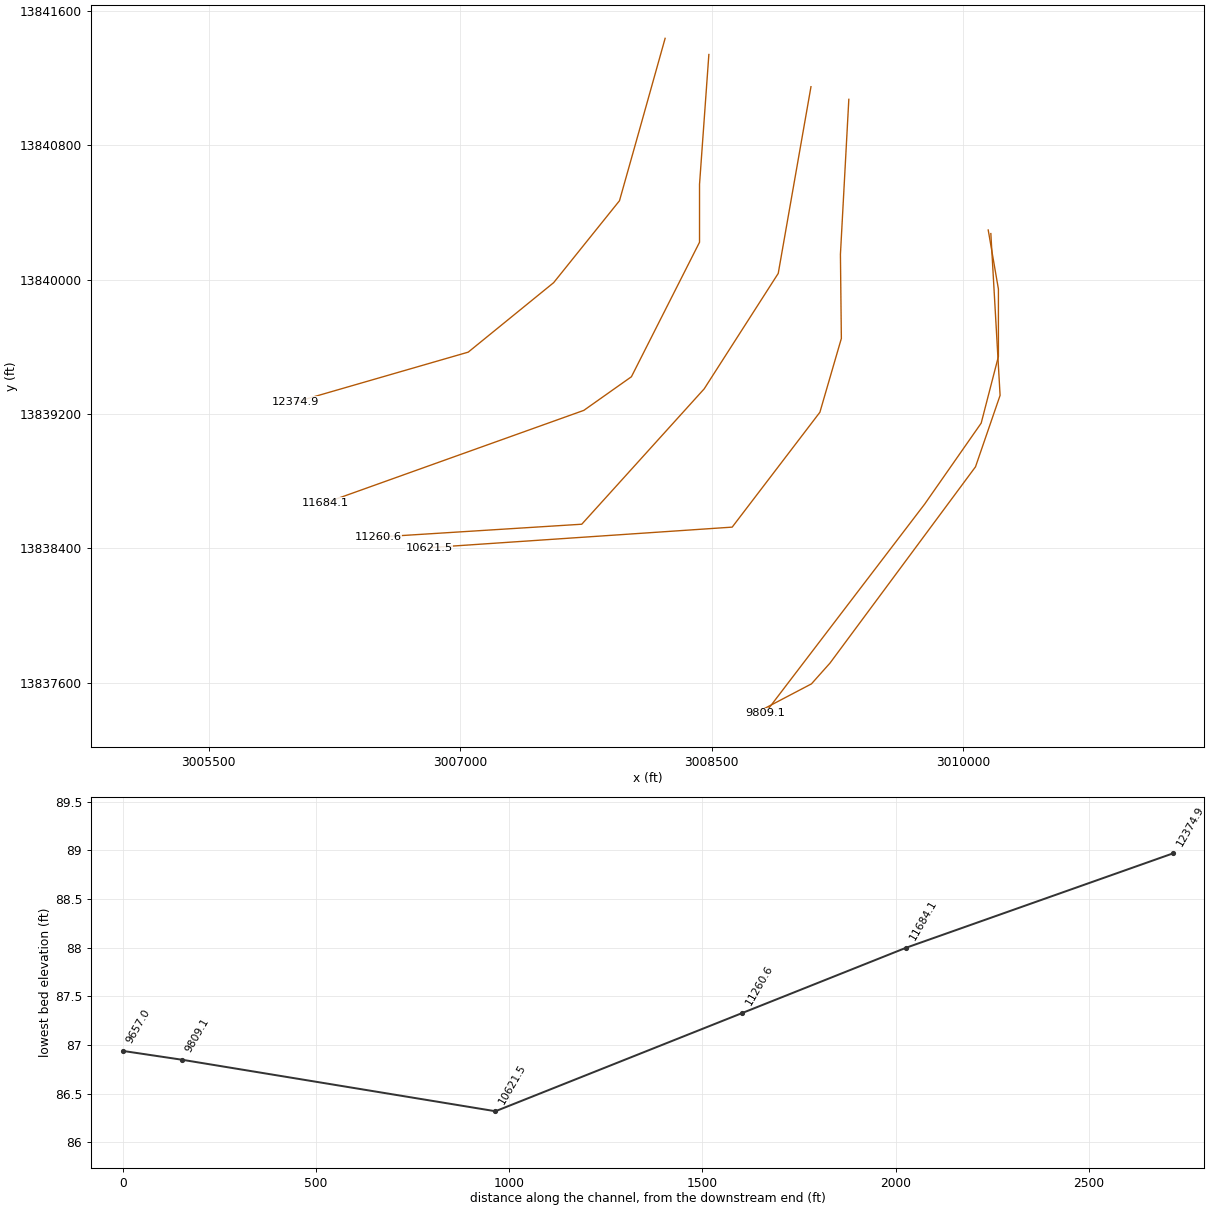
HEC-RAS study T101-00-00.PRJ: T101-00-00

--- T101-00-00.g01 (geometry) --- (continued)

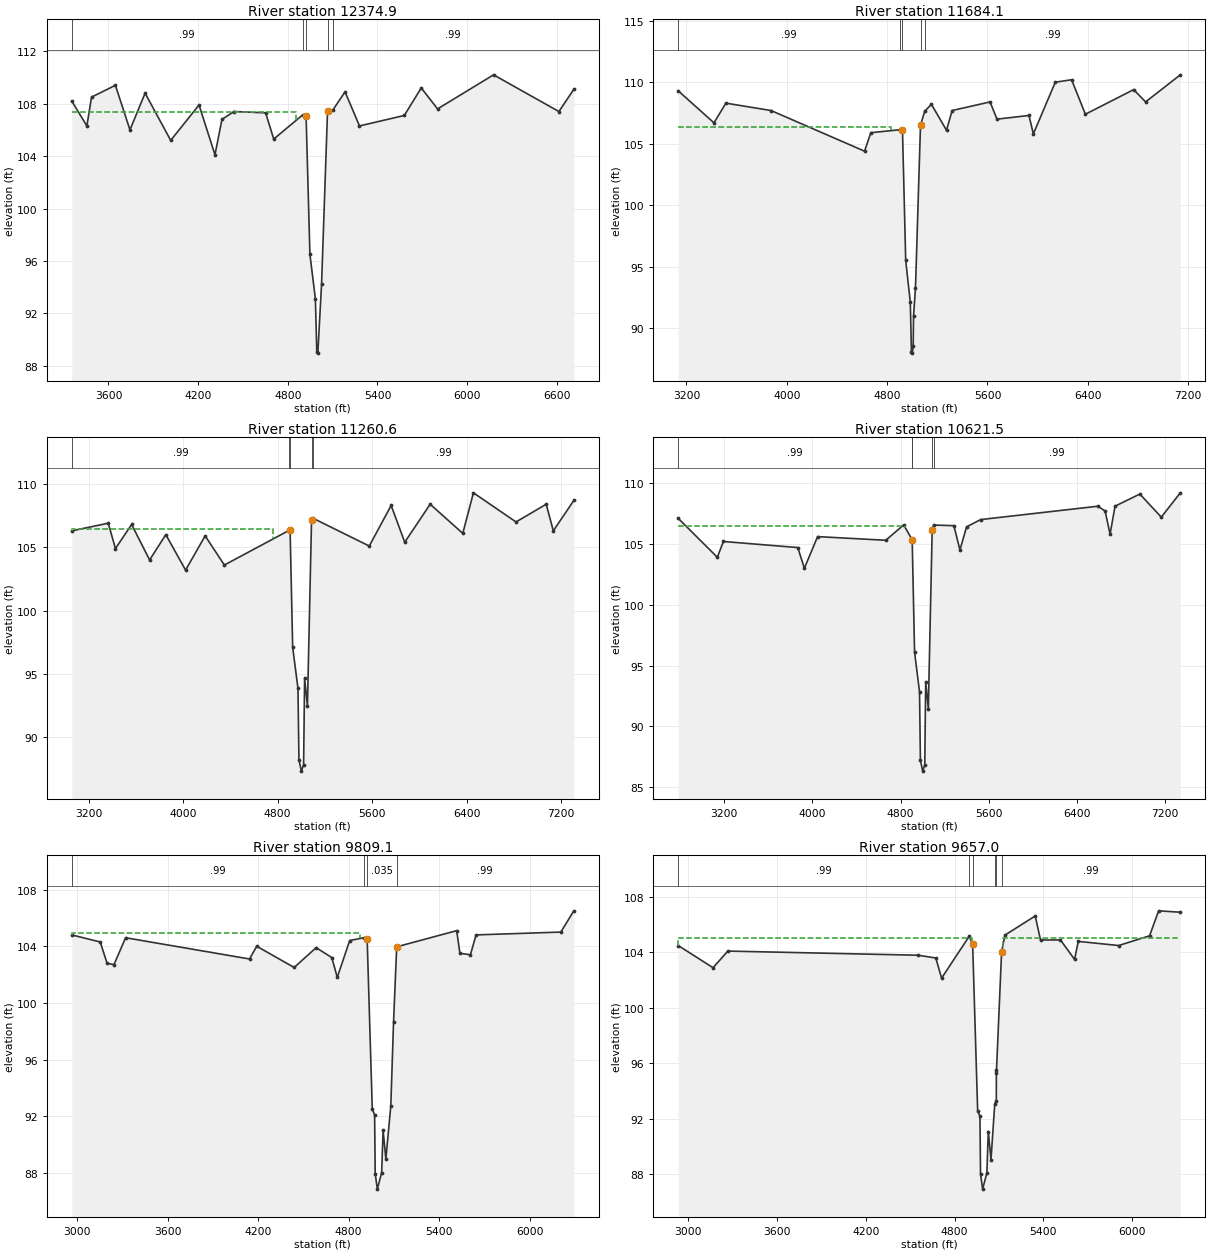
Type RM Length L Ch R = 1 ,12374.9 ,668.5,690.8,739.7
BEGIN DESCRIPTION:
Cross Section 12374.9-Interpolated
END DESCRIPTION:
XS GIS Cut Line= 6
      3008221.63      13841438.3      3008066.26     13840884.78
      3007949.52     13840470.89      3007556.84      13839982.7
      3007047.43      13839568.8        3006018.     13839271.65
#Sta/Elev= 30
  3354.5   108.2  3455.6   106.3  3486.8   108.5  3646.5   109.4  3743.8     106
  3845.1   108.8  4016.5   105.2  4205.9   107.9  4312.7   104.1  4359.4   106.8
  4440.1   107.4  4651.4   107.3  4705.9   105.3    4900  107.15  4922.3  107.06
  4947.9    96.5  4984.5   93.11  4993.8   89.07  5000.9   88.97  5025.9   94.25
  5065.9  107.47    5100  107.49  5182.9   108.9  5279.6   106.3  5579.3   107.1
  5692.8   109.2    5802   107.6  6176.5   110.2  6613.9   107.4  6713.8   109.1
#Mann= 5 , 1 , 0
  3354.5     .99       0    4900      .1       0  4922.3    .035       0
  5065.9      .1       0    5100     .99       0
#XS Ineff= 2 , 0
       0    4856  107.36               0
Permanent Ineff=
       F       F
Bank Sta=4922.3,5065.9
XS Rating Curve= 0 ,0
Exp/Cntr=0.3,0.1

Type RM Length L Ch R = 1 ,11684.1 ,431.8,423.5,377.9
BEGIN DESCRIPTION:
Cross Section 11684.1
END DESCRIPTION:
XS GIS Cut Line= 6
      3008482.44     13841341.95       3008426.8     13840568.48
       3008426.8     13840223.48      3008020.59     13839422.19
       3007736.8     13839221.87      3006195.43     13838670.99
#Sta/Elev= 30
  3134.3   109.3  3419.3   106.7  3514.3   108.3  3874.3   107.7  4619.8   104.4
  4669.8   105.9    4900  106.14  4922.3  106.09  4947.9   95.53  4984.5   92.14
  4993.8    88.1  5000.9      88  5007.7   88.58  5010.4   91.02  5025.9   93.28
  5065.9   106.5    5100  107.66  5153.2   108.2  5273.2   106.1  5318.2   107.7
  5620.6   108.4  5675.6     107  5930.6   107.3  5965.6   105.8  6140.6     110
  6270.6   110.2  6380.6   107.4  6765.6   109.4  6860.6   108.4  7137.4   110.6
#Mann= 5 , 1 , 0
  3134.3     .99       0    4900      .1       0  4922.3    .035       0
  5065.9      .1       0    5100     .99       0
#XS Ineff= 2 , 0
       0    4830  106.37               0
Permanent Ineff=
       F       F
Bank Sta=4922.3,5065.9
XS Rating Curve= 0 ,0
Exp/Cntr=0.3,0.1

Type RM Length L Ch R = 1 ,11260.6 ,632.7,639.1,648.5
BEGIN DESCRIPTION:
Cross Section 11260.6-Interpolated
END DESCRIPTION:
XS GIS Cut Line= 5
      3009091.45      13841150.1      3008896.17     13840037.89
      3008454.68     13839350.18      3007724.53     13838543.61
      3006510.43      13838467.2
#Sta/Elev= 30
    3057   106.3  3365.8   106.9  3426.8   104.9  3563.8   106.8  3716.1     104
  3853.2     106  4020.7   103.2  4186.2   105.9    4349   103.6    4900  106.35
  4905.6  106.35  4927.3   97.11  4972.2   93.86  4980.3   88.23    5001   87.33
  5019.9   87.83  5028.3   94.67  5052.2   92.46  5087.1  107.13    5100  107.29
  5575.7   105.1    5761   108.3  5876.2   105.4  6091.4   108.4  6367.5   106.1
  6457.7   109.3  6818.4     107  7073.9   108.4    7134   106.3  7307.9   108.7
#Mann= 5 , 1 , 0
    3057     .99       0    4900      .1       0  4905.6    .035       0
  5087.1      .1       0    5100     .99       0
#XS Ineff= 2 , 0
       0    4758  106.45               0
Permanent Ineff=
       F       F
Bank Sta=4905.6,5087.1
XS Rating Curve= 0 ,0
Exp/Cntr=0.3,0.1

Type RM Length L Ch R = 1 ,10621.5 ,815.2,812.4,807.7
BEGIN DESCRIPTION:
Cross Section 10621.5
END DESCRIPTION:
XS GIS Cut Line= 6
      3009317.12     13841074.85      3009267.03     13840151.14
       3009272.6     13839650.34      3009144.62     13839210.74
      3008621.55     13838526.31      3006813.09     13838403.89
#Sta/Elev= 30
  2781.9   107.1  3136.9   103.9  3191.9   105.2    3867   104.7    3927     103
    4047   105.6  4665.6   105.3  4828.7  106.56    4900  105.43  4905.6  105.34
  4927.3    96.1  4972.2   92.85  4980.3   87.22    5001   86.32  5019.9   86.82
  5028.3   93.66  5052.2   91.45  5087.1  106.12    5100  106.55  5284.2   106.5
  5339.2   104.5  5399.2   106.4  5527.1     107  6592.1   108.1  6657.1   107.7
  6702.1   105.8  6747.1   108.1  6972.1   109.1  7167.1   107.2  7339.7   109.2
#Mann= 5 , 1 , 0
  2781.9     .99       0    4900      .1       0  4905.6    .035       0
  5087.1      .1       0    5100     .99       0
#XS Ineff= 2 , 0
       0    4842   106.5               0
Permanent Ineff=
       F       F
Bank Sta=4905.6,5087.1
XS Rating Curve= 0 ,0
Exp/Cntr=0.3,0.1

Type RM Length L Ch R = 1 ,9809.1  ,152.1,152.1,152.1
BEGIN DESCRIPTION:
Cross Section 9809.1-Interpolated
END DESCRIPTION:
XS GIS Cut Line= 6
      3010148.34     13840296.52      3010209.18     13839944.99
      3010209.18     13839542.76       3010106.5     13839145.87
      3009769.77     13838663.94      3008816.59      13837416.7
#Sta/Elev= 30
  2964.8   104.8  3153.2   104.3  3198.8   102.8  3244.5   102.7  3321.6   104.6
  4142.7   103.1  4190.5     104  4438.7   102.5  4584.4   103.9  4688.1   103.2
  4724.4   101.8  4806.5   104.4    4900   104.6  4922.5  104.49  4956.3   92.51
  4971.8    92.1  4975.8   87.95  4989.9   86.85  5018.6   88.02  5028.1      91
  5046.4   88.97  5079.2   92.74  5097.3   98.64  5118.2  103.96  5515.7   105.1
  5537.2   103.5  5606.8   103.4  5644.2   104.8  6205.8     105  6292.2   106.5
#Mann= 4 , 1 , 0
  2964.8     .99       0    4900      .1       0  4922.5    .035       0
  5118.2     .99       0
#XS Ineff= 2 , 0
       0    4878   104.9               0
Permanent Ineff=
       F       F
Bank Sta=4922.5,5118.2
XS Rating Curve= 0 ,0
Exp/Cntr=0.5,0.3

Type RM Length L Ch R = 1 ,9657.0  ,113,113,113
BEGIN DESCRIPTION:
Upstream Section of Bridge/Culvert/Weir
PATH CUT IN RIGHT BANK
END DESCRIPTION:
XS GIS Cut Line= 6
      3010164.05     13840275.09      3010219.22     13839311.19
      3010072.56     13838885.61       3009204.9      13837716.4
      3009094.13     13837592.36      3008791.52     13837433.84
#Sta/Elev= 30
  2934.2  104.49  3169.2  102.89  3269.2  104.09    4556  103.79  4673.9  103.59
  4712.8  102.14    4900  105.17  4922.5  104.58  4956.3    92.6  4971.8   92.19
  4975.8   88.04  4989.9   86.94  5018.6   88.11  5028.1   91.09  5046.4   89.06
    5072    93.1  5082.5    93.3  5082.6    95.3  5083.6    95.5    5118  104.02
  5140.6  105.24  5345.2  106.62  5380.8  104.89  5515.8  104.89  5610.8  103.49
  5635.8  104.79  5908.5  104.49  6117.3  105.19  6178.6  106.99    6325  106.89
#Mann= 6 ,-1 , 0
  2934.2     .99       0    4900      .1       0  4922.5    .035       0
    5072    .015       0  5083.6    .035       0    5118     .99       0
#XS Ineff= 2 , 0
       0    4920     105    5125       0     105
Permanent Ineff=
       F       F
Bank Sta=4922.5,5118
XS Rating Curve= 0 ,0
Exp/Cntr=0.5,0.3