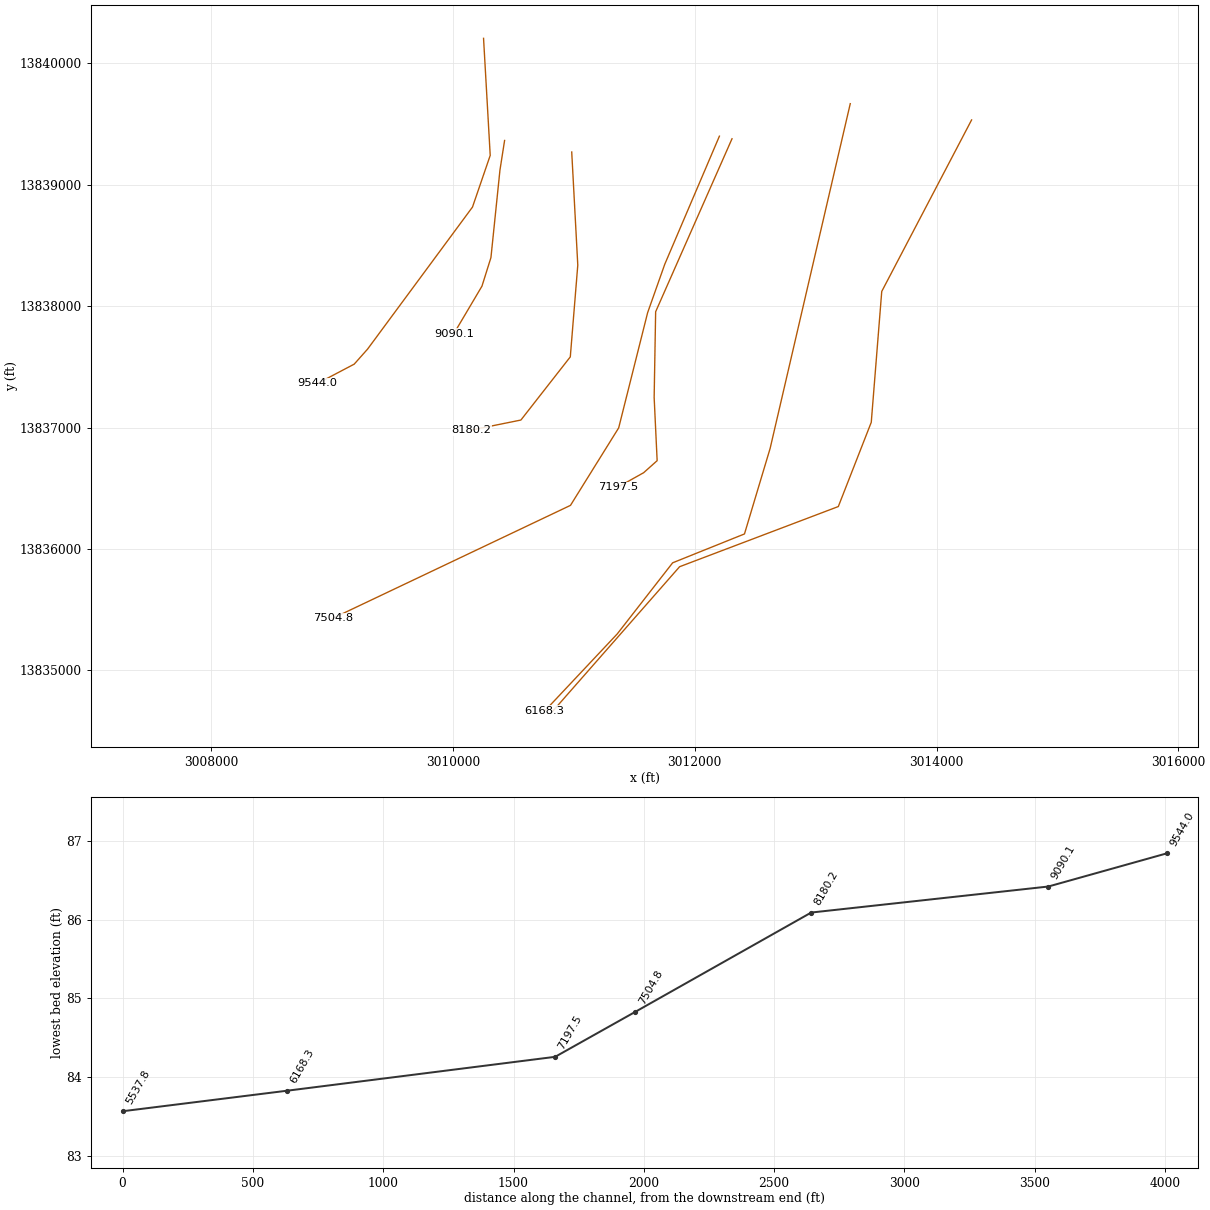
HEC-RAS study T101-00-00.PRJ: T101-00-00

--- T101-00-00.g01 (geometry) --- (continued)

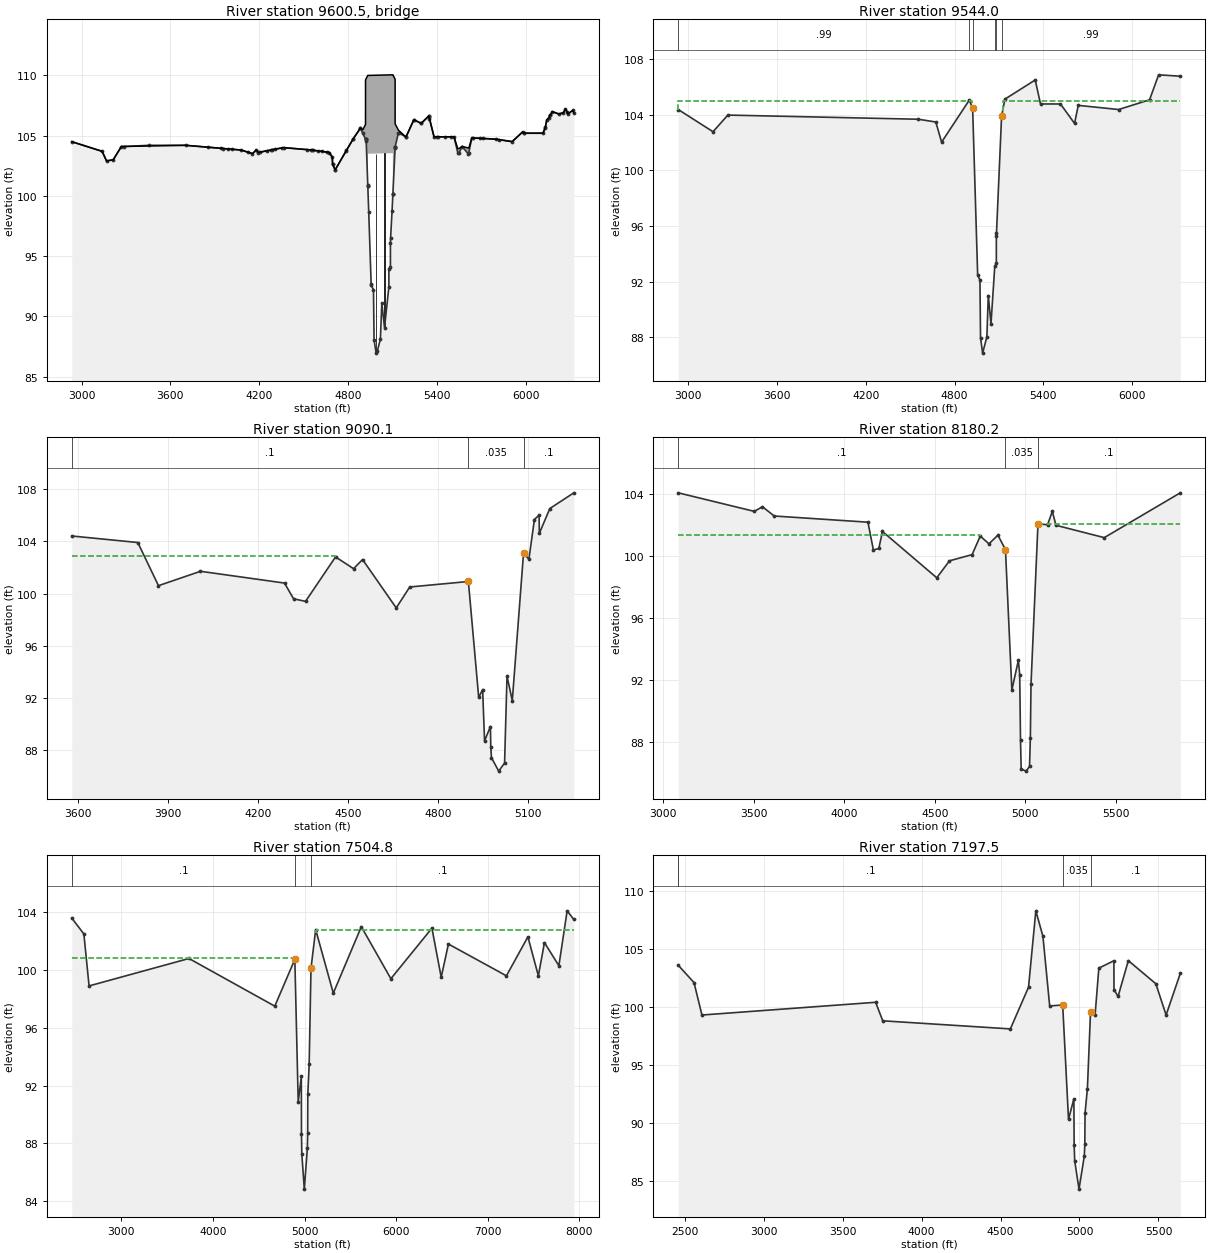
Type RM Length L Ch R = 3 ,9600.5  ,,,
BEGIN DESCRIPTION:
FRY ROAD
Structure ID: T01-3
END DESCRIPTION:
Bridge Culvert--1,0,-1,-1, 0
Deck Dist Width WeirC Skew NumUp NumDn MinLoCord MaxHiCord MaxSubmerge Is_Ogee
10,93,2.6,0, 60, 60, , , 0.95, 0, 1,1,,
  2934.2  3139.2  3169.2  3214.2  3269.2  3702.8  4079.6  4154.6  4179.6  4194.6
    4366    4556  4673.9  4693.9  4695.6  4712.8  4834.9  4883.4    4900 4917.99
  4918.1  4922.5  4933.3 4933.41  4933.5 5102.69  5102.8    5118  5118.1  5140.6
  5191.2  5244.1  5294.5  5345.6  5380.8  5515.8  5540.8  5550.8  5570.8  5610.8
  5615.8  5635.8  5798.5  5908.5  5978.5  5987.3  6117.3  6132.3  6142.3  6157.3
  6162.3  6167.3  6178.6  6223.6  6253.6  6268.6  6278.6  6283.6  6318.6    6325
   104.5   103.7   102.9     103   104.1   104.2  103.81  103.51  103.81  103.61
  104.01  103.81  103.61  103.21  102.66  102.16  104.74  105.63  105.49  105.93
  109.63  109.74     110     110     110  110.05  110.05  109.68  105.98  105.45
  104.89  106.32  106.03  106.64  104.91  104.91  103.93  103.94  104.11  103.98
  103.98  104.81  104.71  104.51  105.31  105.21  105.21   105.7   106.3   106.5
   106.7   106.7     107   106.8   106.9   107.2     107   106.8   107.1   106.9
   104.5   103.7   102.9     103   104.1   104.2   103.8   103.5   103.8   103.6
     104   103.8   103.6   103.2  102.65  102.15  104.73  105.62  105.18  104.71
  104.71  104.59  100.88  100.84   103.5  103.55  100.15  104.03  104.06  105.25
  104.88  106.31  106.02  106.63   104.9   104.9   103.6   103.6   104.1   103.5
   103.6   104.8   104.7   104.5   105.3   105.2   105.2   105.7   106.3   106.5
   106.7   106.7     107   106.8   106.9   107.2     107   106.8   107.1   106.9
  2934.2  3139.2  3169.2  3214.2  3269.2  3702.8  4079.6  4154.6  4179.6  4194.6
    4366    4556  4673.9  4693.9  4695.6  4712.8  4834.9  4883.4    4900 4917.99
  4918.1  4922.5  4933.3 4933.41  4933.5 5102.69  5102.8    5118  5118.1  5140.6
  5191.2  5244.1  5294.5  5345.6  5380.8  5515.8  5540.8  5550.8  5570.8  5610.8
  5615.8  5635.8  5798.5  5908.5  5978.5  5987.3  6117.3  6132.3  6142.3  6157.3
  6162.3  6167.3  6178.6  6223.6  6253.6  6268.6  6278.6  6283.6  6318.6    6325
   104.5   103.7   102.9     103   104.1   104.2  103.81  103.51  103.81  103.61
  104.01  103.81  103.61  103.21  102.66  102.16  104.74  105.63  105.49  105.93
  109.63  109.74     110     110     110  110.05  110.05  109.68  105.98  105.45
  104.89  106.32  106.03  106.64  104.91  104.91  103.93  103.94  104.11  103.98
  103.98  104.81  104.71  104.51  105.31  105.21  105.21   105.7   106.3   106.5
   106.7   106.7     107   106.8   106.9   107.2     107   106.8   107.1   106.9
   104.4   103.6   102.8   102.9     104   104.1   103.7   103.4   103.7   103.5
   103.9   103.7   103.5   103.1  102.55  102.05  104.63  105.52  105.08  104.61
  104.61  104.49  100.78  100.74   103.4  103.45  100.05  103.93  103.96  105.15
  104.78  106.21  105.92  106.53   104.8   104.8   103.5   103.5     104   103.4
   103.5   104.7   104.6   104.4   105.2   105.1   105.1   105.6   106.2   106.4
   106.6   106.6   106.9   106.7   106.8   107.1   106.9   106.7     107   106.8
Pier Skew, UpSta & Num, DnSta & Num=  ,4989.9, 2 ,4989.9, 2 , 0 , 0 , 0 ,,
     1.4     1.4
   85.96  104.52
     1.4     1.4
   85.86  104.42
Pier Skew, UpSta & Num, DnSta & Num=  ,5046.4, 2 ,5046.4, 2 , 0 , 0 , 0 ,,
     1.4     1.4
   88.15  104.53
     1.4     1.4
   88.05  104.43
Abutment Skew #Up #Dn= , 2 , 2
  4933.3  4956.3
   103.5   92.61
  4933.3  4956.3
   103.4   92.51
Abutment Skew #Up #Dn= , 2 , 2
  5087.4 5102.89
    96.5  103.55
  5087.4 5102.89
    96.5  103.45
BR Coef= 1 , 1 , 0 ,1.25, 0 ,,,0.8,0,2,0,
WSPro=,,,, 1 ,,,, 0 ,,,, 0 ,,,,-1 ,-1 ,-1 , 0 , 0 , 0 , 0 , 0
BR U #Sta/Elev= 124
  2934.2   104.5  3139.2   103.7  3169.2   102.9  3214.2     103  3269.2   104.1
  3288.5   104.1  3458.5   104.2  3702.8   104.2  3855.8  104.04  3940.8  103.95
  3955.8  103.93  3990.8  103.89  4015.8  103.87  4079.6   103.8  4121.9  103.63
  4154.6   103.5  4179.6   103.8  4191.9  103.64  4194.6   103.6  4206.9  103.63
  4251.9  103.75  4276.9  103.81  4286.9  103.84  4309.6   103.9  4355.4  103.98
    4366     104  4522.7  103.84  4552.7   103.8    4556   103.8  4562.7  103.79
  4597.7  103.73  4622.7  103.69    4657  103.63  4673.9   103.6  4693.9   103.2
  4695.6  102.65    4697  102.61  4712.8  102.15  4714.2  102.18  4787.8  103.76
  4788.5  103.77  4834.9  104.73    4836  104.75  4882.9  105.61  4883.4  105.62
    4900  105.18 4917.99  104.71  4918.1  104.71 4918.21   104.7  4922.5  104.59
  4933.3  100.88 4933.41  100.84  4933.5  100.81  4939.8   98.64  4956.2   92.65
  4956.3   92.61  4971.8    92.2  4975.8   88.05  4989.9   86.95  4997.3   87.09
  5018.6   88.12  5028.1    91.1  5046.4   89.07  5075.8   92.45  5075.9    93.9
  5086.3    94.1  5086.4    96.1  5087.4    96.5  5097.3   98.74 5102.69  100.12
  5102.8  100.15  5102.9  100.17 5117.89  104.01    5118  104.03  5118.1  104.06
 5118.21  104.07  5140.6  105.25    5142  105.24  5191.2  104.88  5192.1   104.9
  5243.8   106.3  5244.1  106.31  5294.5  106.02  5295.3  106.03  5345.2  106.63
  5345.6  106.63  5346.4  106.59  5349.8  106.42  5380.8   104.9  5399.8   104.9
  5409.8   104.9  5454.8   104.9  5495.7   104.9  5515.8   104.9  5540.8   103.6
  5550.8   103.6  5570.8   104.1  5610.8   103.5  5615.8   103.6  5635.8   104.8
  5641.5   104.8  5693.5   104.8  5711.5  104.78  5798.5   104.7    5817  104.67
  5908.5   104.5  5978.5   105.3  5985.8  105.22  5987.3   105.2  6117.3   105.2
  6129.2   105.6  6132.3   105.7  6142.3   106.3  6157.3   106.5  6162.3   106.7
  6167.3   106.7  6178.6     107  6223.6   106.8  6253.6   106.9  6268.6   107.2
  6278.6     107  6283.6   106.8  6318.6   107.1    6325   106.9
BR U #Mann= 6
  2934.2     .99    4900      .1  4922.5    .035  5075.8    .015 5102.69    .035
    5118     .99
BR U Banks=4922.5,5118
BR D #Sta/Elev= 124
  2934.2   104.4  3139.2   103.6  3169.2   102.8  3214.2   102.9  3269.2     104
  3288.5     104  3458.5   104.1  3702.8   104.1  3855.8  103.94  3940.8  103.85
  3955.8  103.83  3990.8  103.79  4015.8  103.77  4079.6   103.7  4121.9  103.53
  4154.6   103.4  4179.6   103.7  4191.9  103.54  4194.6   103.5  4206.9  103.53
  4251.9  103.65  4276.9  103.71  4286.9  103.74  4309.6   103.8  4355.4  103.88
    4366   103.9  4522.7  103.74  4552.7   103.7    4556   103.7  4562.7  103.69
  4597.7  103.63  4622.7  103.59    4657  103.53  4673.9   103.5  4693.9   103.1
  4695.6  102.55    4697  102.51  4712.8  102.05  4714.2  102.08  4787.8  103.66
  4788.5  103.67  4834.9  104.63    4836  104.65  4882.9  105.51  4883.4  105.52
    4900  105.08 4917.99  104.61  4918.1  104.61 4918.21   104.6  4922.5  104.49
  4933.3  100.78 4933.41  100.74  4933.5  100.71  4939.8   98.54  4956.2   92.55
  4956.3   92.51  4971.8    92.1  4975.8   87.95  4989.9   86.85  4997.3   86.99
  5018.6   88.02  5028.1      91  5046.4   88.97  5075.8   92.36  5075.9    93.9
  5086.3    94.1  5086.4    96.1  5087.4    96.5  5097.3   98.64 5102.69  100.02
  5102.8  100.05  5102.9  100.07 5117.89  103.91    5118  103.93  5118.1  103.96
 5118.21  103.97  5140.6  105.15    5142  105.14  5191.2  104.78  5192.1   104.8
  5243.8   106.2  5244.1  106.21  5294.5  105.92  5295.3  105.93  5345.2  106.53
  5345.6  106.53  5346.4  106.49  5349.8  106.32  5380.8   104.8  5399.8   104.8
  5409.8   104.8  5454.8   104.8  5495.7   104.8  5515.8   104.8  5540.8   103.5
  5550.8   103.5  5570.8     104  5610.8   103.4  5615.8   103.5  5635.8   104.7
  5641.5   104.7  5693.5   104.7  5711.5  104.68  5798.5   104.6    5817  104.57
  5908.5   104.4  5978.5   105.2  5985.8  105.12  5987.3   105.1  6117.3   105.1
  6129.2   105.5  6132.3   105.6  6142.3   106.2  6157.3   106.4  6162.3   106.6
  6167.3   106.6  6178.6   106.9  6223.6   106.7  6253.6   106.8  6268.6   107.1
  6278.6   106.9  6283.6   106.7  6318.6     107    6325   106.8
BR D #Mann= 6
  2934.2     .99    4900      .1  4922.5    .035  5075.8    .015 5102.69    .035
    5118     .99
BR D Banks=4922.5,5118
BC Design=,, 0 ,, 0 ,,,,,,
BC HTab HWMax=107.19
BC Use User HTab Curves=0
BC User HTab FreeFlow(D)= 0

Type RM Length L Ch R = 1 ,9544.0  ,453.9,453.9,453.9
BEGIN DESCRIPTION:
Downstream Section of Bridge/Culvert/Weir
PATH CUT IN RIGHT BANK
END DESCRIPTION:
XS GIS Cut Line= 6
       3010252.6     13840204.89      3010307.78     13839240.99
      3010161.12     13838815.41      3009293.46      13837646.2
      3009182.69     13837522.16      3008880.07     13837363.64
#Sta/Elev= 30
  2934.2  104.39  3169.2  102.79  3269.2  103.99    4556  103.69  4673.9  103.49
  4712.8  102.04    4900  105.07  4922.5  104.48  4956.3    92.5  4971.8   92.09
  4975.8   87.94  4989.9   86.84  5018.6   88.01  5028.1   90.99  5046.4   88.96
    5072    93.1  5082.5    93.3  5082.6    95.3  5083.6    95.5    5118  103.92
  5140.6  105.14  5345.2  106.52  5380.8  104.79  5515.8  104.79  5610.8  103.39
  5635.8  104.69  5908.5  104.39  6117.3  105.09  6178.6  106.89    6325  106.79
#Mann= 6 ,-1 , 0
  2934.2     .99       0    4900      .1       0  4922.5    .035       0
    5072    .015       0  5083.6    .035       0    5118     .99       0
#XS Ineff= 2 , 0
       0    4920     105    5125       0     105
Permanent Ineff=
       F       F
Bank Sta=4922.5,5118
XS Rating Curve= 0 ,0
Exp/Cntr=0.5,0.3

Type RM Length L Ch R = 1 ,9090.1  ,921.7,909.9,894
BEGIN DESCRIPTION:
Cross Section 9090.1
END DESCRIPTION:
XS GIS Cut Line= 5
      3010426.64      13839363.8      3010388.07     13839117.93
      3010313.75     13838399.51      3010239.43     13838164.17
      3010006.91      13837773.1
#Sta/Elev= 30
  3579.8   104.4  3799.8   103.9  3868.7   100.6  4008.7   101.7  4288.7   100.8
  4318.7    99.6  4358.7    99.4  4458.7   102.8  4518.7   101.9  4548.7   102.6
  4660.9    98.9  4705.9   100.5  4901.3  100.92  4935.7   92.05  4948.8   92.66
  4955.2   88.73  4974.7   89.83    4976   88.27  4978.2   87.45  5002.3   86.42
  5021.9   87.04    5030   93.68  5047.6   91.81    5085  103.07    5103  102.63
  5121.3  105.66    5137     106  5137.7   104.6  5172.7   106.5  5252.7   107.7
#Mann= 3 , 1 , 0
  3579.8      .1       0  4901.3    .035       0    5085      .1       0
#XS Ineff= 2 , 0
       0    4460   102.9               0
Permanent Ineff=
       F       F
Bank Sta=4901.3,5085
XS Rating Curve= 0 ,0
Exp/Cntr=0.3,0.1

Type RM Length L Ch R = 1 ,8180.2  ,623,675.4,690.1
BEGIN DESCRIPTION:
Cross Section 8180.2
END DESCRIPTION:
XS GIS Cut Line= 5
      3010982.03     13839268.76      3011032.17     13838337.58
      3010970.24       13837582.      3010561.48     13837061.77
      3010149.69     13836978.92
#Sta/Elev= 30
  3082.9   104.1  3502.9   102.9  3547.9   103.2  3612.9   102.6  4130.5   102.2
  4160.5   100.4  4190.5   100.5  4210.5   101.6  4510.5    98.6  4580.5    99.7
  4705.5   100.1  4750.5   101.3  4798.6   100.8  4847.9  101.36  4889.7  100.43
  4925.1   91.34    4961   93.26  4968.4   92.31  4972.8   88.11  4976.5   86.22
  5004.4   86.09  5022.6    86.4  5027.2   88.24  5030.8   91.72  5069.3   102.1
    5122  102.03  5148.6   102.9  5168.6     102  5435.2   101.2  5855.2   104.1
#Mann= 3 , 1 , 0
  3082.9      .1       0  4889.7    .035       0  5069.3      .1       0
#XS Ineff= 2 , 0
       0    4751  101.35    5072       0   102.1
Permanent Ineff=
       F       F
Bank Sta=4889.7,5069.3
XS Rating Curve= 0 ,0
Exp/Cntr=0.3,0.1

Type RM Length L Ch R = 1 ,7504.8  ,273.8,307.3,362.8
BEGIN DESCRIPTION:
Cross Section 7504.8-Interpolated
END DESCRIPTION:
XS GIS Cut Line= 6
      3012203.76     13839399.48       3011751.7     13838344.68
      3011609.88     13837945.81      3011370.56     13836997.38
      3010971.69     13836359.18      3009003.91     13835428.48
#Sta/Elev= 30
  2459.4   103.6  2591.4   102.5  2648.2    98.9  3738.3   100.8  4674.8    97.5
  4893.7  100.74  4930.5   90.86  4964.6   92.64  4966.2   88.66  4969.8   87.27
    4997   84.83  5030.5   87.68  5033.8   88.72  5035.2   91.39  5050.1   93.49
  5069.9  100.11    5121   102.8  5313.4    98.4  5619.3     103  5941.6    99.4
  6389.7   102.9  6490.9    99.5  6569.7   101.8  7202.7    99.6  7437.1   102.3
  7551.2    99.6  7617.6   101.9  7775.1   100.3  7865.2   104.1  7938.4   103.5
#Mann= 3 , 1 , 0
  2459.4      .1       0  4893.7    .035       0  5069.9      .1       0
#XS Ineff= 2 , 0
       0    4885  100.85    5130       0   102.8
Permanent Ineff=
       F       F
Bank Sta=4893.7,5069.9
XS Rating Curve= 0 ,0
Exp/Cntr=0.3,0.1

Type RM Length L Ch R = 1 ,7197.5  ,1054.2,1029.2,1021.9
BEGIN DESCRIPTION:
Cross Section 7197.5
END DESCRIPTION:
XS GIS Cut Line= 6
      3012307.98     13839378.05      3011676.27      13837953.6
      3011663.88     13837247.57      3011688.66     13836727.33
      3011577.18     13836628.24      3011363.12     13836509.05
#Sta/Elev= 30
  2459.1   103.6  2559.1   102.1  2609.1    99.3  3709.1   100.4  3754.1    98.8
  4562.3    98.1  4677.3   101.7  4723.5   108.3  4768.5   106.1  4811.3  100.08
  4893.7  100.17  4930.5   90.29  4964.6   92.07  4966.2   88.09  4969.8    86.7
    4997   84.26  5030.5   87.11  5033.8   88.15  5035.2   90.82  5050.1   92.92
  5069.9   99.54  5098.6   99.26  5122.6  103.35    5218  103.99  5218.5   101.5
  5244.3   100.9  5309.3     104  5483.5     102  5548.5    99.3  5638.5   102.9
#Mann= 4 , 1 , 0
  2459.1      .2       0  2459.1      .1       0  4893.7    .035       0
  5069.9      .1       0
#XS Ineff= 2 , 0
       0  4867.1  100.02               0
Permanent Ineff=
       F       F
Bank Sta=4893.7,5069.9
XS Rating Curve= 0 ,0
Exp/Cntr=0.3,0.1

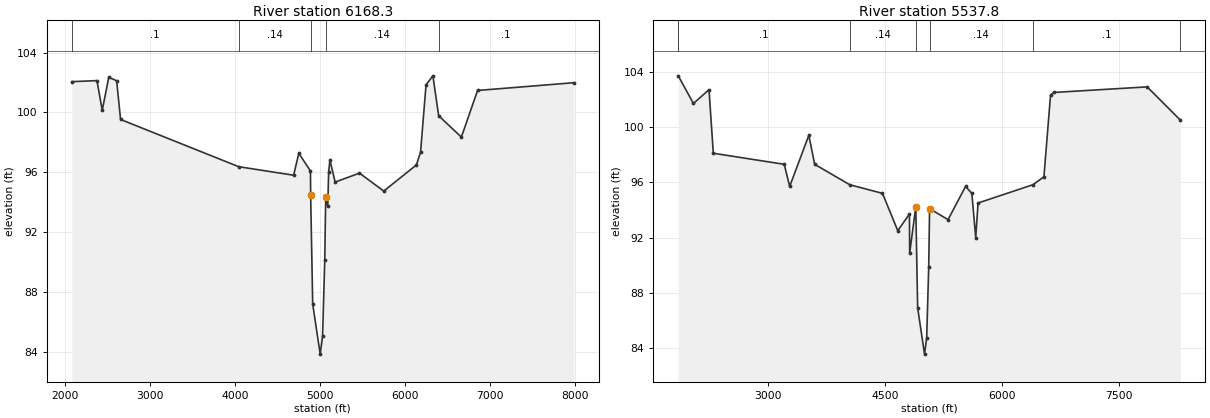
Type RM Length L Ch R = 1 ,6168.3  ,654.5,630.5,600.7
BEGIN DESCRIPTION:
Cross Section 6168.3-Interpolated
END DESCRIPTION:
XS GIS Cut Line= 6
      3013286.23     13839666.93      3012623.37     13836828.59
      3012411.11     13836123.91       3011816.8     13835886.18
      3011358.33     13835300.36      3010758.59     13834665.85
#Sta/Elev= 30
  2080.7  102.06  2377.3  102.13    2439  100.14  2516.1  102.35  2608.7  102.12
    2655   99.53  4045.2   96.37  4691.3    95.8  4752.2   97.27  4889.5   96.08
  4891.5   94.48  4915.8   87.18  5003.9   83.83  5031.7   85.02  5057.5   90.12
  5068.9   94.35    5093   93.72  5103.2      96  5118.2   96.82  5179.6   95.34
  5466.3   95.94  5751.7   94.74  6136.3   96.49  6184.8   97.35  6249.4  101.85
  6330.2  102.45  6397.7   99.78  6665.1   98.35  6855.6  101.47  7988.5  101.99
#Mann= 5 , 1 , 0
  2080.7      .1       0  4045.2     .14       0  4891.5    .035       0
  5068.9     .14       0  6397.7      .1       0
Bank Sta=4891.5,5068.9
XS Rating Curve= 0 ,0
Exp/Cntr=0.3,0.1

Type RM Length L Ch R = 1 ,5537.8  ,0,0,0
BEGIN DESCRIPTION:
Cross Section 5537.8
END DESCRIPTION:
XS GIS Cut Line= 6
      3014289.83     13839532.88      3013546.64     13838120.82
      3013459.93     13837043.19      3013187.43     13836349.54
      3011874.46     13835854.08      3010809.21      13834646.4
#Sta/Elev= 30
  1843.7   103.7  2038.7   101.7  2238.7   102.7  2293.7    98.1  3203.7    97.3
  3273.7    95.7  3519.4    99.4  3594.4    97.3  4045.2   95.82  4464.4    95.2
  4660.5    92.5  4810.5    93.7  4813.3   90.87  4891.5   94.22  4915.8   86.92
  5003.9   83.57  5031.7   84.76  5057.5   89.86  5068.9   94.09  5305.8    93.3
  5530.8    95.7  5610.8    95.2  5660.8      92  5690.8    94.5  6397.7   95.83
  6535.8    96.4  6620.8   102.3  6669.1   102.5  7860.4   102.9  8285.9   100.5
#Mann= 7 , 1 , 0
  1843.7      .2       0  1843.7      .1       0  4045.2     .14       0
  4891.5    .035       0  5068.9     .14       0  6397.7      .1       0
  8285.9      .2       0
Bank Sta=4891.5,5068.9
XS Rating Curve= 0 ,0
Exp/Cntr=0.3,0.1

Chan Stop Cuts=-1
Use User Specified Reach Order=0
Composite Channel Slope=5